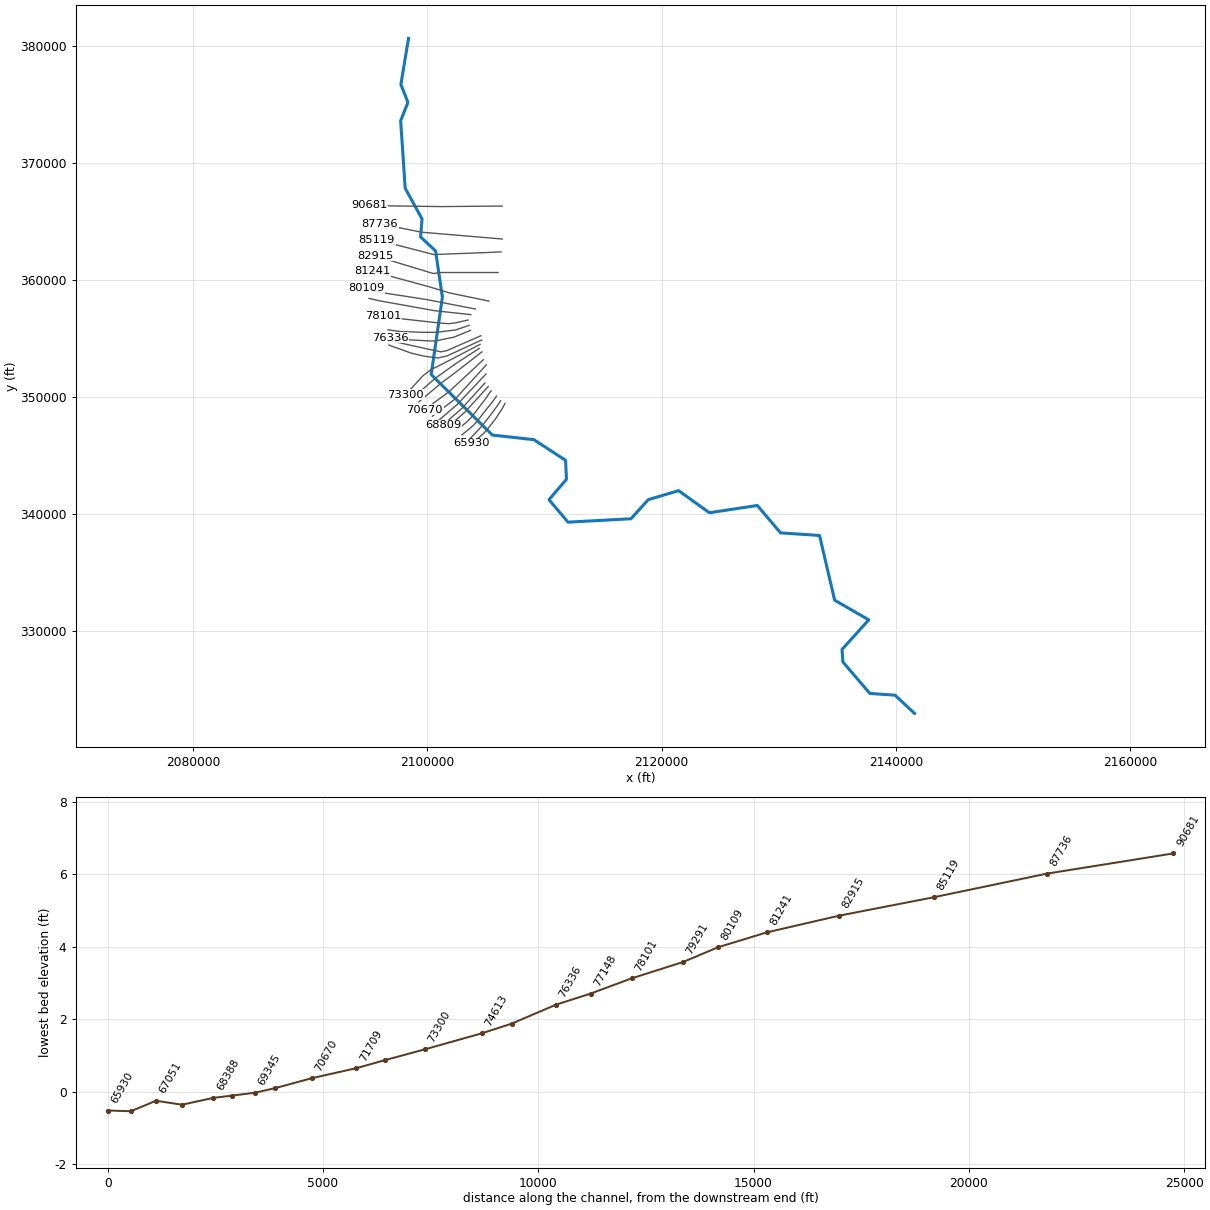
--- AshepooRiver.prj (project) ---

Proj Title=S-15-41 over Ashepoo River
Current Plan=p04
Default Exp/Contr=0.3,0.1
English Units
Geom File=g03
Geom File=g10
Geom File=g12
Geom File=g04
Geom File=g05
Flow File=f02
Flow File=f03
Flow File=f04
Plan File=p03
Plan File=p02
Plan File=p01
Plan File=p04
Plan File=p05
Plan File=p07
Y Axis Title=Elevation
X Axis Title(PF)=Main Channel Distance
X Axis Title(XS)=Station
BEGIN DESCRIPTION:
END DESCRIPTION:
DSS File=dss
DSS Export Rating Curves= 0
DSS Export Rating Curve Sorted= 0
DSS Export Volume Flow Curves= 0
DXF OffsetX= 0
DXF OffsetY= 0
DXF ScaleX= 1
DXF ScaleY= 10

--- AshepooRiver.p04 (plan) ---

Plan Title=Sensitivity
Program Version=6.60
Short Identifier=Sensitivity
Geom File=g03
Flow File=f02
Subcritical Flow
K Sum by GR= 0
Std Step Tol= 0.01
Critical Tol= 0.01
Num of Std Step Trials= 20
Max Error Tol= 0.3
Flow Tol Ratio= 0.001
Split Flow NTrial= 30
Split Flow Tol= 0.02
Split Flow Ratio= 0.02
Log Output Level= 0
Friction Slope Method= 1
Unsteady Friction Slope Method= 2
Unsteady Bridges Friction Slope Method= 1
Calc Critical at every XS
Parabolic Critical Depth
Global Vel Dist= 0 , 0 , 0
Global Log Level= 0
CheckData=True
Encroach Param=-1 ,0,0, 0
Flow Ratio Tolerance=0.1
Flow Ratio Min Ratio=0.5
Flow Ratio Max Ratio=4
Flow Ratio Max Iterations= 10
Computation Interval=1MIN
Output Interval=1HOUR
Instantaneous Interval=1HOUR
Mapping Interval=1HOUR
Computation Time Step Use Courant=        0
Computation Time Step Use Time Series=    0
Computation Time Step Count To Double=0
Computation Time Step Max Doubling=0
Computation Time Step Max Halving=0
Computation Time Step Residence Courant=0
Run HTab= 0
Run UNet= 0
Run Sediment= 0
Run PostProcess= 0
Run WQNet= 0
Run RASMapper= 0
UNET Theta= 1
UNET Theta Warmup= 1
UNET ZTol= 0.02
UNET ZSATol= 0.02
UNET MxIter= 20
UNET Max Iter WO Improvement= 0
UNET MaxInSteps= 0
UNET DtIC= 0
UNET DtMin= 0
UNET MaxCRTS= 20
UNET WFStab= 2
UNET SFStab= 1
UNET WFX= 1
UNET SFX= 1
UNET Gravity=32.17405
UNET 1D Methodology=Finite Difference
UNET DSS MLevel= 4
UNET Pardiso=0
UNET DZMax Abort= 100
UNET Use Existing IB Tables=-1
UNET Froude Reduction=False
UNET Froude Limit= 0.8
UNET Froude Power= 4
UNET D1 Cores= 0
UNET WindReference=Eulerian
UNET WindDragFormulation=Hsu (1988)
UNET D2 Coriolis=0
UNET D2 Cores= 0
UNET D2 Theta= 1
UNET D2 Theta Warmup= 1
UNET D2 Z Tol= 0.01
UNET D2 Volume Tol= 0.01
UNET D2 Max Iterations= 20
UNET D2 Advanced Convergence=0
UNET D2 WS Max Tol=0.15
UNET D2 WS RMS Tol=0.002
UNET D2 WS Stall Tol=1
UNET D2 Equation= 0
UNET D2 RampUpFraction=0.1
UNET D2 TimeSlices= 1
UNET D2 Turbulence Formulation=None
UNET D2 Eddy Viscosity=0.3
UNET D2 Transverse Eddy Viscosity=0.1
UNET D2 Smagorinsky Mixing=0.05
UNET D2 BCVolumeCheck=0
UNET D2 Cores=0
UNET D2 SolverType=PARDISO (Direct)
UNET D2 Minimum Iterations= 3
UNET D2 Maximum Iterations= 30
UNET D2 Restart Number= 10
UNET D2 Relaxation Coeff=1.3
UNET D2 SOR Precondition Iterations= 10
UNET D2 ILUT Maximum Fill= 8
UNET D2 ILUT Tolerance=1E-08
UNET D2 Convergence Tolerance=0.00001
PS Theta= 1
PS WS Tol= 0.01
PS Volume Tol= 0.01
PS Max Iterations= 20
PS Equation= 0
PS Advance Time Step=-1
PS Target Courant=0.9
PS Time Slices= 1
PS Iterate With 2D=0
PS Project Initial WSE from DS=-1
PS Ramp Up Initial WSE from US=-1
PS Cores=0
UNET D1D2 MaxIter= 0
UNET D1D2 ZTol=0.01
UNET D1D2 QTol=0.1
UNET D1D2 MinQTol=1
Write IC File= 0
Write IC File at Fixed DateTime=0
Write IC File at Sim End=0
Echo Input=False
Echo Parameters=False
Echo Output=False
Write Detailed= 0
HDF Write Warmup=0
HDF Write Time Slices=0
HDF Flush=0
HDF Compression= 1
HDF Chunk Size= 1
HDF Spatial Parts= 1
HDF Use Max Rows=0
HDF Fixed Rows= 1
Calibration Method= 0
Calibration Iterations= 20
Calibration Max Change=0.05
Calibration Tolerance=0.2
Calibration Maximum=1.5
Calibration Minimum=0.5
Calibration Optimization Method= 1
WQ AD Non Conservative
WQ ULTIMATE=-1
WQ Max Comp Step=1HOUR
WQ Output Interval=15MIN
WQ Output Selected Increments= 0
WQ Create Restart=0
WQ Fixed Restart=0
WQ System Summary=0
WQ Write To DSS=0
Sorting and Armoring Iterations= 10
XS Update Threshold= 0.02
Bed Roughness Predictor= 0
Processes Affected by Predictor=Sediment Only
Hydraulics Update Threshold= 0.02
Energy Slope Method= 1
Volume Change Method= 1
Sediment Retention Method= 0
Sediment TS Multiplier= 1
Warm Up Method= 0
XS Weighting Method= 0
Number of US Weighted Cross Sections= 1
Number of DS Weighted Cross Sections= 1
Upstream XS Weight=0
Main XS Weight=1
Downstream XS Weight=0
Number of DS XS's Weighted with US Boundary= 1
Upstream Boundary Weight= 1
Weight of XSs Associated with US Boundary= 0
Number of US XS's Weighted with DS Boundary= 1
Downstream Boundary Weight= 0.5
Weight of XSs Associated with DS Boundary= 0.5
Percentile Method= 0
Sediment Output Level= 3
Mass or Volume Output= 0
Output Increment Type= 1
Profile and TS Output Increment= 1
Transport Output Increment 1
XS Output Flag= 0
XS Output Increment= 10
Read HDF5 Sediment Hotstart= 0
Sediment Hotstart Type= 0
Write Gradation File= 0
Read Gradation Hotstart= 0
Write HDF5 File= 1
Write Binary Output= 1
Write DSS Sediment File= 0
DSS Sediment Output Type= 1
SV Curve= 0
Specific Gage Flag= 0
Subcell Erosion Methods= 0
Subcell Deposition Methods= 0
Advection Scheme= 1
Matrix Solver= 0
Implicit Weighting Factor= 1
Maximum Outer Loop Convergence Iterations= 5
Convergence Maximum Absolute= 0.001
Convergence RMSE= 0.0001
Grain Fractions Max Abs Error= 0.001
Max Subgrid Regions= 1
Max Subgrid Length Scale= 3.402823E+38
Initial Layer Thickness= 3
Min Layer Thickness= 0.1
Max Layer Thickness= 6
Number of Layers= 5

--- AshepooRiver.p01 (plan) ---

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Plan Title=Proposed Conditions
Short Identifier=PROP
Geom File=g04
Flow File=f04

--- AshepooRiver.p02 (plan) ---

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Plan Title=Existing Conditions
Short Identifier=Existing
Geom File=g03
Flow File=f04

--- AshepooRiver.p03 (plan) ---

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Plan Title=Natural Conditions
Short Identifier=Natural
Geom File=g10
Flow File=f04

--- AshepooRiver.p05 (plan) ---

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Plan Title=Corrected Effective-Floodway
Short Identifier=CE-FW
Geom File=g12
Flow File=f03
Encroach Param=-1 ,0,0, 2
Encroach River=River 1
Encroach Reach=Reach 1
Encroach Node=57469
       1    1150    3130
Encroach Node=56776
       1    1279    3268
Encroach Node=56522
       1    1276    3124
Encroach Node=55906
       1    1859    3499
Encroach Node=55848
       1    1905    3550
Encroach Node=55386
       1    2162    3879
Encroach Node=54912
       1    2459    4260
Encroach Node=54169
       1    3268    5161
Encroach Node=53189
       1    4061    5973
Encroach Node=51598
       1    4574    6719
Encroach Node=50530
       1    5100    7004
Encroach Node=49691
       1    5175    7309
Encroach Node=48739
       1    5083    7280
Encroach Node=47790
       1    4760    6697
Encroach Node=46993
       1    4778    6604
Encroach Node=45829
       1    5042    6188
Encroach Node=45112
       1    5996    6256
Encroach Node=44964
       1    5167    6638
Encroach Node=44133
       1    5155    6024

--- AshepooRiver.p07 (plan) ---

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Plan Title=Post Project-Floodway
Short Identifier=POST-FW
Geom File=g05
Flow File=f03
Encroach Param=-1 ,0,0, 2
Encroach River=River 1
Encroach Reach=Reach 1
Encroach Node=57469
       1    1150    3130
Encroach Node=56776
       1    1279    3268
Encroach Node=56522
       1    1276    3124
Encroach Node=55906
       1    1859    3499
Encroach Node=55848
       1    1905    3550
Encroach Node=55386
       1    2162    3879
Encroach Node=54912
       1    2459    4260
Encroach Node=54169
       1    3268    5161
Encroach Node=53189
       1    4061    5973
Encroach Node=51598
       1    4574    6719
Encroach Node=50530
       1    5100    7004
Encroach Node=49691
       1    5175    7309
Encroach Node=48739
       1    5083    7280
Encroach Node=47790
       1    4760    6697
Encroach Node=46993
       1    4778    6604
Encroach Node=45829
       1    5042    6188
Encroach Node=45112
       1    5996    6256
Encroach Node=44964
       1    5167    6638
Encroach Node=44133
       1    5155    6024
DSS File=dss

--- AshepooRiver.f02 (steady flow) ---

Flow Title=Sensitivity
Program Version=6.60
Number of Profiles= 3
Profile Names=100Y-3,100Y,100Y+3
River Rch & RM=River 1,Reach 1         ,90681
    8600    8600    8600
River Rch & RM=River 1,Reach 1         ,37010
    9340    9340    9340
River Rch & RM=River 1,Reach 1         ,15225
   13600   13600   13600
Boundary for River Rch & Prof#=River 1,Reach 1         , 1
Up Type= 0
Dn Type= 1
Dn Known WS=2.95
Boundary for River Rch & Prof#=River 1,Reach 1         , 2
Up Type= 0
Dn Type= 1
Dn Known WS=5.95
Boundary for River Rch & Prof#=River 1,Reach 1         , 3
Up Type= 0
Dn Type= 1
Dn Known WS=8.95
DSS Import GetInterval= 0
DSS Import GetPeak= 0
DSS Import FillOption= 0

--- AshepooRiver.f03 (steady flow) ---

Flow Title=FIS
Program Version=6.60
Number of Profiles= 2
Profile Names=100Y,100Y-FW
River Rch & RM=River 1,Reach 1         ,88407
    7910    7910
Boundary for River Rch & Prof#=River 1,Reach 1         , 1
Up Type= 0
Dn Type= 1
Dn Known WS=8.8
Boundary for River Rch & Prof#=River 1,Reach 1         , 2
Up Type= 0
Dn Type= 1
Dn Known WS=9.7
DSS Import GetInterval= 0
DSS Import GetPeak= 0
DSS Import FillOption= 0

--- AshepooRiver.f04 (steady flow) ---

Flow Title=USGS_Regression
Program Version=6.60
Number of Profiles= 6
Profile Names=2Y,10Y,25Y,50Y,100Y,500Y
River Rch & RM=River 1,Reach 1         ,90681
    1590    4100    5700    7170    8600   12200
River Rch & RM=River 1,Reach 1         ,37010
    1740    4460    6200    7780    9340   13300
River Rch & RM=River 1,Reach 1         ,15225
    2590    6560    9060   11300   13600   19200
Boundary for River Rch & Prof#=River 1,Reach 1         , 1
Up Type= 0
Dn Type= 3
Dn Slope=0.0001
Boundary for River Rch & Prof#=River 1,Reach 1         , 2
Up Type= 0
Dn Type= 3
Dn Slope=0.0001
Boundary for River Rch & Prof#=River 1,Reach 1         , 3
Up Type= 0
Dn Type= 3
Dn Slope=0.0001
Boundary for River Rch & Prof#=River 1,Reach 1         , 4
Up Type= 0
Dn Type= 3
Dn Slope=0.0001
Boundary for River Rch & Prof#=River 1,Reach 1         , 5
Up Type= 0
Dn Type= 3
Dn Slope=0.0001
Boundary for River Rch & Prof#=River 1,Reach 1         , 6
Up Type= 0
Dn Type= 3
Dn Slope=0.0001
DSS Import GetInterval= 0
DSS Import GetPeak= 0
DSS Import FillOption= 0

--- AshepooRiver.g03 (geometry) ---

Geom Title=Existing Conditions
Program Version=6.60

River Reach=River 1         ,Reach 1
Reach XY= 30
2098396.23576606380646.8009591682097747.70079908376704.682944754
2098349.83399384 375176.529045482097726.69704407373600.953953826
2098114.75192337367841.6387006832099554.59564156365212.903242423
2099428.81121289363681.5771457152100708.15579364362482.324665464
2101289.63273322358523.8663055422100333.06655326351923.692230741
2105558.65619563 346752.098334352109100.83653268346361.782563958
 2111805.7756717  344595.11980812111881.37719572 342976.52674064
2110389.42873442341236.9377136342112009.03935508339315.330548813
2117392.06971744339605.4093036772118856.90036976341234.808654364
2121453.98495726342005.6100018412124086.01263555340119.173339952
2128172.64408214340741.1285328922130154.38300398338400.752734401
 2133484.0451058338177.5277912142134776.01760446332648.670849807
2137687.37757937330969.5992636312135404.68988351328442.041949436
 2135479.5315566327368.0527128622137781.44848433324683.100655903
2139929.12472133324531.7252012472141596.00533789322979.696540254

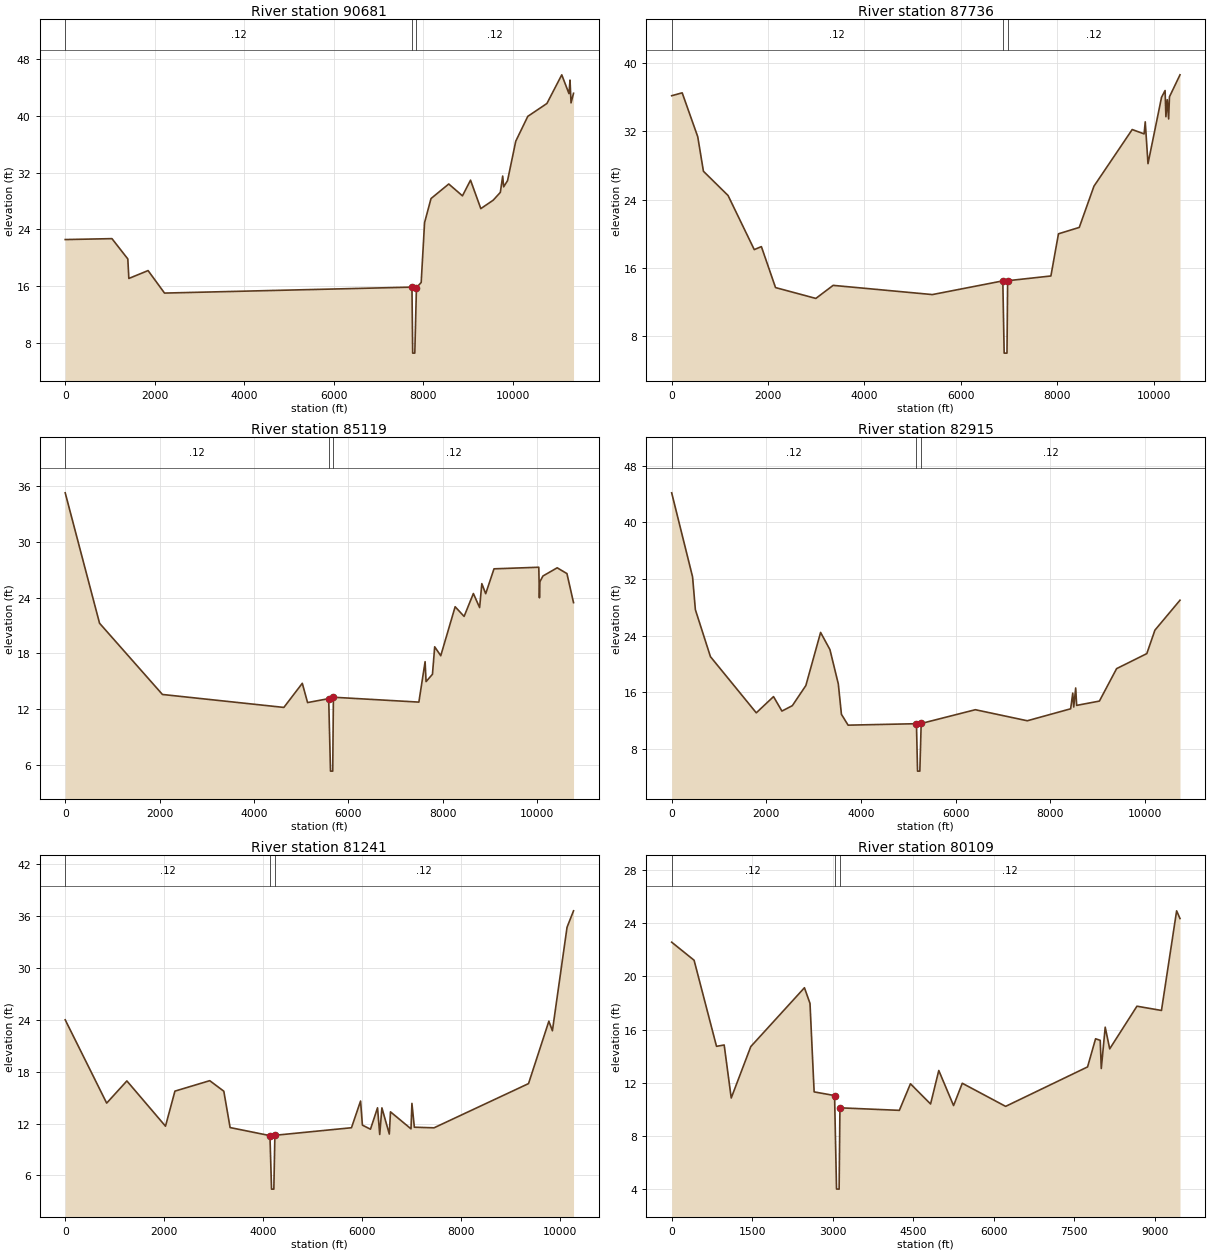
Type RM Length L Ch R = 1 ,90681   ,2944.8,2944.8,2944.8
XS GIS Cut Line= 4
2106397.55682745366319.4387589582101182.35958186366273.012670718
2095719.55653232366350.3894844512095038.64057147366396.815572691
#Sta/Elev= 30
       0   22.58    1045   22.71  1399.4   19.85  1422.4    17.1  1852.3   18.21
  2219.9   15.04    775015.87843 7766.29    6.58  7813.8    6.58    785015.78977
  7956.4   16.54  8031.9   24.97  8176.3   28.36  8572.5   30.41  8878.7   28.74
  9059.2   30.95    9289   26.94  9564.6   28.12  9725.5   29.23    9778   31.53
  9799.6   30.01  9886.4   30.88 10070.1   36.44 10339.2   39.94 10766.1   41.75
 11098.3   45.79 11259.5   43.14 11282.5   45.05 11305.6   41.8411361.25   43.19
#Mann= 3 ,0,0
       0     .12       0    7750    .041       0    7850     .12       0
Bank Sta=7750,7850
XS Rating Curve= 0 ,0
Exp/Cntr(USF)=0,0
Exp/Cntr=0.3,0.1

Type RM Length L Ch R = 1 ,87736   ,2617.4,2617.4,2617.4
XS GIS Cut Line= 3
2106396.93542404363503.8041623472099505.29078866364086.196666745
  2095946.225484364798.009727677
#Sta/Elev= 30
       0   36.18   218.1   36.52   540.8   31.38     659   27.33  1169.9   24.49
  1713.3   18.15  1861.5    18.5  2154.6    13.7  2991.1   12.43  3350.1   13.96
  5408.5   12.88    687014.48625 6897.76    6.02 6956.29    6.02    697014.50333
  7867.4   15.06  8024.4      20  8456.1   20.75  8760.7   25.58  9554.2   32.22
    9801   31.71  9824.9   33.12  9881.8   28.22   10163      36 10236.6   36.79
 10253.3   33.72 10281.5   35.72 10310.2   33.46 10326.9   36.0510545.76   38.63
#Mann= 3 ,0,0
       0     .12       0    6870    .041       0    6970     .12       0
Bank Sta=6870,6970
XS Rating Curve= 0 ,0
Exp/Cntr(USF)=0,0
Exp/Cntr=0.3,0.1

Type RM Length L Ch R = 1 ,85119   ,2203.7,2203.7,2203.7
XS GIS Cut Line= 4
2106299.87000664362403.7294318162104876.24388478 362339.01915355
2100540.65524092362177.2434578832095687.38437094 363439.09388408
#Sta/Elev= 30
       0   35.25   728.1   21.25  2061.7    13.6  4636.3   12.21  5027.1    14.8
  5139.1   12.735586.82113.15396 5625.24    5.37 5672.39    5.375686.82113.30377
  7498.9   12.78  7631.1   17.12  7651.4   14.98  7787.1   15.77  7834.6   18.72
    7963   17.76  8268.2   23.02  8458.1   21.98  8654.8   24.44    8787   22.93
  8833.9    25.5  8915.9   24.42  9092.2   27.09 10041.7   27.26 10055.2   23.98
 10065.4   25.71 10129.8   26.32 10431.6    27.2 10638.5   26.5810778.33   23.46
#Mann= 3 ,0,0
       0     .12       05586.821    .041       05686.821     .12       0
Bank Sta=5586.821,5686.821
XS Rating Curve= 0 ,0
Exp/Cntr(USF)=0,0
Exp/Cntr=0.3,0.1

Type RM Length L Ch R = 1 ,82915   ,1673.9,1673.9,1673.9
XS GIS Cut Line= 4
2106043.70142807 360642.752451782101182.44207423 360642.75245178
 2100503.1394571360557.8396246392095535.73906933362065.042306397
#Sta/Elev= 30
       0   44.15   441.6   32.28   500.7   27.65     819   21.02  1787.2   13.09
  2151.4   15.38  2328.7   13.34  2548.5    14.1    2834   16.94  3145.8   24.44
  3342.7   22.02  3519.9   17.17  3585.6   12.88  3726.7   11.355170.20611.55534
 5193.38    4.86 5241.73    4.865270.20611.58589  6414.5   13.53  7511.9   11.97
  8427.2   13.66  8471.8   15.87  8492.4   13.91  8533.5    16.6  8554.1   14.14
  9034.8   14.75  9397.8   19.33 10035.7   21.45 10207.1   24.76 10736.9   28.99
#Mann= 3 ,0,0
       0     .12       05170.206    .041       05270.206     .12       0
Bank Sta=5170.206,5270.206
XS Rating Curve= 0 ,0
Exp/Cntr(USF)=0,0
Exp/Cntr=0.3,0.1

Type RM Length L Ch R = 1 ,81241   ,1132.2,1132.2,1132.2
XS GIS Cut Line= 4
2105258.25777701358201.5086714672101882.97289815358902.039495383
 2100205.9445621359411.5164582312095302.22879469360748.893485707
#Sta/Elev= 30
       0   24.01   838.7   14.36  1247.6   16.93  2028.6   11.69  2219.6   15.75
  2923.5   16.96  3208.4   15.74  3335.7   11.534141.57110.59565 4173.95     4.4
 4220.34     4.44241.57110.63325  5790.9   11.51  5974.6    14.6    6012   11.81
  6175.2   11.34  6318.1   13.82  6362.3   10.73  6406.4   13.81  6556.2   10.78
    6580   13.35    6995   11.38  7013.6   14.33  7062.7   11.57  7460.7    11.5
  9372.4   16.62    9784   23.85  9855.4   22.74 10151.4   34.7210282.74   36.63
#Mann= 3 ,0,0
       0     .12       04141.571    .041       04241.571     .12       0
Bank Sta=4141.571,4241.571
XS Rating Curve= 0 ,0
Exp/Cntr(USF)=0,0
Exp/Cntr=0.3,0.1

Type RM Length L Ch R = 1 ,80109   ,817.9,817.9,817.9
XS GIS Cut Line= 4
 2104111.9346106357522.2060543372099845.06504675358350.106118965
2096108.90065254358923.2677021682094813.98003863359284.147217519
#Sta/Elev= 30
       0   22.58   417.7   21.22   835.5   14.74   978.3   14.84  1109.7   10.85
    1474   14.72  2473.6   19.15  2577.2   17.97  2654.1   11.31    303511.03299
  3071.3       4 3119.82    3.99    313510.11057    4242    9.92  4448.6   11.92
  4823.7    10.4  4976.5   12.92    5252   10.28  5414.3   11.96    6222   10.22
  7748.4   13.19  7897.9   15.31  7984.2   15.19  8004.1   13.07  8077.2   16.18
    8161   14.55  8668.7   17.76  9125.3   17.44  9407.9   24.949470.586   24.36
#Mann= 3 ,0,0
       0     .12       0    3035    .041       0    3135     .12       0
Bank Sta=3035,3135
XS Rating Curve= 0 ,0
Exp/Cntr(USF)=0,0
Exp/Cntr=0.3,0.1

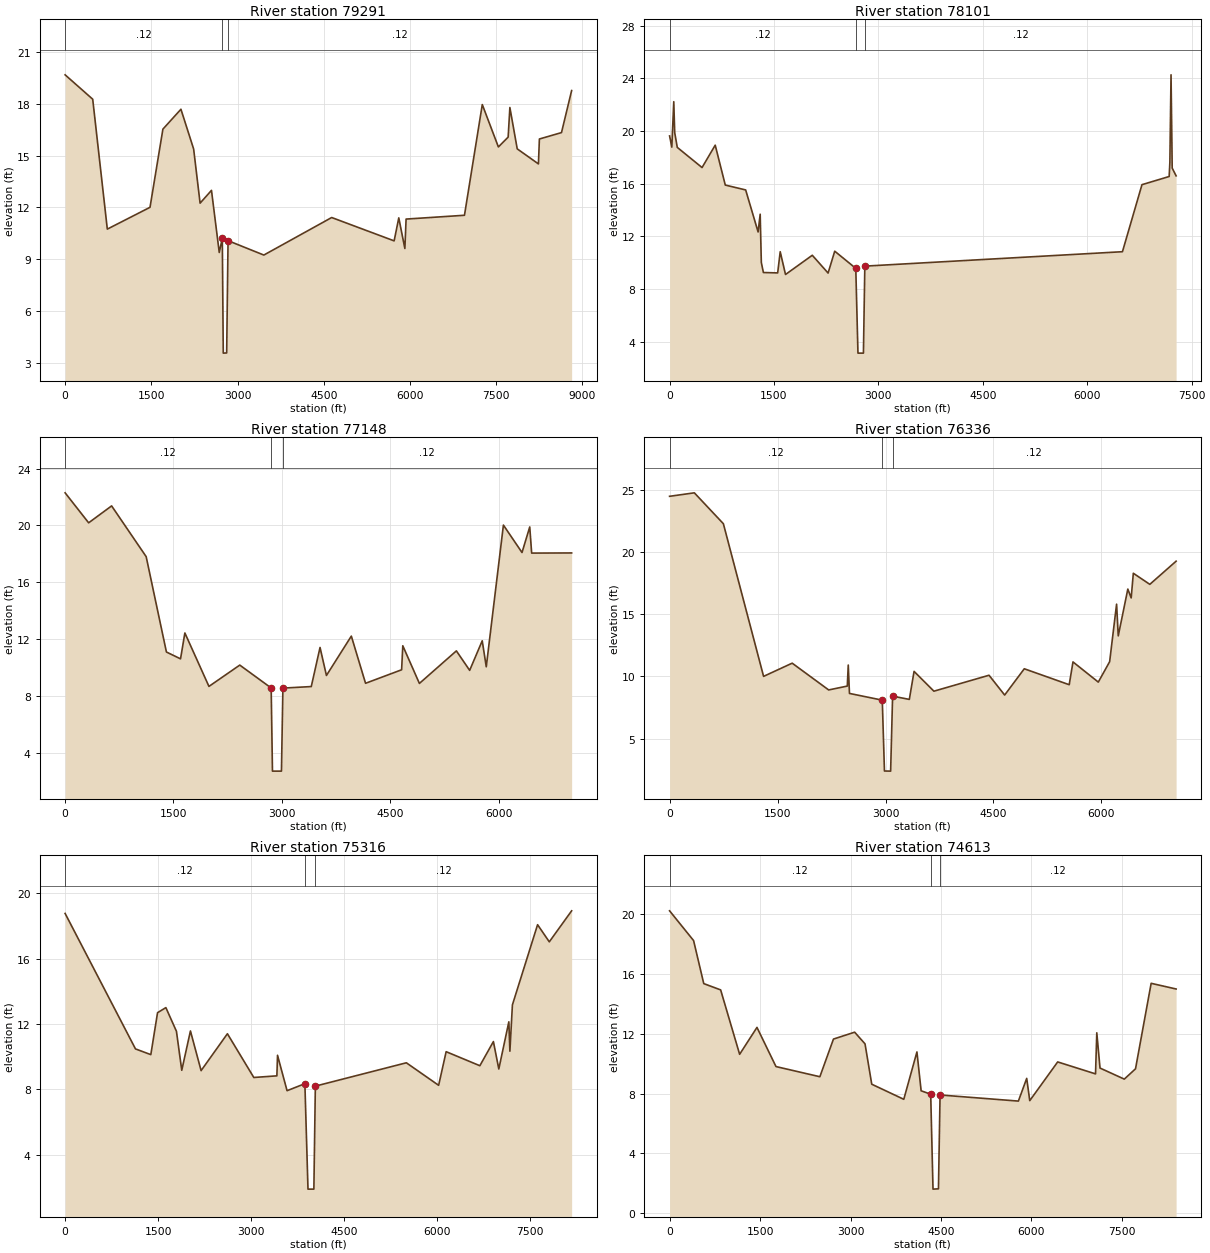
Type RM Length L Ch R = 1 ,79291   ,1190.2,1190.2,1190.2
XS GIS Cut Line= 4
2103719.85250626357044.0968831052100627.32658961357379.108622936
2095876.54498006358231.4916030132095024.16199999358432.052304208
#Sta/Elev= 30
       0   19.67   480.2   18.26   734.3   10.75  1477.1   12.01  1701.5   16.53
  2015.1   17.68  2236.3   15.38  2348.5   12.25  2546.6   12.99  2681.9     9.4
    273510.22525  2751.7    3.58 2810.91    3.59    283510.08146  3457.8    9.25
  4638.1   11.42  5724.7   10.07  5805.5    11.4  5911.4    9.63  5932.7   11.33
  6948.3   11.55  7258.4   17.95  7538.5    15.5  7708.5   16.07  7738.5   17.78
  7866.4   15.39  8235.3   14.52  8252.1   15.96  8636.5   16.338812.922   18.76
#Mann= 3 ,0,0
       0     .12       0    2735    .041       0    2835     .12       0
Bank Sta=2735,2835
XS Rating Curve= 0 ,0
Exp/Cntr(USF)=0,0
Exp/Cntr=0.3,0.1

Type RM Length L Ch R = 1 ,78101   ,952.8,952.8,952.8
XS GIS Cut Line= 6
2103484.77253227356585.643760793 2102409.3881305356342.559731688
2101850.75576887356271.4910918842101200.12087369356311.763392387
2097028.31291086356773.2007179292096279.54032397356915.172039683
#Sta/Elev= 30
       0   19.62    31.9   18.77      60   22.22    73.5   19.87   110.5   18.75
   466.4   17.22   655.5   18.92   800.2   15.89  1092.9   15.52  1271.7   12.33
  1301.5   13.68    1318   10.01  1347.8    9.25  1552.9    9.22  1589.3   10.83
  1665.4     9.1  2050.1   10.56    2277    9.21  2372.6   10.87    26759.566566
 2706.35    3.13 2784.84    3.13    28059.734908  6506.2   10.83  6786.7   15.92
  7177.5   16.54  7187.5   17.61  7204.2   24.26  7220.9   17.18  7277.1   16.59
#Mann= 3 ,0,0
       0     .12       0    2675    .041       0    2805     .12       0
Bank Sta=2675,2805
XS Rating Curve= 0 ,0
Exp/Cntr(USF)=0,0
Exp/Cntr=0.3,0.1

Type RM Length L Ch R = 1 ,77148   ,811.4,811.4,811.4
XS GIS Cut Line= 6
2103563.33853893356122.9023916632102439.46191877355741.479447767
2100828.15808317355532.0491173452099585.11723442355535.141277814
2097678.49577922355601.6040459542096639.78637301355746.062602483
#Sta/Elev= 30
       0   22.29   325.8   20.18   643.8   21.37  1122.1    17.8  1402.5   11.09
  1597.9   10.61  1657.9   12.43  1991.3    8.67  2417.9   10.17 2852.64    8.56
 2870.41    2.71 2994.83    2.71    30158.550438  3407.7    8.66  3529.1   11.41
  3617.7    9.44  3962.3   12.21  4159.2    8.89  4658.4    9.84  4674.8   11.53
  4904.7    8.88  5416.6   11.17  5600.5     9.8  5774.5   11.88  5830.3   10.05
  6067.7   20.02  6325.2   18.09  6432.2   19.89  6458.7   18.05  7012.1   18.06
#Mann= 3 ,0,0
       0     .12       0 2852.64    .041       0    3015     .12       0
Bank Sta=2852.64,3015
XS Rating Curve= 0 ,0
Exp/Cntr(USF)=0,0
Exp/Cntr=0.3,0.1

Type RM Length L Ch R = 1 ,76336   ,1021,1021,1021
XS GIS Cut Line= 6
2103682.61513281355697.0549044052102284.70829131355122.464937907
2100677.49266574354792.8194410942099999.66209378354803.752192255
2097708.15364479354935.6286455442096807.74356719 355079.52451163
#Sta/Elev= 30
       0   24.47   343.8   24.75   747.2   22.27  1305.9   10.01  1703.3   11.07
  2210.3    8.92  2468.9    9.23  2482.3   10.92  2499.1    8.64    29558.099456
 2985.25    2.41 3071.13     2.4 3098.528.422089  3330.9    8.16  3396.7   10.41
  3672.3    8.82  4438.2    10.1  4655.3    8.51  4928.1   10.62  5552.2    9.34
  5604.7   11.17  5956.4    9.55  6114.1   11.19  6210.4   15.81  6233.6   13.26
  6366.6   17.02  6413.3   16.31    6443   18.29  6672.3    17.4  7037.4   19.26
#Mann= 3 ,0,0
       0     .12       0    2955    .041       0 3098.52     .12       0
Bank Sta=2955,3098.52
XS Rating Curve= 0 ,0
Exp/Cntr(USF)=0,0
Exp/Cntr=0.3,0.1

Type RM Length L Ch R = 1 ,75316   ,702.4,702.4,702.4
XS GIS Cut Line= 6
2104580.48483008 355241.062238682101661.80877761353965.224877458
2101171.16157919353868.206247267 2100082.3226075354092.234792296
2097823.82905937354594.7347783322096794.35129549 354866.19170869
#Sta/Elev= 30
       0   18.77  1135.9   10.47  1383.4   10.12    1492   12.69  1626.4      13
  1796.9   11.55  1882.8    9.16  2022.9   11.57    2195    9.14  2619.6    11.4
  3045.7    8.72    3418    8.82  3428.5   10.08  3582.4    7.91    3870 8.34008
 3920.28    1.88 4015.14    1.88 4039.05    8.19  5507.9    9.62    6029    8.24
  6150.1    10.3  6694.3    9.44  6912.9   10.92  7000.3    9.24  7162.1   12.13
  7179.1   10.33  7219.8   13.17    7626   18.08  7815.1   17.03  8175.6   18.93
#Mann= 3 ,0,0
       0     .12       0    3870    .041       0 4039.05     .12       0
Bank Sta=3870,4039.05
XS Rating Curve= 0 ,0
Exp/Cntr(USF)=0,0
Exp/Cntr=0.3,0.1

Type RM Length L Ch R = 1 ,74613   ,1313.4,1313.4,1313.4
XS GIS Cut Line= 6
2104641.45660154354877.0331971342101692.11568816353517.983834757
2100893.78222901353339.0597686792099760.68197156  353489.0289204
2098619.17759005 353758.006675212096722.45335365354443.507094647
#Sta/Elev= 30
       0   20.23     398   18.24   566.7   15.36   846.7   14.94  1161.5   10.63
    1449   12.43  1764.3    9.81  2491.9    9.13  2717.6   11.65  3068.8   12.11
  3240.8   11.33  3352.3    8.63  3883.7    7.62  4101.7   10.79  4171.3    8.19
    43307.960487 4368.31    1.61 4458.54    1.63 4485.35    7.91    5784     7.5
  5922.2    9.02  5972.8    7.53  6435.8   10.12  7063.4    9.32  7084.3   12.07
  7137.8    9.71  7540.5    8.97  7726.5    9.66  7985.9   15.38  8399.6      15
#Mann= 3 ,0,0
       0     .12       0    4330    .041       0 4485.35     .12       0
Bank Sta=4330,4485.35
XS Rating Curve= 0 ,0
Exp/Cntr(USF)=0,0
Exp/Cntr=0.3,0.1

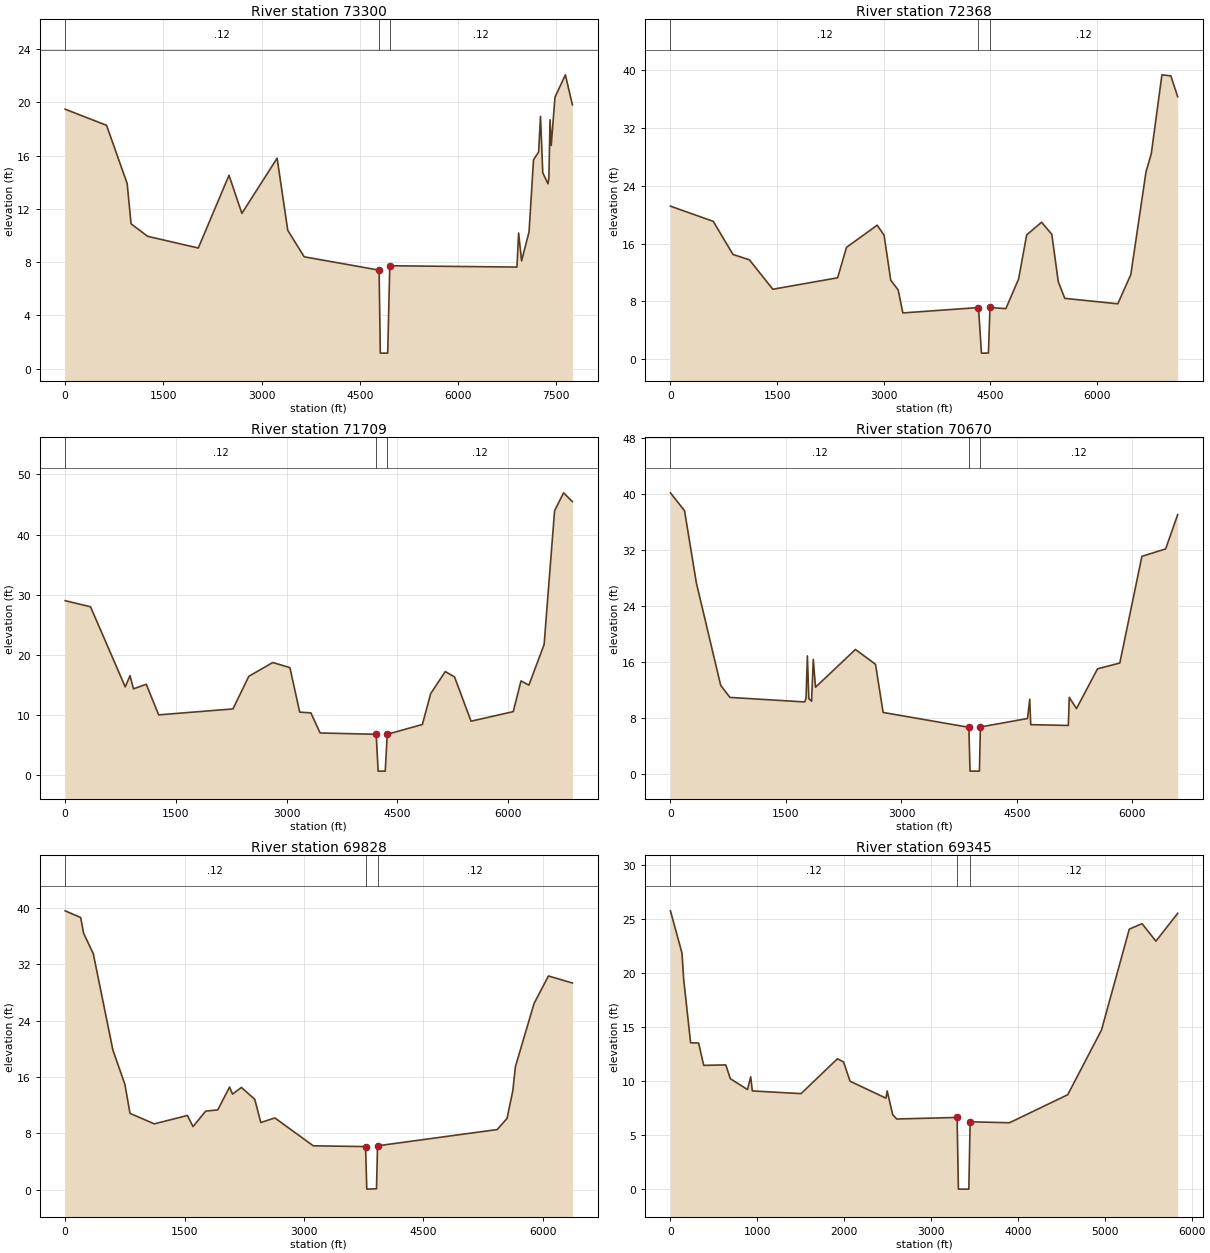
Type RM Length L Ch R = 1 ,73300   ,932,932,932
XS GIS Cut Line= 6
2104500.83237574354502.2540987692102059.37782849353224.823799985
2100860.60817398352609.7235453542100308.18738998352348.740765757
2099630.38953622351822.9891955322098164.55244227350216.185473509
#Sta/Elev= 30
       0   19.48   632.4   18.27   947.2    13.9  1006.5   10.88  1258.3    9.94
  2033.5    9.06  2502.8   14.52  2699.1   11.66  3237.4    15.8  3399.9   10.39
  3650.8     8.4  4794.8     7.4 4813.52    1.17  4926.2    1.17  4958.17.728683
  6900.1    7.63  6925.6   10.19  6971.1     8.1  7085.2   10.27  7153.2   15.68
  7231.3   16.27  7259.9   18.94  7294.6   14.71  7374.6   13.88  7387.9   14.32
  7405.7   18.69  7423.5   16.76  7481.2   20.38  7639.7   22.06  7747.3   19.81
#Mann= 3 ,0,0
       0     .12       0  4794.8    .041       0  4958.1     .12       0
Bank Sta=4794.8,4958.1
XS Rating Curve= 0 ,0
Exp/Cntr(USF)=0,0
Exp/Cntr=0.3,0.1

Type RM Length L Ch R = 1 ,72368   ,659,659,659
XS GIS Cut Line= 4
2104436.01786635354160.1425241452102459.03756485352876.263836931
2100652.50396726351583.2095389232098728.33976301 349899.56586021
#Sta/Elev= 30
       0   21.16   602.7   19.06   879.8   14.49  1111.3   13.75  1440.2    9.69
  2351.7   11.27  2476.7   15.47  2908.5   18.53  3005.4   17.15  3099.1   10.94
  3203.1     9.6  3269.6    6.42  4333.2    7.16 4375.27     .87 4473.31     .88
    44957.172149  4718.3    7.01  4897.7    11.1  5011.1   17.19  5220.8   18.94
  5364.8   17.27  5455.9   10.72  5547.5    8.43  6293.2    7.68  6476.3   11.71
    6690   25.91  6764.2   28.39  6913.8   39.29  7038.9   39.15  7135.7   36.27
#Mann= 3 ,0,0
       0     .12       0  4333.2    .041       0    4495     .12       0
Bank Sta=4333.2,4495
XS Rating Curve= 0 ,0
Exp/Cntr(USF)=0,0
Exp/Cntr=0.3,0.1

Type RM Length L Ch R = 1 ,71709   ,1039,1039,1039
XS GIS Cut Line= 5
 2104668.4043109353865.4570101392103846.66691624353225.991559639
2102131.87292103351894.7699054612101242.87252992351244.294252948
 2099285.9100722349593.448827716
#Sta/Elev= 30
       0   29.01   343.8   27.99   814.2   14.66   879.3   16.53   925.7   14.34
  1099.2    15.1  1267.3   10.01  2274.1      11  2488.7   16.42  2812.8   18.72
  3045.5   17.87  3178.6   10.47  3329.6   10.34  3455.6       7    42156.777931
 4241.53     .65 4337.39     .65    43656.781381  4840.6    8.41  4953.4   13.54
    5151   17.22  5276.8   16.32  5500.4    8.96  6072.3   10.55  6177.1   15.66
  6284.4   14.96  6490.5   21.72  6632.2   43.97  6754.4   46.95  6873.9   45.49
#Mann= 3 ,0,0
       0     .12       0    4215    .041       0    4365     .12       0
Bank Sta=4215,4365
XS Rating Curve= 0 ,0
Exp/Cntr(USF)=0,0
Exp/Cntr=0.3,0.1

Type RM Length L Ch R = 1 ,70670   ,842,842,842
XS GIS Cut Line= 3
2104785.08390592353190.3239595122101855.10659491350457.136169394
2099777.88387442348926.551006928
#Sta/Elev= 30
       0   40.19   183.1   37.64   336.3   27.32   652.1   12.66   772.2   10.92
  1742.9   10.27  1760.9   10.82  1778.3   16.86    1797   10.74  1832.7   10.38
  1855.1   16.38  1883.6   12.38  2402.9   17.78    2663   15.66  2761.7    8.77
    38756.639429 3890.62    .372 4012.31    .372    40256.689871  4636.9     7.9
  4665.5   10.67  4678.7    7.02  5166.9    6.91  5179.1   10.92  5272.9    9.32
    5546   15.01  5835.4   15.84  6122.2    31.1  6430.6   32.17  6587.1   37.07
#Mann= 3 ,0,0
       0     .12       0    3875    .041       0    4025     .12       0
Bank Sta=3875,4025
XS Rating Curve= 0 ,0
Exp/Cntr(USF)=0,0
Exp/Cntr=0.3,0.1

Type RM Length L Ch R = 1 ,69828   ,483.1,483.1,483.1
XS GIS Cut Line= 3
2105036.53718261352753.0139130932102423.60965525349877.700357889
2100444.78169521348368.980697743
#Sta/Elev= 30
       0   39.62     195   38.67   231.7   36.44   353.6   33.53   599.9   19.85
   751.3   14.96   814.7   10.86  1120.3    9.37    1537   10.56  1606.4    8.98
  1766.1   11.18  1917.6   11.35  2065.9    14.6    2103   13.59  2214.6   14.54
  2382.4   12.86  2458.5    9.56  2635.1   10.21    3118    6.25    37756.143803
 3789.86      .1 3912.11     .15    39256.251347  5428.5    8.56  5552.2   10.14
  5624.8   14.06  5657.6    17.5  5891.7   26.46  6072.6   30.37  6373.6   29.37
#Mann= 3 ,0,0
       0     .12       0    3775    .041       0    3925     .12       0
Bank Sta=3775,3925
XS Rating Curve= 0 ,0
Exp/Cntr(USF)=0,0
Exp/Cntr=0.3,0.1

Type RM Length L Ch R = 1 ,69345   ,535.9,535.9,535.9
XS GIS Cut Line= 3
2105016.33473616351978.5532578462102532.84558371349346.594645189
2100845.69262688347902.391714141
#Sta/Elev= 30
       0   25.76     133   21.84   152.1   19.44   232.3   13.53   324.3   13.51
   383.2   11.44   637.4   11.48   689.7    10.2     887     9.2   924.2   10.38
   942.7    9.07  1503.8    8.82  1922.4   12.05  1993.2   11.75  2067.8    9.97
  2480.9     8.4  2495.3    9.07  2558.6    6.87  2605.2    6.47    33006.612388
    3315    -.03    3435    -.03    34506.212595  3902.8    6.12  4573.7    8.72
  4962.6   14.72  5282.2   24.06  5429.1   24.57  5588.9   22.95  5839.5   25.53
#Mann= 3 ,0,0
       0     .12       0    3300    .041       0    3450     .12       0
Bank Sta=3300,3450
XS Rating Curve= 0 ,0
Exp/Cntr(USF)=0,0
Exp/Cntr=0.3,0.1

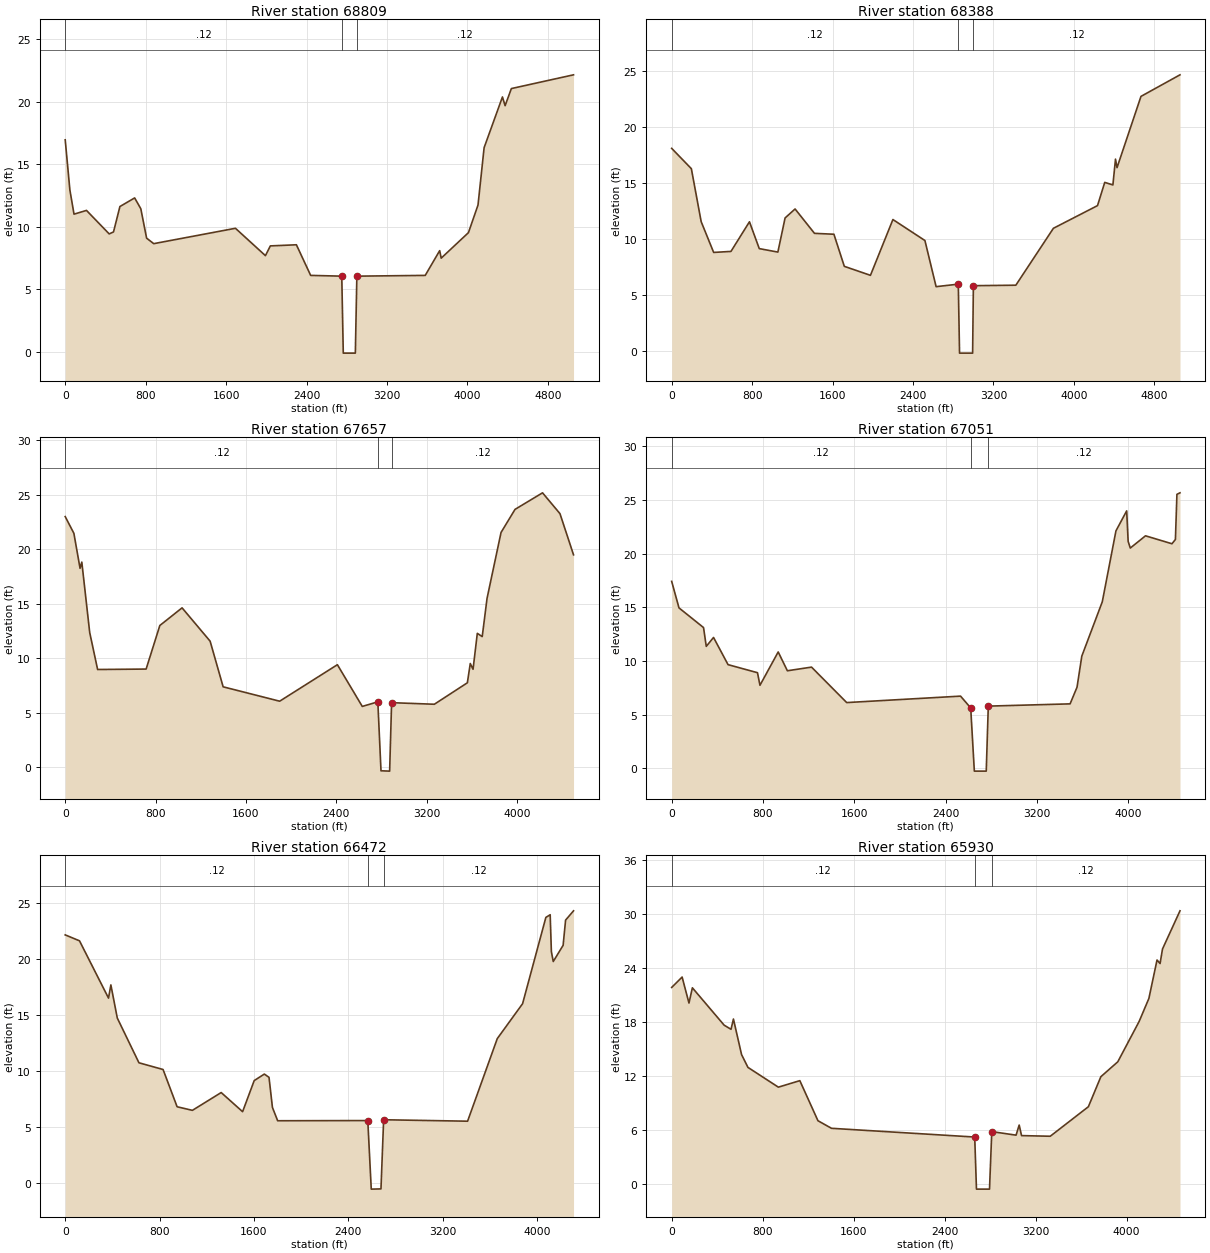
Type RM Length L Ch R = 1 ,68809   ,421.1,421.1,421.1
XS GIS Cut Line= 5
2104919.42897314351202.4621204592102931.07946149349007.530841367
2101969.18310683348174.7480913592101762.60133939347955.733161985
2101408.81412269347575.326226796
#Sta/Elev= 30
       0   16.96    46.6   12.94    87.6   11.01   211.6   11.31   437.4    9.43
   480.4    9.59     544   11.62   690.6   12.31   751.9   11.44   809.4    9.09
   880.3    8.65  1692.7    9.88  1990.9    7.69  2039.8    8.47  2298.9    8.56
  2440.6    6.11    27506.049471    2765    -.11    2885    -.11    29006.049471
  3579.8    6.11  3723.6    8.09  3738.7    7.49  4009.5    9.53  4104.7   11.74
  4165.4   16.33  4347.7   20.39  4374.2   19.69  4436.3   21.06  5054.5   22.16
#Mann= 3 ,0,0
       0     .12       0    2750    .041       0    2900     .12       0
Bank Sta=2750,2900
XS Rating Curve= 0 ,0
Exp/Cntr(USF)=0,0
Exp/Cntr=0.3,0.1

Type RM Length L Ch R = 1 ,68388   ,730.7,730.7,730.7
XS GIS Cut Line= 5
2105200.84078447350906.7282358382103212.49127282348711.796956746
2102250.59491816347879.0142067382102044.01315072347659.999277365
2101690.22593402347279.592342175
#Sta/Elev= 30
       0   18.07   195.7   16.26   293.4   11.54   417.5     8.8   589.5    8.89
   773.5   11.53   870.9    9.14    1056    8.83  1127.7   11.87  1227.1   12.67
    1420    10.5  1613.3   10.42  1716.7    7.56  1976.6    6.76  2199.9   11.73
  2518.2    9.86  2629.4    5.75    28505.973382 2862.49    -.17  2992.5    -.17
    30005.837326  3422.2    5.88  3795.8   10.95  4234.3   12.97  4306.3   15.04
  4387.3   14.81  4413.1   17.11  4428.4   16.35  4666.6    22.7  5054.5   24.62
#Mann= 3 ,0,0
       0     .12       0    2850    .041       0    3000     .12       0
Bank Sta=2850,3000
XS Rating Curve= 0 ,0
Exp/Cntr(USF)=0,0
Exp/Cntr=0.3,0.1

Type RM Length L Ch R = 1 ,67657   ,605.7,605.7,605.7
XS GIS Cut Line= 6
2105451.07381229350530.1259079532105264.97539394350287.841441331
2105110.69420985 350033.553074562103802.92056539348320.054379324
2103460.76951306347952.0806060652102508.91532765347158.908634768
#Sta/Elev= 30
       0   23.01    76.9   21.47   131.5   18.26     147   18.83     217   12.36
     287    8.97   716.3    9.01   837.7   13.01  1034.6   14.63  1282.9   11.57
  1398.1    7.38  1898.5    6.06  2409.6    9.41  2629.9    5.58  2767.5       6
 2795.61    -.33 2872.13    -.362889.3975.924609    3268    5.78  3560.2    7.75
  3585.9    9.52  3610.5    8.99  3648.2   12.29  3691.7   11.99  3734.4    15.5
  3858.3   21.55  3982.1   23.67  4225.6   25.19  4379.9   23.28    4500    19.5
#Mann= 3 ,0,0
       0     .12       0  2767.5    .041       02889.397     .12       0
Bank Sta=2767.5,2889.397
XS Rating Curve= 0 ,0
Exp/Cntr(USF)=0,0
Exp/Cntr=0.3,0.1

Type RM Length L Ch R = 1 ,67051   ,579.5,579.5,579.5
XS GIS Cut Line= 6
2105909.72849235350087.8721371012105579.00780553 349605.21654921
2105023.86638157348925.1271643062104262.09611412347937.408088715
2103919.94506179347569.4343154562102968.09087638346776.262344159
#Sta/Elev= 30
       0   17.41    64.2   14.94   279.1   13.11     303   11.36   366.7   12.19
   493.7    9.66   751.5    8.91   773.3    7.74   932.9   10.84  1013.4    9.09
  1224.8    9.43  1532.9    6.13  2529.9    6.73  2618.9    5.63  2650.7    -.25
 2754.93    -.25 2772.91     5.8  3489.3    6.01    3550    7.56  3591.8   10.45
  3771.3   15.51  3890.9   22.11  3984.9   23.97  3997.7   21.13  4016.5   20.51
  4149.8   21.65  4381.4   20.91  4411.7   21.31  4424.9   25.51  4451.8   25.65
#Mann= 3 ,0,0
       0     .12       0  2618.9    .041       0 2772.91     .12       0
Bank Sta=2618.9,2772.91
XS Rating Curve= 0 ,0
Exp/Cntr(USF)=0,0
Exp/Cntr=0.3,0.1

Type RM Length L Ch R = 1 ,66472   ,541.8,541.8,541.8
XS GIS Cut Line= 6
2106260.49878914349680.3857755222106014.05120195 349298.24870406
2105472.10917914348564.3463760172104710.33891169347576.627300427
2104368.18785936347208.6535271672103548.32768542346344.407857385
#Sta/Elev= 30
       0   22.18   121.1   21.65   367.1   16.53     387   17.71   441.4   14.75
     625   10.75   829.4   10.15   948.4    6.82    1078     6.5  1321.9    8.09
  1503.5    6.38  1601.8    9.16  1687.8    9.74  1727.3    9.45  1756.3    6.76
  1800.6    5.572564.3975.587436 2593.82    -.54 2676.09    -.52 2698.72    5.66
  3410.2    5.53  3661.9   12.91  3876.3   16.03  4073.6   23.74  4110.2   23.98
  4120.4   20.68  4136.3    19.8  4219.9   21.25  4240.8    23.5  4308.1   24.33
#Mann= 3 ,0,0
       0     .12       02564.397    .041       0 2698.72     .12       0
Bank Sta=2564.397,2698.72
XS Rating Curve= 0 ,0
Exp/Cntr(USF)=0,0
Exp/Cntr=0.3,0.1

Type RM Length L Ch R = 1 ,65930   ,761.5,761.5,761.5
XS GIS Cut Line= 6
2106639.91538697349455.4434211342106352.85425779348941.312338199
2105861.67916247348197.2566246582105099.90889502347209.537549068
2104757.75784269346841.5637758082103805.90365728346048.391804512
#Sta/Elev= 30
       0   21.83    91.9   22.98   152.1    20.1   182.1   21.79   461.3   17.65
   521.9   17.19     543   18.33   614.5   14.39   670.6   12.97     938   10.78
  1126.8    11.5  1286.1    7.06  1405.3    6.222664.3975.251529 2679.74    -.52
 2794.45    -.522814.3975.853982  3027.9    5.46  3055.4    6.58  3076.1    5.41
  3328.5    5.34  3663.6    8.61  3773.6   11.94  3922.3   13.59  4110.3   18.07
  4195.7   20.61  4267.2   24.87    4294   24.48  4315.4   26.09  4469.2   30.32
#Mann= 3 ,0,0
       0     .12       02664.397    .041       02814.397     .12       0
Bank Sta=2664.397,2814.397
XS Rating Curve= 0 ,0
Exp/Cntr(USF)=0,0
Exp/Cntr=0.3,0.1