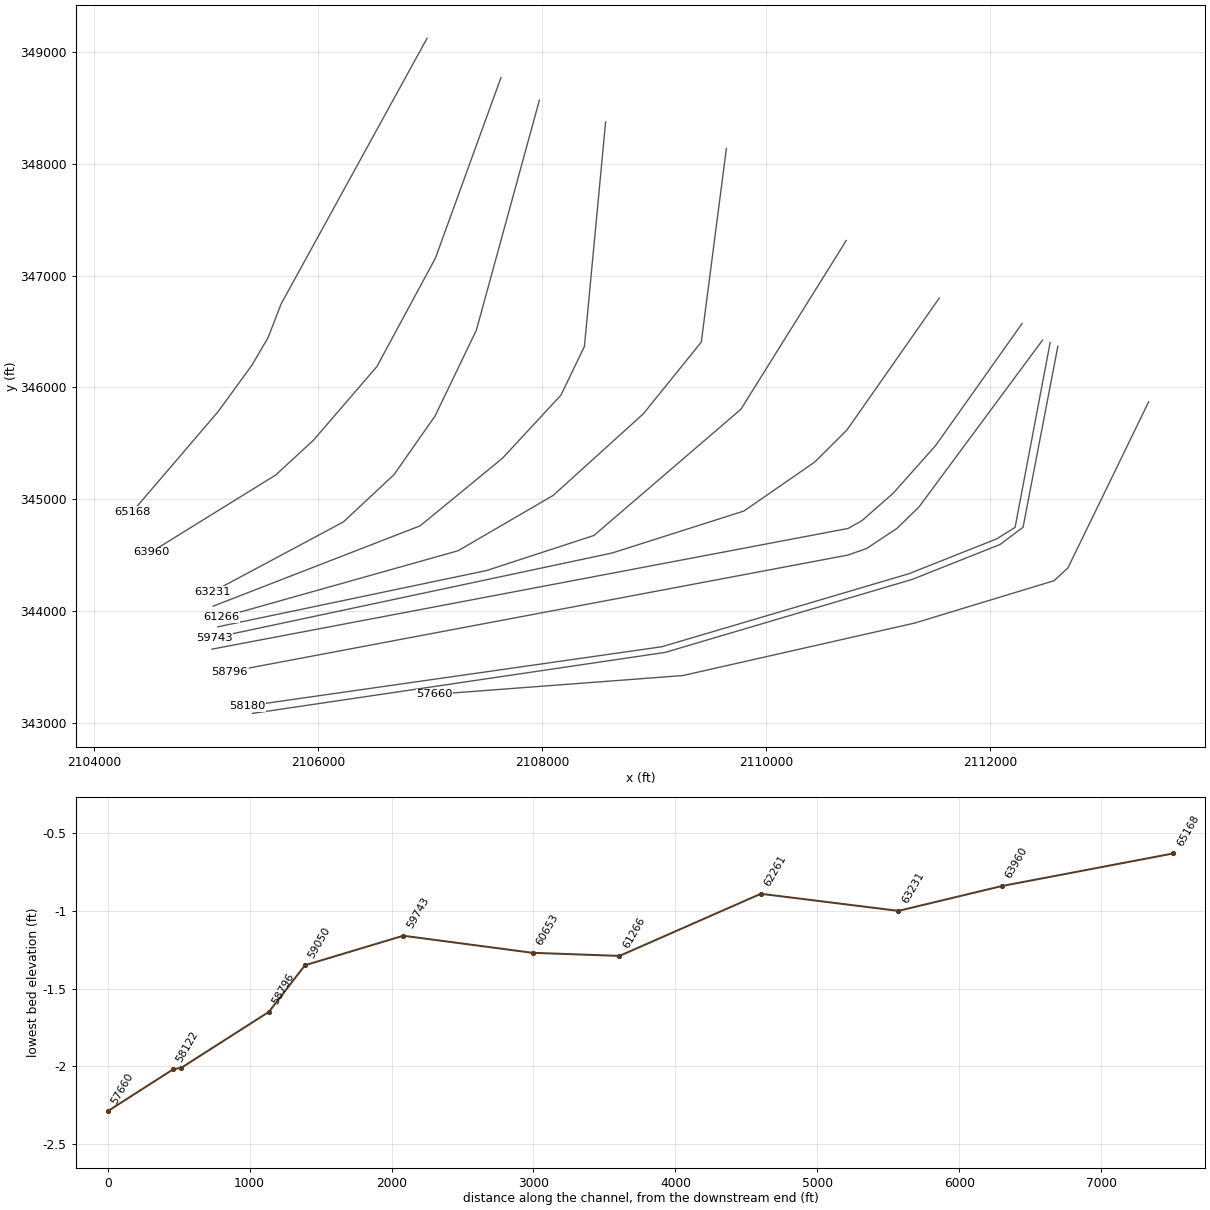
HEC-RAS study AshepooRiver.prj: S-15-41 over Ashepoo River

--- AshepooRiver.g03 (geometry) --- (continued)

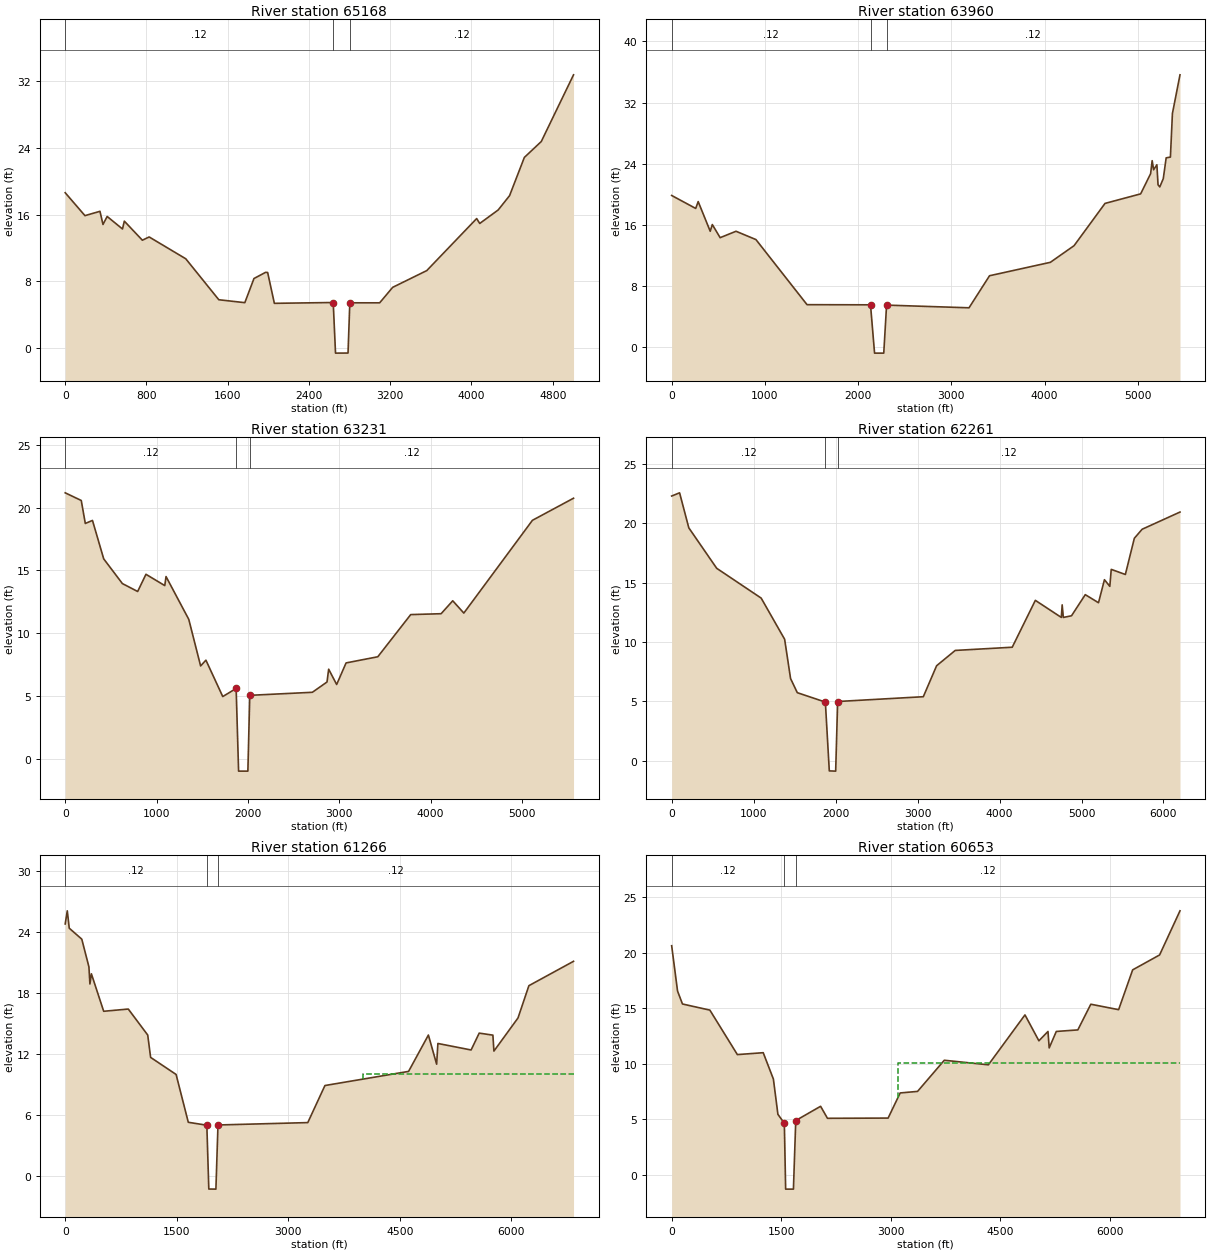
Type RM Length L Ch R = 1 ,65168   ,1208.3,1208.3,1208.3
XS GIS Cut Line= 6
2106971.16762549349118.6353251632105668.00875549346744.728572319
2105552.85570614346446.1605709182105408.38327427346199.065693092
2105106.05692631345783.8167286512104341.20857382344889.364607303
#Sta/Elev= 30
       0   18.63   194.5   15.88   342.3    16.4   372.1   14.82   413.1   15.78
     564   14.28   582.2   15.22   759.7   12.93   826.8   13.32  1187.1    10.7
  1512.5    5.78  1768.7    5.43  1858.7    8.33  1972.9    9.07  1993.4    9.05
  2059.5    5.352639.0085.448291 2661.63    -.63 2784.71    -.62  2802.45.411972
  3096.3    5.41  3224.5    7.27    3560    9.28  4051.4   15.53  4081.6   14.94
  4263.1   16.56  4375.4   18.28  4520.9   22.87  4687.6   24.78  5005.2   32.79
#Mann= 3 ,0,0
       0     .12       02639.008    .041       0  2802.4     .12       0
Bank Sta=2639.008,2802.4
XS Rating Curve= 0 ,0
Exp/Cntr(USF)=0,0
Exp/Cntr=0.3,0.1

Type RM Length L Ch R = 1 ,63960   ,729.3,729.3,729.3
XS GIS Cut Line= 6
2107631.10497338348767.652928333 2107046.5754343347156.298112087
2106523.02960873346185.5518378322105958.50709774345530.207926267
2105621.25247013345218.5302854072104507.20787529  344528.6153287
#Sta/Elev= 30
       0   19.82   257.9   18.12   284.4   19.02   413.5   15.13     436   16.01
   519.8   14.29   690.2   15.13   903.8   14.04  1451.9    5.51 2132.67    5.49
 2176.17    -.84 2274.74    -.84    23055.451851  3189.2     5.1  3409.3     9.3
  4061.6   11.06  4315.9   13.24  4647.9   18.78  5030.1   20.03  5137.1   22.68
  5153.6   24.38    5169   23.19  5204.1   23.84  5216.6   21.22  5235.3   20.94
  5272.7   22.02  5303.8   24.75  5349.3   24.85  5370.8   30.56  5452.1   35.63
#Mann= 3 ,0,0
       0     .12       0 2132.67    .041       0    2305     .12       0
Bank Sta=2132.67,2305
XS Rating Curve= 0 ,0
Exp/Cntr(USF)=0,0
Exp/Cntr=0.3,0.1

Type RM Length L Ch R = 1 ,63231   ,969.4,969.4,969.4
XS GIS Cut Line= 6
2107974.03011954348566.1976154132107411.41057779 346511.09306813
2107043.38284408345745.963747439 2106676.2036752345220.885833417
2106224.69277549 344798.982205822105057.85128235344174.523806138
#Sta/Elev= 30
       0   21.17   175.7   20.56     220   18.73   298.5   18.97   421.4   15.91
   625.9   13.94   793.1   13.31   883.8   14.68  1089.8   13.78  1103.5    14.5
  1352.5   11.09  1482.1    7.38  1540.1    7.84  1724.3    4.94 1870.875.583691
 1897.71      -1 1999.23      -1    20205.037807    2705    5.28  2865.4     6.1
  2883.6    7.12    2971     5.9  3074.1    7.62  3421.2    8.11  3781.5   11.47
  4114.3   11.54  4241.5   12.57  4362.9   11.59  5113.6   18.98  5563.5   20.74
#Mann= 3 ,0,0
       0     .12       0 1870.87    .041       0    2020     .12       0
Bank Sta=1870.87,2020
XS Rating Curve= 0 ,0
Exp/Cntr(USF)=0,0
Exp/Cntr=0.3,0.1

Type RM Length L Ch R = 1 ,62261   ,995.7,995.7,995.7
XS GIS Cut Line= 6
2108565.32228052348371.6293052752108376.18519788346366.723367857
2108166.34421596345931.3629740592107645.84183687345368.922193977
2106910.35740571344764.4410710632105062.22230429344046.441724679
#Sta/Elev= 30
       0   22.29    96.6   22.56     209   19.61   549.5    16.2  1091.8   13.69
  1378.2   10.22  1450.5    6.91  1532.7    5.72    1875  4.9276 1923.02    -.87
 2000.65    -.89    2025 4.97617    3070    5.38  3232.1    7.99  3459.3    9.28
  4154.7    9.55  4436.8    13.5  4753.6   12.06  4763.9   13.12  4778.2   12.06
    4878    12.2  5045.8   13.98  5207.2    13.3  5279.7   15.24  5345.1   14.68
  5362.7   16.11  5534.7   15.68  5644.4   18.73  5739.4   19.49  6201.4   20.94
#Mann= 3 ,0,0
       0     .12       0    1875    .041       0    2025     .12       0
Bank Sta=1875,2025
XS Rating Curve= 0 ,0
Exp/Cntr(USF)=0,0
Exp/Cntr=0.5,0.3

Type RM Length L Ch R = 1 ,61266   ,612.6,612.6,612.6
XS GIS Cut Line= 6
2109643.36416889348136.061039782 2109419.2208664346405.377529302
2108901.83713806345764.4344459052108097.35273658345035.840382716
2107248.48796725344541.4190195852105134.72207127343946.508637072
#Sta/Elev= 30
       0   24.82    27.9   26.11    54.4    24.4   223.1   23.32   319.1   20.59
   332.4   18.91   352.2   19.91   517.7   16.22   848.6   16.44    1110   13.88
  1148.9   11.68  1491.6      10  1655.7    5.29    19055.002243 1931.73   -1.28
 2027.04   -1.29    20555.025343  3262.9    5.26  3493.7    8.91  4618.7    10.3
  4885.3   13.88  4996.1   11.01  5013.1   13.05  5459.7   12.41  5568.8   14.07
  5752.9   13.87  5766.6    12.3  6090.5   15.56  6237.1   18.74  6837.5   21.14
#Mann= 3 ,0,0
       0     .12       0    1905    .041       0    2055     .12       0
#XS Ineff= 2 , 0
                            4000           10.03
Permanent Ineff=
       F       F
Bank Sta=1905,2055
XS Rating Curve= 0 ,0
Exp/Cntr(USF)=0,0
Exp/Cntr=0.5,0.3

Type RM Length L Ch R = 1 ,60653   ,910.6,910.6,910.6
XS GIS Cut Line= 5
2110712.77288746347311.8579898082109773.11276474345805.532602232
2108460.91386474344677.8068074582107503.50920049344364.812564901
2105104.22212249343861.947563075
#Sta/Elev= 30
       0   20.62    80.6   16.54   148.1   15.38   523.3   14.83   900.1   10.83
  1254.4      11  1393.6    8.63  1455.5    5.46 1543.58    4.65 1561.55   -1.27
 1668.17   -1.27    17004.898249  2040.4    6.18  2134.4     5.1  2965.2    5.12
  3130.8    7.38  3368.8    7.52  3734.8   10.32  4339.1    9.91  4840.4    14.4
  5031.2   12.07  5155.6   12.91  5172.3   11.43  5269.6   12.91  5564.6   13.05
  5742.4   15.36  6123.4   14.87  6315.7   18.45  6684.6   19.79  6964.3   23.76
#Mann= 3 ,0,0
       0     .12       0 1543.58    .041       0    1700     .12       0
#XS Ineff= 2 , 0
                            3100           10.03
Permanent Ineff=
       F       F
Bank Sta=1543.58,1700
XS Rating Curve= 0 ,0
Exp/Cntr(USF)=0,0
Exp/Cntr=0.5,0.3

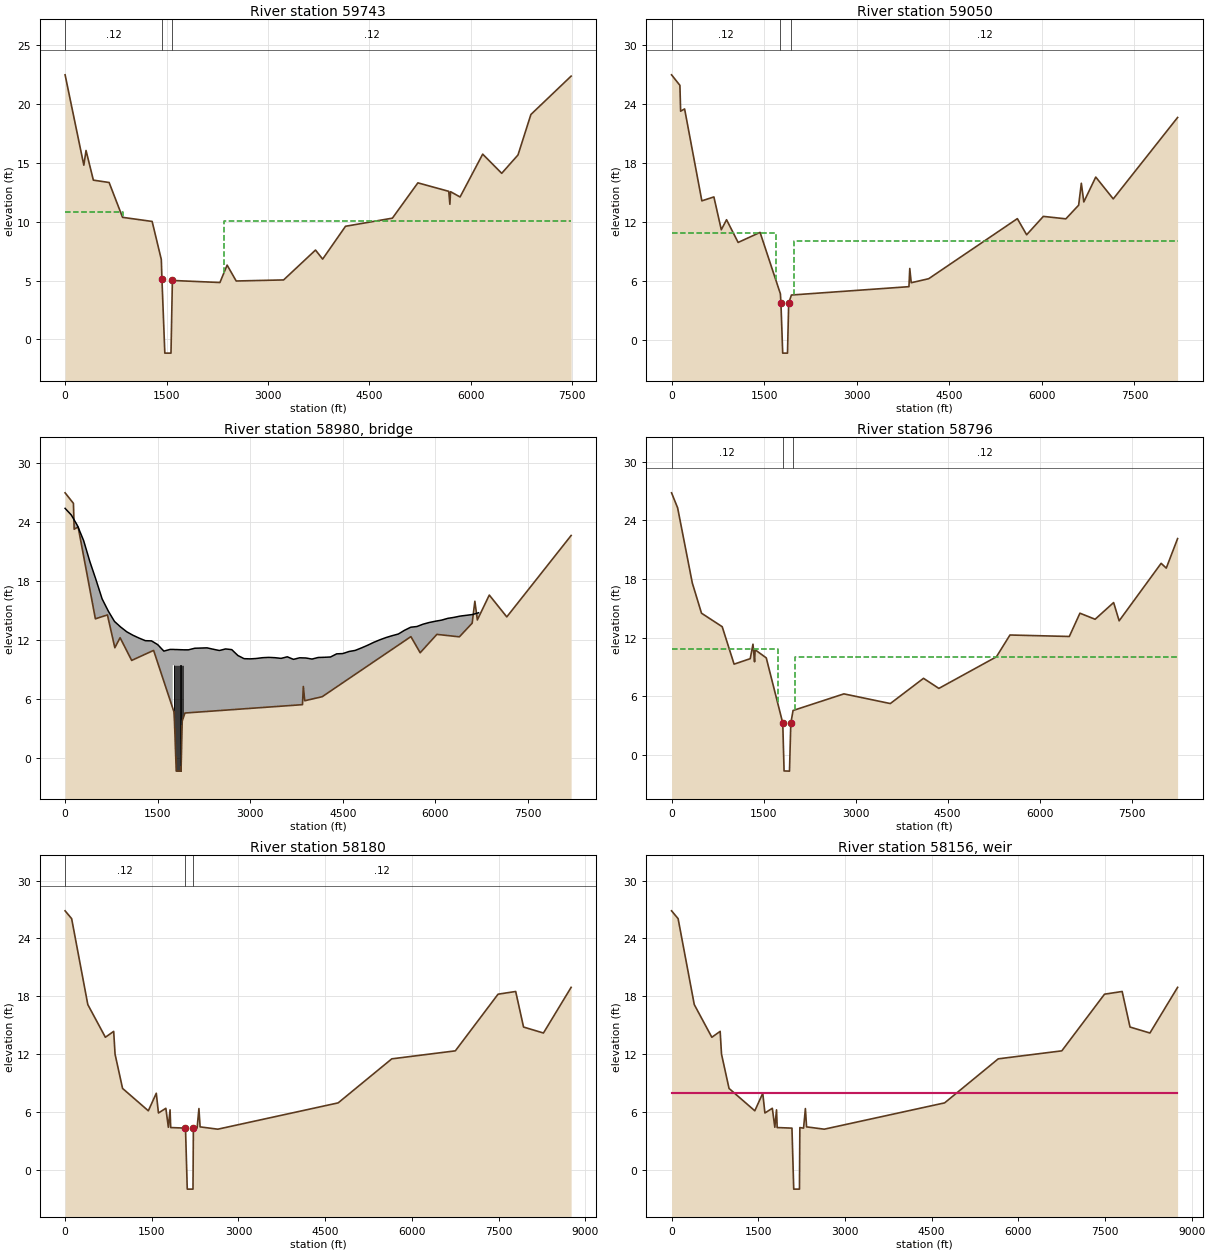
Type RM Length L Ch R = 1 ,59743   ,692.5,692.5,692.5
XS GIS Cut Line= 6
 2111543.9979528346799.4654006252110720.29886494345621.270508605
2110432.87640412345334.4647799842109800.23240003344896.283538183
2108623.27742312  344521.24242642105070.32233361343764.748045568
#Sta/Elev= 30
       0   22.49   277.2   14.81   309.7   16.06   418.2   13.54   651.1   13.34
   849.8   10.38  1287.4   10.03  1423.1    6.79 1432.21    5.13  1474.9   -1.16
 1566.09   -1.16  1586.85.015964  2289.7    4.84  2396.2    6.32  2530.4    4.97
  3231.5    5.06  3703.4     7.6  3808.9    6.83  4147.1    9.62  4840.5   10.31
  5217.1   13.31  5673.7   12.59  5690.5   11.49  5700.5   12.56  5841.1   12.11
  6175.8   15.75  6456.9   14.12  6697.9   15.68  6888.7   19.12  7483.6   22.38
#Mann= 3 ,0,0
       0     .12       0 1432.21    .041       0  1586.8     .12       0
#XS Ineff= 2 , 0
             850   10.87    2350           10.03
Permanent Ineff=
       F       F
Bank Sta=1432.21,1586.8
XS Rating Curve= 0 ,0
Exp/Cntr(USF)=0,0
Exp/Cntr=0.5,0.3

Type RM Length L Ch R = 1 ,59050   ,254.1,254.1,254.1
BEGIN DESCRIPTION:
HEC-2 RS: 218448
END DESCRIPTION:
XS GIS Cut Line= 6
2112282.70593525346571.0636307492111510.76004851345480.860592143
2111131.56207502345054.5707431452110853.32104535344810.025185703
2110729.34134793344740.5849727232105051.66105604343662.589639585
#Sta/Elev= 30
       0   26.96   135.3   25.89     147   23.26   211.4   23.49   490.8   14.14
   685.9   14.54     806    11.2   891.1   12.22  1078.6    9.91  1434.1   10.93
  1763.5    4.68 1772.133.742357  1800.8   -1.35 1878.42   -1.35 1897.79    3.75
    1942    4.56  3846.3    5.41  3859.6    7.26  3882.9    5.81  4166.1    6.22
  5602.5   12.33    5753   10.69  6023.8   12.56  6388.3   12.31  6595.6    13.7
    6639   15.93  6679.2   14.03  6872.8   16.56  7156.3   14.34  8198.7   22.62
#Mann= 3 ,-1,0
       0     .12       0  1763.5    .041       0    1942     .12       0
#XS Ineff= 2 , 0
            1687   10.87    1983           10.03
Permanent Ineff=
       F       F
Bank Sta=1772.13,1897.79
XS Rating Curve= 0 ,0
Exp/Cntr(USF)=0,0
Exp/Cntr=0.5,0.3

Type RM Length L Ch R = 3 ,58980   ,,,
BEGIN DESCRIPTION:
S-15-41 over Ashepoo River
END DESCRIPTION:
Bridge Culvert--1,0,-1,-1, 0
Deck Dist Width WeirC Skew NumUp NumDn MinLoCord MaxHiCord MaxSubmerge Is_Ogee
53.74202,100,2.6,0, 68, 68, , , 0.98, 0, 2,2,,
       0     100     200     300     400     500     600     700     800     900
    1000    1100    1200    1300    1400    1500    1600    1700    1744    1926
    2000    2100    2200    2300    2400    2500    2600    2700    2800    2900
    3000    3100    3200    3300    3400    3500    3600    3700    3800    3900
    4000    4100    4200    4300    4400    4500    4600    4700    4800    4900
    5000    5100    5200    5300    5400    5500    5600    5700    5800    5900
    6000    6100    6200    6300    6400    6500    6600    6700
   25.38   24.71   23.63   22.11   19.99   18.13   16.17   14.93   13.88   13.31
   12.82   12.47   12.18   11.92    11.9   11.52   10.86   11.03   11.03   10.99
   10.99   11.15   11.17   11.19   11.05   10.92   11.08   11.01   10.41   10.09
   10.07   10.11   10.19   10.22   10.19   10.12   10.28   10.02   10.18   10.16
   10.05   10.21   10.23   10.26   10.58   10.61   10.82   10.93   11.18   11.45
   11.75   12.01   12.24   12.43    12.6   12.98   13.29   13.36    13.6   13.77
    13.9   14.01   14.19   14.29   14.42    14.5   14.58   14.76
                                                                                
                                                                    9.43    9.43
                                                                                
                                                                                
                                                                                
                                                                                
                                                                
      41     141     241     341     441     541     641     741     841     941
    1041    1141    1241    1341    1441    1541    1641    1741    1785    1967
    2041    2141    2241    2341    2441    2541    2641    2741    2841    2941
    3041    3141    3241    3341    3441    3541    3641    3741    3841    3941
    4041    4141    4241    4341    4441    4541    4641    4741    4841    4941
    5041    5141    5241    5341    5441    5541    5641    5741    5841    5941
    6041    6141    6241    6341    6441    6541    6641    6741
   25.38   24.71   23.63   22.11   19.99   18.13   16.17   14.93   13.88   13.31
   12.82   12.47   12.18   11.92    11.9   11.52   10.86   11.03   11.03   10.99
   10.99   11.15   11.17   11.19   11.05   10.92   11.08   11.01   10.41   10.09
   10.07   10.11   10.19   10.22   10.19   10.12   10.28   10.02   10.18   10.16
   10.05   10.21   10.23   10.26   10.58   10.61   10.82   10.93   11.18   11.45
   11.75   12.01   12.24   12.43    12.6   12.98   13.29   13.36    13.6   13.77
    13.9   14.01   14.19   14.29   14.42    14.5   14.58   14.76
                                                                                
                                                                    9.43    9.43
                                                                                
                                                                                
                                                                                
                                                                                
                                                                
Pier Skew, UpSta & Num, DnSta & Num=  ,1758, 2 ,1799, 2 , 0 , 0 , 0 ,,
       1       1
   -1.65    9.69
       1       1
   -1.65    9.69
Pier Skew, UpSta & Num, DnSta & Num=  ,1772, 2 ,1813, 2 , 0 , 0 , 0 ,,
       1       1
   -1.65    9.69
       1       1
   -1.65    9.69
Pier Skew, UpSta & Num, DnSta & Num=  ,1786, 2 ,1827, 2 , 0 , 0 , 0 ,,
       1       1
   -1.65    9.69
       1       1
   -1.65    9.69
Pier Skew, UpSta & Num, DnSta & Num=  ,1800, 2 ,1841, 2 , 0 , 0 , 0 ,,
       1       1
   -1.65    9.69
       1       1
   -1.65    9.69
Pier Skew, UpSta & Num, DnSta & Num=  ,1814, 2 ,1855, 2 , 0 , 0 , 0 ,,
       1       1
   -1.65    9.69
       1       1
   -1.65    9.69
Pier Skew, UpSta & Num, DnSta & Num=  ,1828, 2 ,1869, 2 , 0 , 0 , 0 ,,
       1       1
   -1.65    9.69
       1       1
   -1.65    9.69
Pier Skew, UpSta & Num, DnSta & Num=  ,1842, 2 ,1883, 2 , 0 , 0 , 0 ,,
       1       1
   -1.65    9.69
       1       1
   -1.65    9.69
Pier Skew, UpSta & Num, DnSta & Num=  ,1856, 2 ,1897, 2 , 0 , 0 , 0 ,,
       1       1
   -1.65    9.69
       1       1
   -1.65    9.69
Pier Skew, UpSta & Num, DnSta & Num=  ,1870, 2 ,1911, 2 , 0 , 0 , 0 ,,
       1       1
   -1.65    9.69
       1       1
   -1.65    9.69
Pier Skew, UpSta & Num, DnSta & Num=  ,1884, 2 ,1925, 2 , 0 , 0 , 0 ,,
       1       1
   -1.65    9.69
       1       1
   -1.65    9.69
Pier Skew, UpSta & Num, DnSta & Num=  ,1898, 2 ,1939, 2 , 0 , 0 , 0 ,,
       1       1
   -1.65    9.69
       1       1
   -1.65    9.69
Pier Skew, UpSta & Num, DnSta & Num=  ,1912, 2 ,1953, 2 , 0 , 0 , 0 ,,
       1       1
   -1.65    9.69
       1       1
   -1.65    9.69
Abutment Skew #Up #Dn= , 3 , 3
    1744    1746 1752.46
    7.43    7.43     4.2
    1785    1787 1793.46
    7.43    7.43     4.2
Abutment Skew #Up #Dn= , 3 , 3
  1916.6    1924    1926
    3.73    7.43    7.43
  1957.6    1965    1967
    3.73    7.43    7.43
BR Coef=-1 ,-1 ,-1 ,0.9, 0 ,,,0.8,0,1.2,0,
WSPro=,,,, 1 ,,,, 0 ,,,, 0 ,,,,-1 ,-1 ,-1 , 0 , 0 , 0 , 0 , 0
BC Design=,, 0 ,, 0 ,,,,,,
BC Use User HTab Curves=0
BC User HTab FreeFlow(D)= 0

Type RM Length L Ch R = 1 ,58796   ,616.6,616.6,616.6
BEGIN DESCRIPTION:
HEC-2 RS: 218419
END DESCRIPTION:
XS GIS Cut Line= 6
2112465.11983619 346422.549297062111363.13655015344933.468875854
2111165.40341921344740.6376676242110893.85305968344560.725925455
2110725.69108737 344502.288003772105210.34691174343461.561526106
#Sta/Elev= 30
       0   26.81    98.7   25.28   338.2   17.59     488    14.5   825.3   13.12
  1019.1    9.29  1282.2    9.85  1326.9   11.33  1352.7    9.53  1362.2   10.76
  1543.5    9.93 1812.413.262738 1833.62   -1.63 1922.08   -1.65  1943.2    3.23
  1980.2    4.55  2808.6    6.25  3565.2    5.26  4106.1    7.84  4356.5    6.81
  5294.1   10.04    5515   12.27  6482.5   12.12  6655.3    14.5  6902.9   13.88
  7204.5   15.59  7294.5   13.72  7978.7    19.6  8062.5   19.11    8247   22.13
#Mann= 3 ,-1,0
       0     .12       0 1812.41    .041       0  1980.2     .12       0
#XS Ineff= 2 , 0
            1735   10.87    2017           10.03
Permanent Ineff=
       F       F
Bank Sta=1812.41,1943.2
XS Rating Curve= 0 ,0
Exp/Cntr(USF)=0,0
Exp/Cntr=0.5,0.3

Type RM Length L Ch R = 1 ,58180   ,57.8,57.8,57.8
BEGIN DESCRIPTION:
HEC-2 RS: 217655 (LTR N)
END DESCRIPTION:
Node Name=N
XS GIS Cut Line= 6
2112533.15905625346400.8927124982112220.07912493344749.760027028
2112055.98129461344647.4896658622111273.13088891 344336.30716421
2109066.92062286343683.8963280072105367.39154218343155.008802025
#Sta/Elev= 30
       0   26.87   113.3   26.06   393.2   17.14   697.2   13.75   840.9   14.36
   864.4      12   994.6    8.44  1440.4    6.12  1578.2    7.94  1615.4    5.89
  1743.6    6.38  1786.9    4.41  1816.3    6.22  1827.4    4.38 2083.48    4.32
 2113.92   -2.01 2213.14   -2.01    22204.374556  2284.3    4.32  2315.9    6.35
  2336.1    4.45  2642.3    4.21    4725    6.94  5652.9   11.51  6752.9   12.34
  7491.9   18.22  7797.1    18.5  7933.1   14.81  8277.4   14.19  8756.4   18.93
#Mann= 3 ,-1,0
       0     .12       0 2083.48    .041       0    2220     .12       0
Bank Sta=2083.48,2220
XS Rating Curve= 0 ,0
Exp/Cntr(USF)=0,0
Exp/Cntr=0.3,0.1

Type RM Length L Ch R = 5 ,58156   ,,,
IW Pilot Flow=0
#Inline Weir SE= 2
       0       88751.605       8
IW Dist,WD,Coef,Skew,MaxSub,Min_El,Is_Ogee,SpillHt,DesHd
14,16,2.6,0,0.98,, 0 ,,,2,2,
Inline Weir Flap Gates= 0
IW Outlet Rating Curve= 0 ,False,,

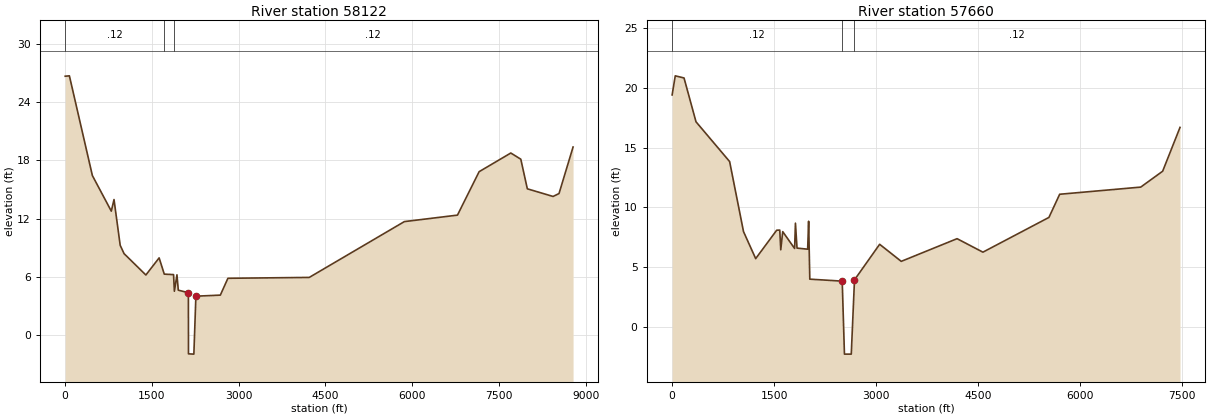
Type RM Length L Ch R = 1 ,58122   ,461.9,461.9,461.9
XS GIS Cut Line= 6
2112602.22771004346368.3947165712112291.51670559344751.338327519
 2112086.1399642 344597.12224529 2111303.2895585344285.939743638
2109097.07929245343633.5289074342105413.49016296343088.701430261
#Sta/Elev= 30
       0   26.71    72.8   26.75   470.2   16.44   797.5   12.76   844.3   13.96
   951.1    9.23  1017.9    8.37    1395    6.16  1624.2    7.93  1713.3    6.25
  1873.8     6.2    1888    4.48  1932.5    6.18  1955.7    4.59    2130    4.33
 2131.85   -1.99 2224.95   -2.02    2260    3.97  2682.7    4.08  2813.6    5.82
  4220.1    5.91  5864.6   11.68  6782.7   12.35  7157.2   16.84  7705.1   18.77
  7877.8   18.13  7990.7   15.07  8435.6   14.28  8538.5   14.58  8781.5   19.39
#Mann= 3 ,-1,0
       0     .12       0  1713.3    .041       0  1873.8     .12       0
Bank Sta=2130,2260
XS Rating Curve= 0 ,0
Exp/Cntr(USF)=0,0
Exp/Cntr=0.3,0.1

Type RM Length L Ch R = 1 ,57660   ,293.4,293.4,293.4
XS GIS Cut Line= 6
2113412.80357095345872.1360190542112692.51382011344389.192395445
2112568.93658486344274.0096954432111325.14543062343895.675353461
2109255.17654151343426.6027141322107037.10774411343258.632919787
#Sta/Elev= 30
       0   19.42      46   21.02   174.8   20.84   350.9   17.17     845   13.84
  1049.3    7.97  1228.1    5.71    1537    8.09    1582     8.1  1596.6    6.45
  1625.4    7.97  1800.2    6.56  1812.4    8.68  1835.5    6.59  1992.1     6.5
  2006.1    8.84  2023.5    3.99    2500 3.82269 2532.68   -2.29 2633.02   -2.29
 2680.38    3.93  3050.2    6.91  3367.6    5.48  4188.1    7.38    4568    6.25
  5538.3    9.16  5696.3    11.1  6887.7    11.7  7209.9   13.03  7465.1    16.7
#Mann= 3 ,-1,0
       0     .12       0    2500    .041       0 2680.38     .12       0
Bank Sta=2500,2680.38
XS Rating Curve= 0 ,0
Exp/Cntr(USF)=0,0
Exp/Cntr=0.3,0.1