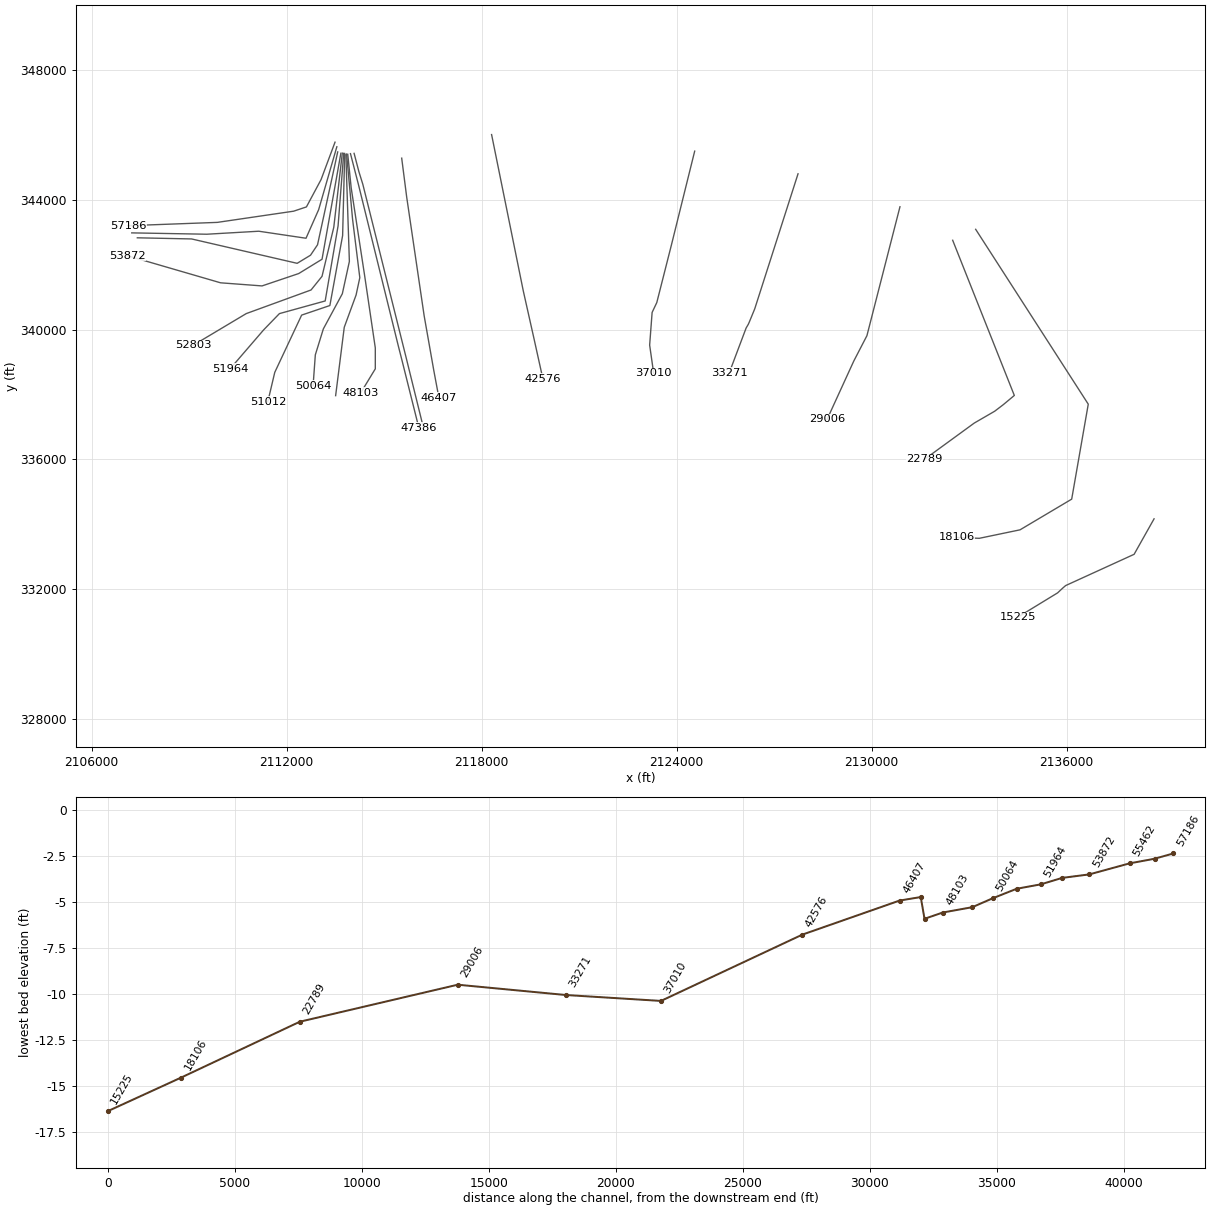
HEC-RAS study AshepooRiver.prj: S-15-41 over Ashepoo River

--- AshepooRiver.g03 (geometry) --- (continued)

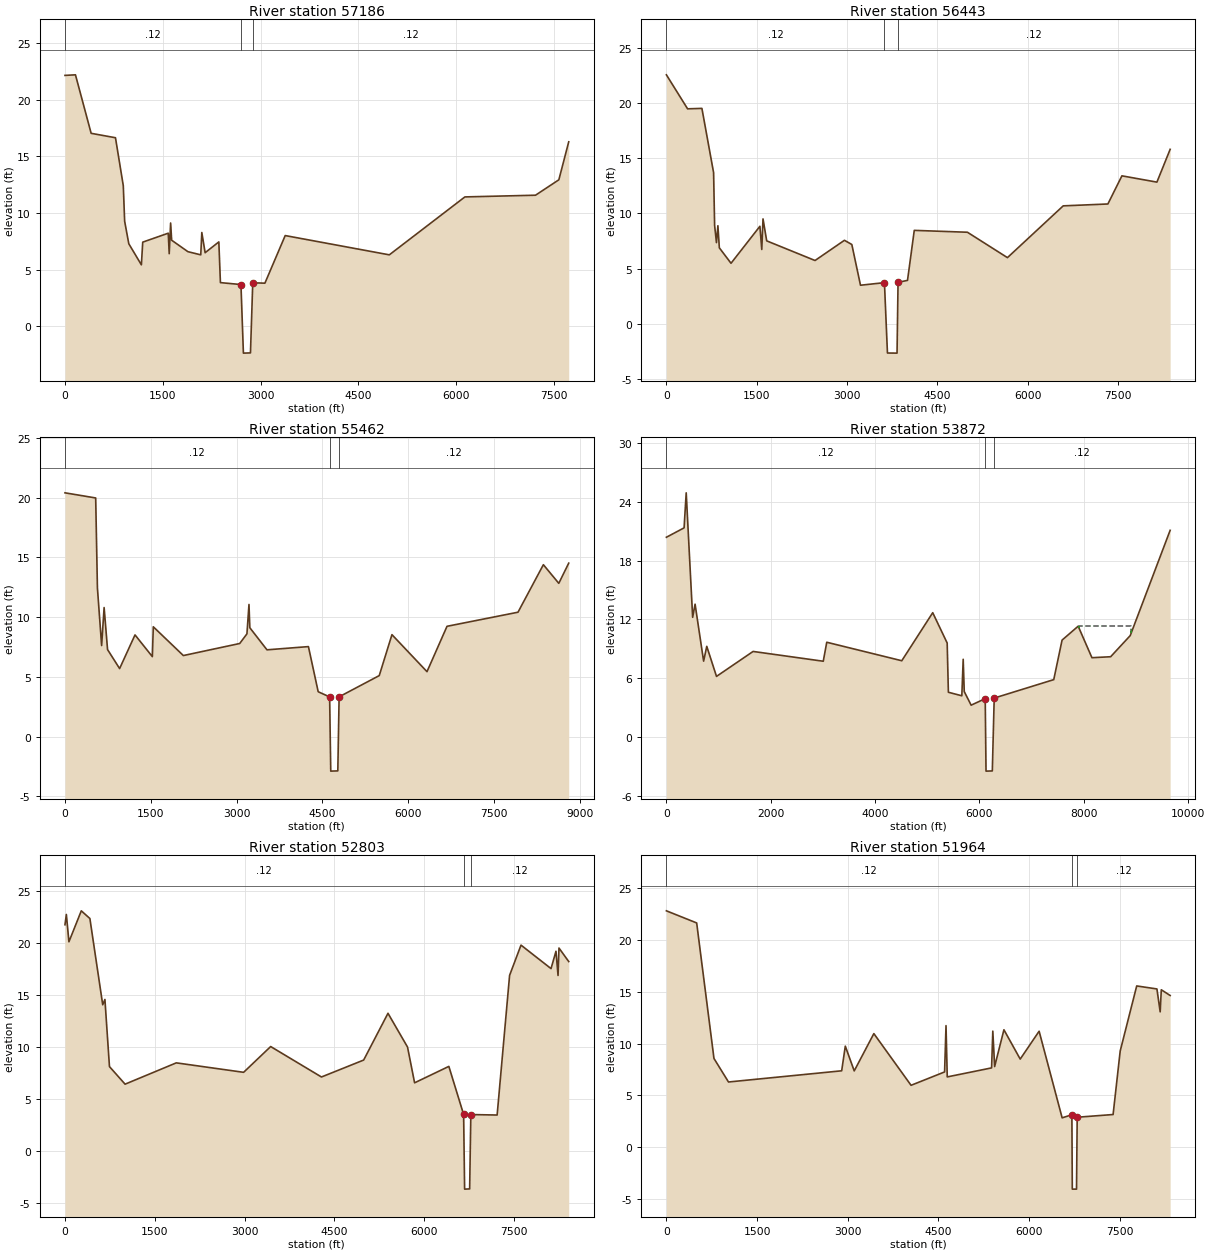
Type RM Length L Ch R = 1 ,57186   ,742.9,742.9,742.9
BEGIN DESCRIPTION:
HEC-2 RS: 216847
END DESCRIPTION:
XS GIS Cut Line= 6
2113486.58521938345768.4686934842113057.02499013344616.224982676
2112606.63455243343774.9088022842112213.00337047343643.294728209
2109864.08764517343298.3666103682107113.53128844343196.340419961
#Sta/Elev= 30
       0   22.14   160.9   22.19   401.6   17.03   774.8   16.64   894.7   12.41
   915.5    9.28     979    7.29  1172.3    5.43    1193    7.43  1584.5    8.22
  1599.4    6.41    1621    9.12  1636.7     7.6  1886.1    6.59  2083.4    6.31
  2099.5    8.28  2150.4     6.5  2360.7    7.45  2384.9    3.86    2700    3.69
 2737.58   -2.36 2846.02   -2.34 2881.093.846987  3067.5    3.81    3379    8.01
  4976.3    6.31  6136.1   11.42  7219.6   11.57  7577.5   12.93    7729   16.28
#Mann= 3 ,-1,0
       0     .12       0    2700    .041       0 2881.09     .12       0
Bank Sta=2700,2881.09
XS Rating Curve= 0 ,0
Exp/Cntr(USF)=0,0
Exp/Cntr=0.3,0.1

Type RM Length L Ch R = 1 ,56443   ,980.8,980.8,980.8
BEGIN DESCRIPTION:
HEC-2 RS: 215997
END DESCRIPTION:
XS GIS Cut Line= 6
 2113542.7384924345627.2632154992112982.60128618343689.622050567
2112594.04871233342810.1317107832111140.64623269343026.164538765
2109541.92443561342933.8618398392107232.32289834342975.171662578
#Sta/Elev= 30
       0   22.56   351.7   19.48   589.4   19.52   783.5    13.7   800.5    8.91
   831.1    7.36     855    8.89   878.8    6.89  1072.8    5.49  1552.4    8.84
  1583.5    6.74  1603.9    9.51  1665.2    7.52  2467.9    5.74  2955.8    7.57
  3078.6    7.19  3222.5     3.5    3620 3.73413 3669.99   -2.64 3829.28   -2.65
 3846.123.762544  4003.1    3.94  4115.4    8.47    4998     8.3  5662.3       6
  6588.3   10.69  7330.1   10.86  7563.1   13.41  8144.1   12.84  8363.9   15.81
#Mann= 3 ,-1,0
       0     .12       0    3620    .041       0 3846.12     .12       0
Bank Sta=3620,3846.12
XS Rating Curve= 0 ,0
Exp/Cntr(USF)=0,0
Exp/Cntr=0.3,0.1

Type RM Length L Ch R = 1 ,55462   ,1590.3,1590.3,1590.3
BEGIN DESCRIPTION:
HEC-2 RS: 215090 (LTR M)
END DESCRIPTION:
Node Name=M
XS GIS Cut Line= 6
2113568.81423419345468.007339637 2112947.9376938342607.997925717
2112732.08088266342287.2343462792112321.38115258342037.902023321
2109072.61770797342788.5819753352107403.45554704  342823.5553852
#Sta/Elev= 30
       0   20.41   536.7   19.98   566.8   12.46   640.4    7.62   683.9    10.8
   744.1    7.28   954.8    5.69    1224    8.51  1526.9    6.69  1543.5    9.19
  2068.7    6.78  3053.7    7.79    3180     8.6  3215.6   11.06  3230.4    9.11
  3530.1    7.26  4254.4    7.53  4425.2    3.75    46253.314335 4644.54    -2.9
 4768.05   -2.88 4790.713.322143    5492     5.1  5714.1    8.53  6326.5    5.43
  6676.4    9.23  7916.8   10.41  8360.3   14.39  8629.8   12.83  8803.3   14.52
#Mann= 3 ,-1,0
       0     .12       0    4625    .041       0 4790.71     .12       0
Bank Sta=4625,4790.71
XS Rating Curve= 0 ,0
Exp/Cntr(USF)=0,0
Exp/Cntr=0.3,0.1

Type RM Length L Ch R = 1 ,53872   ,1068.4,1068.4,1068.4
BEGIN DESCRIPTION:
HEC-2 RS: 214067
END DESCRIPTION:
XS GIS Cut Line= 6
2113665.95705568 345426.336509692113086.88115373342163.439416852
2112369.53776723341723.0682256752111241.00129154341342.111761542
2109965.28864871341437.8266651632107086.50153097342275.881131254
#Sta/Elev= 30
       0    20.4   338.9   21.36   379.5   24.94     503   12.22   549.7   13.56
   713.2    7.74   773.5    9.25   960.1    6.18  1661.4    8.73  3006.1    7.73
  3073.2    9.67  4510.9    7.78  5103.9   12.69  5380.9    9.59    5404    4.56
  5661.7     4.2  5687.9    7.93    5708    4.63  5840.1    3.24    61103.904998
 6125.35    -3.5 6246.04   -3.48 6282.263.966102  7423.3    5.85  7582.9    9.89
  7891.5   11.31  8155.4    8.09  8513.9    8.19    8889   10.35  9654.2   21.11
#Mann= 3 ,-1,0
       0     .12       0    6110    .041       0 6282.26     .12       0
#XS Ineff= 1 ,-1
 7904.23 8907.04   11.37
Permanent Ineff=
       T
Bank Sta=6110,6282.26
XS Rating Curve= 0 ,0
Exp/Cntr(USF)=0,0
Exp/Cntr=0.3,0.1

Type RM Length L Ch R = 1 ,52803   ,839.1,839.1,839.1
BEGIN DESCRIPTION:
HEC-2 RS: 213236
END DESCRIPTION:
XS GIS Cut Line= 6
2113710.59355572345430.4006670612113448.33330875343148.228105745
2113086.53357444341637.1573886812112748.97970278 341217.20142283
2110755.64770619340490.302856961 2109124.3484468339515.562594273
#Sta/Elev= 30
       0   21.75    23.1   22.74    66.1   20.11   272.6   23.09   416.2   22.35
   630.7   14.05   667.3   14.56   743.3     8.1  1004.2    6.41  1859.8    8.46
  2984.3    7.55  3436.5   10.03    4285     7.1  4990.1    8.73  5396.3   13.23
  5722.9    9.98  5840.9    6.54  6413.2    8.12    66603.492058 6676.48   -3.69
 6760.69   -3.67 6780.463.485386  7219.8    3.44    7428   16.88  7618.6   19.79
  8120.2   17.53  8202.9    19.2  8237.4   16.87  8252.8   19.51  8415.8   18.21
#Mann= 3 ,-1,0
       0     .12       0    6660    .041       0 6780.46     .12       0
Bank Sta=6660,6780.46
XS Rating Curve= 0 ,0
Exp/Cntr(USF)=0,0
Exp/Cntr=0.3,0.1

Type RM Length L Ch R = 1 ,51964   ,952,952,952
BEGIN DESCRIPTION:
HEC-2 RS: 212304
END DESCRIPTION:
XS GIS Cut Line= 6
2113753.67471267345423.5593204752113580.43345627 343190.64241309
2113183.51759426340879.1236672472111775.48857235340489.480415901
2111290.56987558 339988.659403132110252.98432053338783.358492686
#Sta/Elev= 30
       0   22.82   500.9   21.65   787.2    8.57  1027.4     6.3  2900.5    7.38
  2960.4    9.76  3108.2    7.37    3433   10.97  4048.6    5.98  4603.5    7.27
  4627.1   11.74  4647.4    6.79  5381.2    7.66  5401.5   11.21  5431.7    7.79
  5585.5   11.34  5854.9    8.51  6167.8    11.2  6548.8    2.84    6710 3.13754
 6716.82   -4.04 6786.62   -4.04 6797.952.897896  7392.1    3.16  7509.4    9.29
  7782.9   15.57  8117.3   15.28  8171.1   13.07  8189.7    15.2  8336.2   14.65
#Mann= 3 ,-1,0
       0     .12       0    6710    .041       0 6797.95     .12       0
Bank Sta=6710,6797.95
XS Rating Curve= 0 ,0
Exp/Cntr(USF)=0,0
Exp/Cntr=0.3,0.1

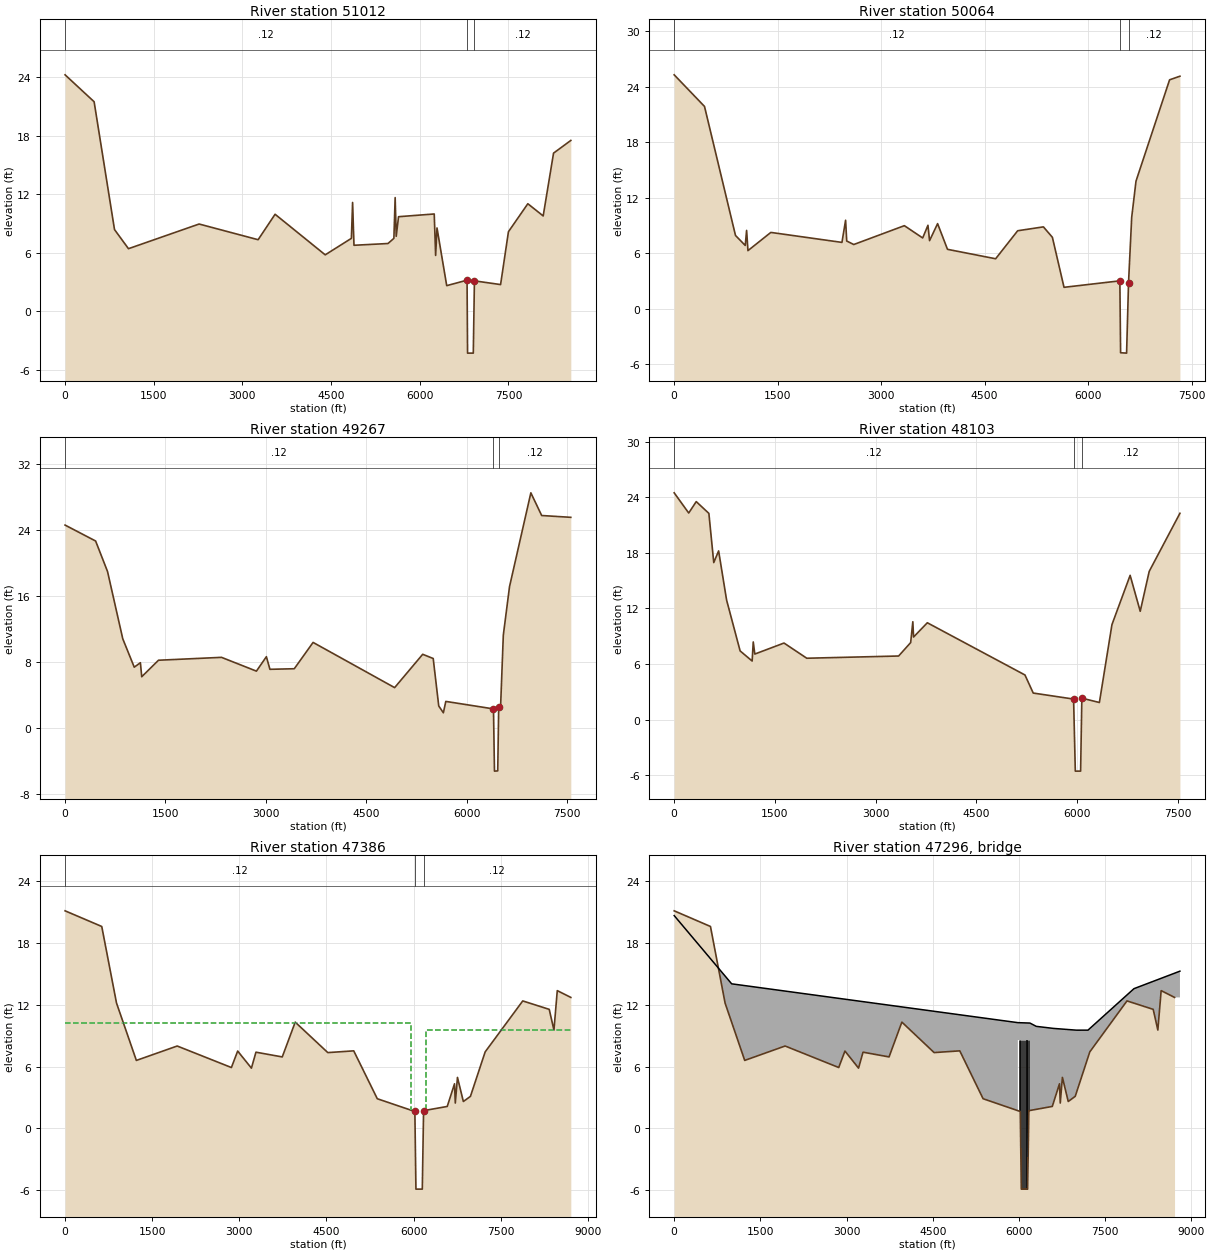
Type RM Length L Ch R = 1 ,51012   ,948.3,948.3,948.3
BEGIN DESCRIPTION:
HEC-2 RS: 211308
END DESCRIPTION:
XS GIS Cut Line= 6
2113784.01759306345418.4051467052113720.27176802342893.723116748
2113327.76276237340738.0580405182112459.28196653340443.410629815
2111632.31338533338680.5684926832111419.26402097337778.426294558
#Sta/Elev= 30
       0   24.26   491.3    21.5   836.3    8.39  1072.6    6.43  2267.3    8.96
  3265.6    7.35  3552.6    9.96  4400.8     5.8  4843.4    7.49  4863.7   11.17
  4887.2    6.78  5462.6    6.96  5562.3    7.49  5583.7   11.67  5601.8     7.7
  5640.9    9.71  6244.7    9.99  6268.6    5.74  6291.6    8.56    6456    2.64
    68003.201209 6808.59   -4.28 6905.56   -4.28 6924.723.132063  7367.3    2.75
  7500.2    8.17  7828.2   11.04  8087.9    9.79  8263.2   16.23  8555.3   17.53
#Mann= 3 ,-1,0
       0     .12       0    6800    .041       0 6924.72     .12       0
Bank Sta=6800,6924.72
XS Rating Curve= 0 ,0
Exp/Cntr(USF)=0,0
Exp/Cntr=0.3,0.1

Type RM Length L Ch R = 1 ,50064   ,797,797,797
BEGIN DESCRIPTION:
HEC-2 RS: 210260
END DESCRIPTION:
XS GIS Cut Line= 6
2113819.67999959345380.3975931412113927.97080106342095.905734601
2113711.50232809341102.1186541492113127.51502048340019.569395021
2112880.30446054339219.3152655542112811.38049324338267.623629299
#Sta/Elev= 30
       0   25.31   439.5   21.89   888.8    7.93    1030    6.85  1049.7    8.48
  1069.4    6.29  1401.1    8.26  2431.8    7.18  2484.6    9.58    2501    7.33
  2602.9    6.95  3336.4    8.99    3602    7.66  3678.4    9.03  3701.6    7.37
  3818.2    9.21  3961.6    6.43  4659.4    5.41    4979    8.44  5351.9    8.86
  5482.1    7.73  5650.7    2.32    64603.021096 6470.79   -4.76 6557.69    -4.8
 6585.91    2.83  6631.7     9.9  6694.2   13.81  7180.9   24.77  7330.7   25.16
#Mann= 3 ,-1,0
       0     .12       0    6460    .041       0 6585.91     .12       0
Bank Sta=6460,6585.91
XS Rating Curve= 0 ,0
Exp/Cntr(USF)=0,0
Exp/Cntr=0.3,0.1

Type RM Length L Ch R = 1 ,49267   ,1164.1,1164.1,1164.1
BEGIN DESCRIPTION:
HEC-2 RS: 209434
END DESCRIPTION:
XS GIS Cut Line= 6
2113842.64379361  345402.5263264 2114026.3655615343394.716572421
2114248.95082345341596.1784298422114134.59979798341062.760749973
2113770.53918435 340068.973669522113505.26959665337962.936515315
#Sta/Elev= 30
       0   24.54   456.4   22.61   634.4   18.91   861.8   10.76  1033.3    7.32
  1125.4    7.86  1145.2    6.16  1395.7    8.16  2336.8    8.51  2858.5    6.84
  3007.3    8.59  3060.2    7.06    3424    7.13    3705   10.32  4923.2    4.84
  5342.6    8.88  5499.5    8.37  5582.1    2.62  5651.4    1.79  5687.8    3.17
    64002.261818 6414.62   -5.28 6463.46   -5.25 6477.612.433743  6507.1    2.75
  6546.8    11.2  6639.6   17.08  6958.3   28.45  7119.9    25.7  7555.2   25.48
#Mann= 3 ,-1,0
       0     .12       0    6400    .041       0 6477.61     .12       0
Bank Sta=6400,6477.61
XS Rating Curve= 0 ,0
Exp/Cntr(USF)=0,0
Exp/Cntr=0.3,0.1

Type RM Length L Ch R = 1 ,48103   ,717.4,717.4,717.4
BEGIN DESCRIPTION:
HEC-2 RS: 208274 (LTR L)
END DESCRIPTION:
Node Name=L
XS GIS Cut Line= 6
2113877.86478229345392.9455559052113984.30492154344357.593753259
2114390.07680005 341709.099288592114726.00750383339431.354087047
 2114725.9193221338789.0864046892114276.75018094338049.327786138
#Sta/Elev= 30
       0   24.48   216.4    22.3   328.5   23.53   516.6   22.26   589.2   16.95
   661.7   18.21   780.5    12.9   981.8    7.41  1160.7    6.32  1177.3    8.38
  1200.5    7.07  1635.5    8.26  1974.1    6.62    3342    6.86  3521.3    8.31
  3553.3   10.56  3564.4    8.91  3769.4   10.45  5223.3    4.81  5346.1    2.86
 5947.11    2.21  5972.7   -5.57 6051.68   -5.57 6069.96    2.31  6331.3    1.84
  6518.3   10.25  6789.1   15.57  6939.3   11.69  7073.2      16  7530.4   22.27
#Mann= 3 ,-1,0
       0     .12       0 5947.11    .041       0 6069.96     .12       0
Bank Sta=5947.11,6069.96
XS Rating Curve= 0 ,0
Exp/Cntr(USF)=0,0
Exp/Cntr=0.5,0.3

Type RM Length L Ch R = 1 ,47386   ,148.2,148.2,148.2
BEGIN DESCRIPTION:
HEC-2 RS: 207385
END DESCRIPTION:
XS GIS Cut Line= 5
2113961.77074045345415.0293650792114204.83077183344471.731700322
2115437.79764054339477.5591892312115543.63379055339062.969763302
2116067.18892544336966.980577882
#Sta/Elev= 30
       0   21.12   631.4    19.6   885.6   12.16  1227.2    6.59  1930.4    7.99
  2863.3     5.9  2971.5     7.5  3208.1    5.84  3285.9    7.39  3738.9    6.93
    3962   10.31  4523.1    7.35  4969.3    7.52  5374.9    2.87  6021.8    1.63
 6040.13   -5.91 6149.65   -5.91 6171.84    1.71  6579.2    2.12  6704.4    4.32
  6717.9    2.45  6755.2    4.94  6856.6     2.6  6978.4     3.1  7232.1    7.42
  7879.2   12.37  8334.8   11.55    8416    9.54  8473.5   13.37  8706.5   12.71
#Mann= 3 ,-1,0
       0     .12       0  6021.8    .041       0 6171.84     .12       0
#XS Ineff= 2 , 0
            5955   10.27    6215            9.53
Permanent Ineff=
       F       F
Bank Sta=6021.8,6171.84
XS Rating Curve= 0 ,0
Exp/Cntr(USF)=0,0
Exp/Cntr=0.5,0.3

Type RM Length L Ch R = 3 ,47296   ,,,
BEGIN DESCRIPTION:
SC-303 over Ashepoo River
END DESCRIPTION:
Bridge Culvert--1,0,-1,-1, 0
Deck Dist Width WeirC Skew NumUp NumDn MinLoCord MaxHiCord MaxSubmerge Is_Ogee
25,90,2.6,0, 14, 14, , , 0.98, 0, 2,2,,
       0    1000 5979.99    5980    5980    6190    6190 6190.01    6300    6600
    7000    7200    8000    8800
  20.657  14.031   10.26   10.26   10.26   10.22   10.22   10.22     9.9     9.7
    9.53   9.531   13.56   15.26
                                    8.57    8.53
                                
       0    1000 5979.99    5980    5980    6190    6190 6190.01    6300    6900
    7000    7200    8000    8800
  20.657  14.031   10.26   10.26   10.26   10.22   10.22   10.22     9.9     9.7
    9.53   9.531   13.56   15.26
                                    8.57    8.53
                                
Pier Skew, UpSta & Num, DnSta & Num=  ,5995, 2 ,5995, 2 , 0 , 0 , 0 ,,
     1.5     1.5
      -6    9.95
     1.5     1.5
      -6    9.95
Pier Skew, UpSta & Num, DnSta & Num=  ,6010, 2 ,6010, 2 , 0 , 0 , 0 ,,
     1.5     1.5
   -5.91    9.95
     1.5     1.5
   -5.91    9.95
Pier Skew, UpSta & Num, DnSta & Num=  ,6025, 2 ,6025, 2 , 0 , 0 , 0 ,,
     1.5     1.5
      -6    9.95
     1.5     1.5
      -6    9.95
Pier Skew, UpSta & Num, DnSta & Num=  ,6040, 2 ,6040, 2 , 0 , 0 , 0 ,,
     1.5     1.5
   -5.91    9.95
     1.5     1.5
   -5.91    9.95
Pier Skew, UpSta & Num, DnSta & Num=  ,6055, 2 ,6055, 2 , 0 , 0 , 0 ,,
     1.5     1.5
      -6    9.95
     1.5     1.5
      -6    9.95
Pier Skew, UpSta & Num, DnSta & Num=  ,6070, 2 ,6070, 2 , 0 , 0 , 0 ,,
     1.5     1.5
   -5.91    9.95
     1.5     1.5
   -5.91    9.95
Pier Skew, UpSta & Num, DnSta & Num=  ,6085, 2 ,6085, 2 , 0 , 0 , 0 ,,
     1.5     1.5
      -6    9.95
     1.5     1.5
      -6    9.95
Pier Skew, UpSta & Num, DnSta & Num=  ,6100, 2 ,6100, 2 , 0 , 0 , 0 ,,
     1.5     1.5
   -5.91    9.95
     1.5     1.5
   -5.91    9.95
Pier Skew, UpSta & Num, DnSta & Num=  ,6115, 2 ,6115, 2 , 0 , 0 , 0 ,,
     1.5     1.5
      -6    9.95
     1.5     1.5
      -6    9.95
Pier Skew, UpSta & Num, DnSta & Num=  ,6130, 2 ,6130, 2 , 0 , 0 , 0 ,,
     1.5     1.5
   -5.91    9.95
     1.5     1.5
   -5.91    9.95
Pier Skew, UpSta & Num, DnSta & Num=  ,6145, 2 ,6145, 2 , 0 , 0 , 0 ,,
     1.5     1.5
      -6    9.95
     1.5     1.5
      -6    9.95
Pier Skew, UpSta & Num, DnSta & Num=  ,6160, 2 ,6160, 2 , 0 , 0 , 0 ,,
     1.5     1.5
   -5.91    9.95
     1.5     1.5
   -5.91    9.95
Pier Skew, UpSta & Num, DnSta & Num=  ,6175, 2 ,6175, 2 , 0 , 0 , 0 ,,
     1.5     1.5
      -6    9.95
     1.5     1.5
      -6    9.95
Abutment Skew #Up #Dn= , 3 , 3
    5980    5982  5990.7
    6.57    6.57    2.22
    5980    5982  5990.7
    6.57    6.57    2.22
Abutment Skew #Up #Dn= , 3 , 3
 6178.38    6188    6190
    1.72    6.53    6.53
 6178.38    6188    6190
    1.72    6.53    6.53
BR Coef=-1 ,-1 ,-1 ,0.9, 0 ,,,0.8,0,1.2,0,
WSPro=,,,, 1 ,,,, 0 ,,,, 0 ,,,,-1 ,-1 ,-1 , 0 , 0 , 0 , 0 , 0
BC Design=,, 0 ,, 0 ,,,,,,
BC Use User HTab Curves=0
BC User HTab FreeFlow(D)= 0

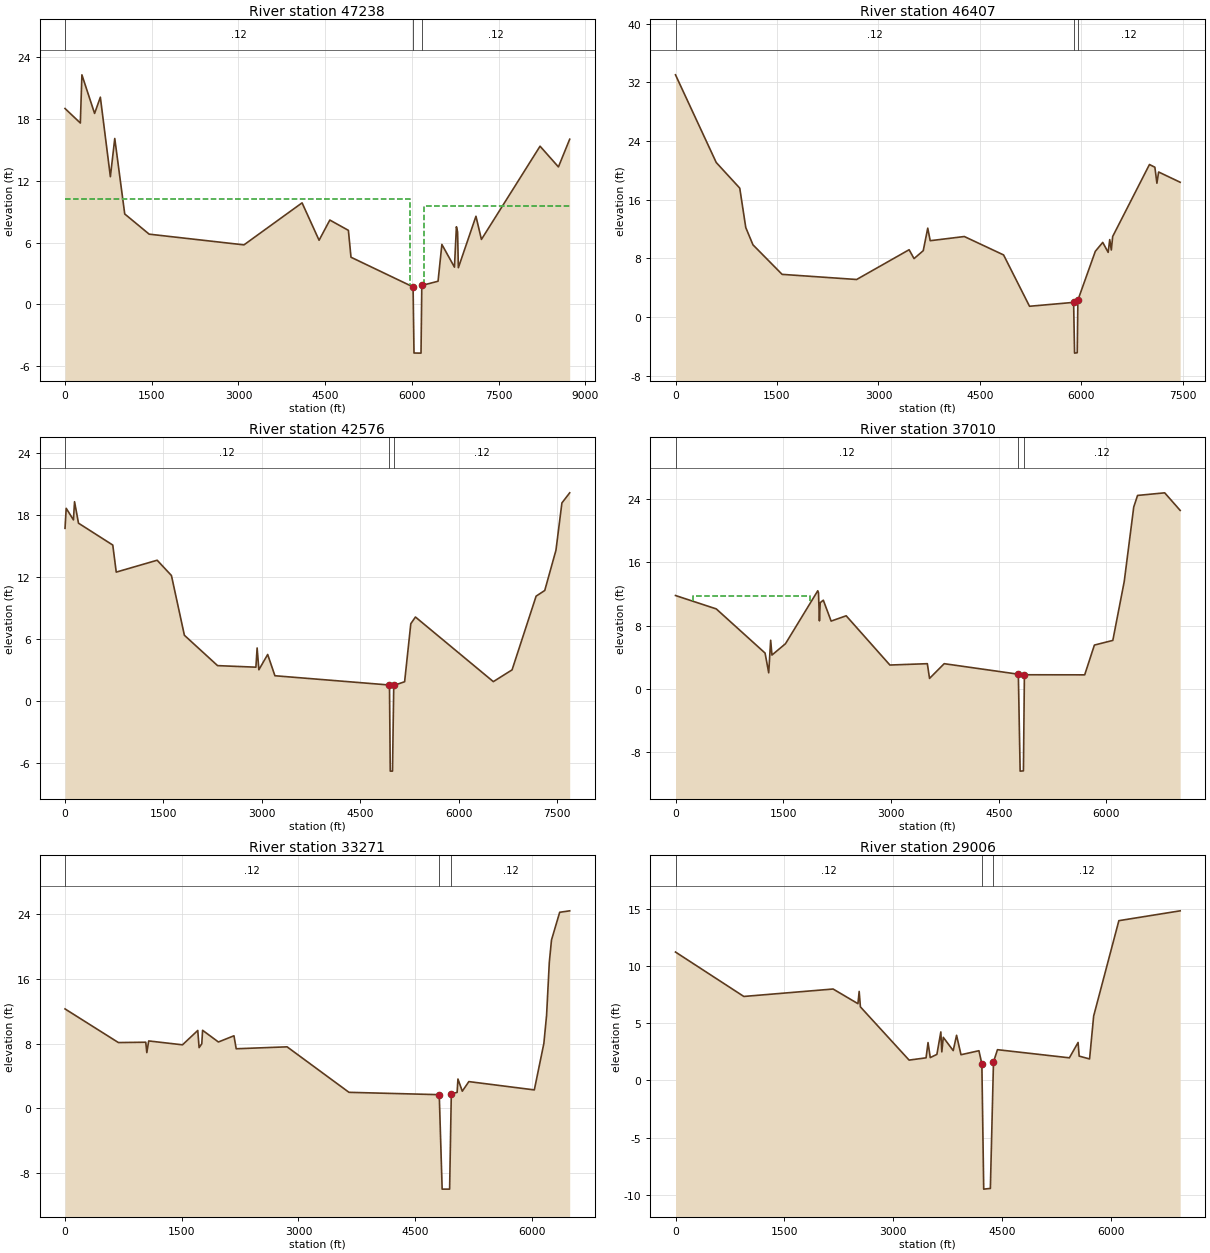
Type RM Length L Ch R = 1 ,47238   ,831.2,831.2,831.2
BEGIN DESCRIPTION:
HEC-2 RS: 207243
END DESCRIPTION:
XS GIS Cut Line= 6
2114073.47904332  345423.60386612114221.42584184344858.595689091
2114341.76739176344471.5221031752115658.66614636339198.105657315
2116169.30860132337126.505086102 2116213.6270204336961.916215067
#Sta/Elev= 30
       0   19.02   264.9   17.61     292   22.29   511.5   18.54     611   20.12
   784.4    12.4   860.3   16.11  1032.8    8.78  1455.5    6.82  3094.8    5.78
  4099.9    9.86  4394.1    6.23  4580.1    8.19  4901.3    7.19  4946.1    4.58
    60201.697643 6035.72   -4.72 6157.21   -4.73  6170.8    1.84  6451.8    2.25
  6518.1    5.82  6735.6    3.62  6769.4    7.54  6789.7    7.04  6803.2    3.56
  7107.5    8.56  7202.2    6.31  8216.2   15.36  8533.9   13.35  8728.9   16.04
#Mann= 3 ,-1,0
       0     .12       0    6020    .041       0  6170.8     .12       0
#XS Ineff= 2 , 0
            5963   10.27    6207            9.53
Permanent Ineff=
       F       F
Bank Sta=6020,6170.8
XS Rating Curve= 0 ,0
Exp/Cntr(USF)=0,0
Exp/Cntr=0.5,0.3

Type RM Length L Ch R = 1 ,46407   ,3831.1,3831.1,3831.1
BEGIN DESCRIPTION:
HEC-2 RS: 206515 (LTR K)
END DESCRIPTION:
Node Name=K
XS GIS Cut Line= 5
2115537.78628686345276.3727564262115691.65318385344076.177599645
2116229.20633682340420.1299743212116525.06356667338740.926794892
2116681.20054587337905.065912506
#Sta/Elev= 30
       0   33.03   602.4   21.07   949.8   17.58    1039    12.2    1145    9.85
  1576.1    5.82  2677.4    5.12  3453.6    9.18  3526.5    7.97  3662.5    9.05
  3728.9   12.12  3765.6   10.41  4269.6   10.98  4850.1    8.47  5233.7    1.47
 5885.54       2 5899.47   -4.92 5938.86   -4.87 5948.39     2.3  6206.1    8.96
  6316.1   10.18    6396    8.82  6419.4   10.56  6442.7    9.14  6462.7   10.98
  7006.6    20.8  7086.7   20.43  7116.8   18.25  7142.3   19.78  7460.8   18.38
#Mann= 3 ,-1,0
       0     .12       0 5885.54    .041       0 5948.39     .12       0
Bank Sta=5885.54,5948.39
XS Rating Curve= 0 ,0
Exp/Cntr(USF)=0,0
Exp/Cntr=0.3,0.1

Type RM Length L Ch R = 1 ,42576   ,5565.5,5565.5,5565.5
XS GIS Cut Line= 4
2118303.66927878346002.5906400612119278.61713182341189.752825883
2119603.39438416339740.9089025852119883.18310562338475.198019788
#Sta/Elev= 30
       0   16.75    17.9   18.69   128.4   17.57   145.1   19.33   205.4   17.25
   727.8   15.13   780.6   12.51  1404.2   13.66  1621.8   12.18  1819.4    6.39
    2325    3.45  2909.1     3.3  2927.7    5.16  2954.5    3.05  3088.5    4.53
    3199    2.47    49451.571982 4956.82   -6.77 4991.02   -6.77    50101.527162
  5175.7    1.89  5269.9    7.51  5340.5    8.16  6527.7     1.9  6813.4    3.04
  7179.7   10.18  7311.4   10.73  7482.2   14.63  7572.9   19.217691.659   20.19
#Mann= 3 ,0,0
       0     .12       0    4945    .041       0    5010     .12       0
Bank Sta=4945,5010
XS Rating Curve= 0 ,0
Exp/Cntr(USF)=0,0
Exp/Cntr=0.3,0.1

Type RM Length L Ch R = 1 ,37010   ,3738.7,3738.7,3738.7
BEGIN DESCRIPTION:
HEC-2 RS: 197805 (LTR I)
END DESCRIPTION:
Node Name=I
XS GIS Cut Line= 6
2124552.79285475345492.2516775562123836.54206595342602.273698308
2123387.02818671340830.4235865182123242.98947943340525.936698981
2123166.86284749339519.7699893162123290.64051106338653.450830175
#Sta/Elev= 30
       0   11.81   567.5   10.12  1247.1    4.54  1297.8    2.05  1324.9    6.16
  1342.8    4.29  1531.1    5.72  1980.8   12.41  1990.9   12.16  2003.9    8.61
  2014.6    10.9  2058.1   11.22  2166.8    8.58  2376.4    9.25    2985    3.03
  3506.4     3.2  3536.9    1.34  3740.9     3.2  4773.3   1.871 4798.42  -10.37
 4844.01  -10.34  4857.7   1.801  5697.1    1.79    5832    5.55  6088.7    6.14
  6247.4   13.57    6380   22.99  6433.1   24.45    6811   24.78  7026.5   22.56
#Mann= 3 ,-1,0
       0     .12       0  4773.3    .041       0  4857.7     .12       0
#XS Ineff= 1 ,-1
  243.38 1870.42    11.8
Permanent Ineff=
       T
Bank Sta=4773.3,4857.7
XS Rating Curve= 0 ,0
Exp/Cntr(USF)=0,0
Exp/Cntr=0.3,0.1

Type RM Length L Ch R = 1 ,33271   ,4264.8,4264.8,4264.8
XS GIS Cut Line= 6
2127732.46096736344794.0527805662126399.23665777 340633.47969719
2126231.03891756340225.1461509062126201.34741081340158.829709078
2126135.02888988 340045.470241962125616.70249457338667.560752107
#Sta/Elev= 30
       0   12.29   686.1    8.12  1037.6    8.16  1051.4    6.87  1075.5    8.32
  1509.8    7.84  1706.2    9.62  1723.4    7.49  1757.9    7.97  1768.2    9.64
  1971.6    8.19  2171.4    8.96  2200.2    7.35  2854.4    7.59  3649.9    1.95
    48101.658942 4847.36  -10.05 4943.36  -10.05 4964.96    1.76  5039.7    1.94
  5050.3     3.6  5106.3    2.09  5190.5    3.28    6032    2.25  6154.7    8.01
  6189.8   11.52  6224.8   18.09  6252.9   20.84  6358.1   24.27  6486.8   24.45
#Mann= 3 ,0,0
       0     .12       0    4810    .041       0 4964.96     .12       0
Bank Sta=4810,4964.96
XS Rating Curve= 0 ,0
Exp/Cntr(USF)=0,0
Exp/Cntr=0.3,0.1

Type RM Length L Ch R = 1 ,29006   ,6216.7,6216.7,6216.7
XS GIS Cut Line= 4
2130868.70562372343778.9454059382129851.97429128339809.514861452
2129448.06732359339029.5565790262128626.32556175337232.866964154
#Sta/Elev= 30
       0   11.22   941.1    7.34  2170.8    7.99    2513    6.71  2529.9    7.78
  2546.9    6.43  3217.7    1.78  3451.4    1.98  3478.5    3.31    3509       2
  3600.5    2.28  3654.7    4.24  3668.2     2.5  3688.6    3.77  3825.4    2.61
  3871.5    3.95  3932.5    2.25  4179.6     2.6    42201.439775 4245.38   -9.49
  4337.1   -9.43    43801.616352  4434.9    2.69  5425.6    1.98  5545.3    3.32
  5560.2    2.13  5703.5    1.88  5759.8    5.63    6107   13.966951.603   14.82
#Mann= 3 ,0,0
       0     .12       0    4220    .041       0    4380     .12       0
Bank Sta=4220,4380
XS Rating Curve= 0 ,0
Exp/Cntr(USF)=0,0
Exp/Cntr=0.3,0.1

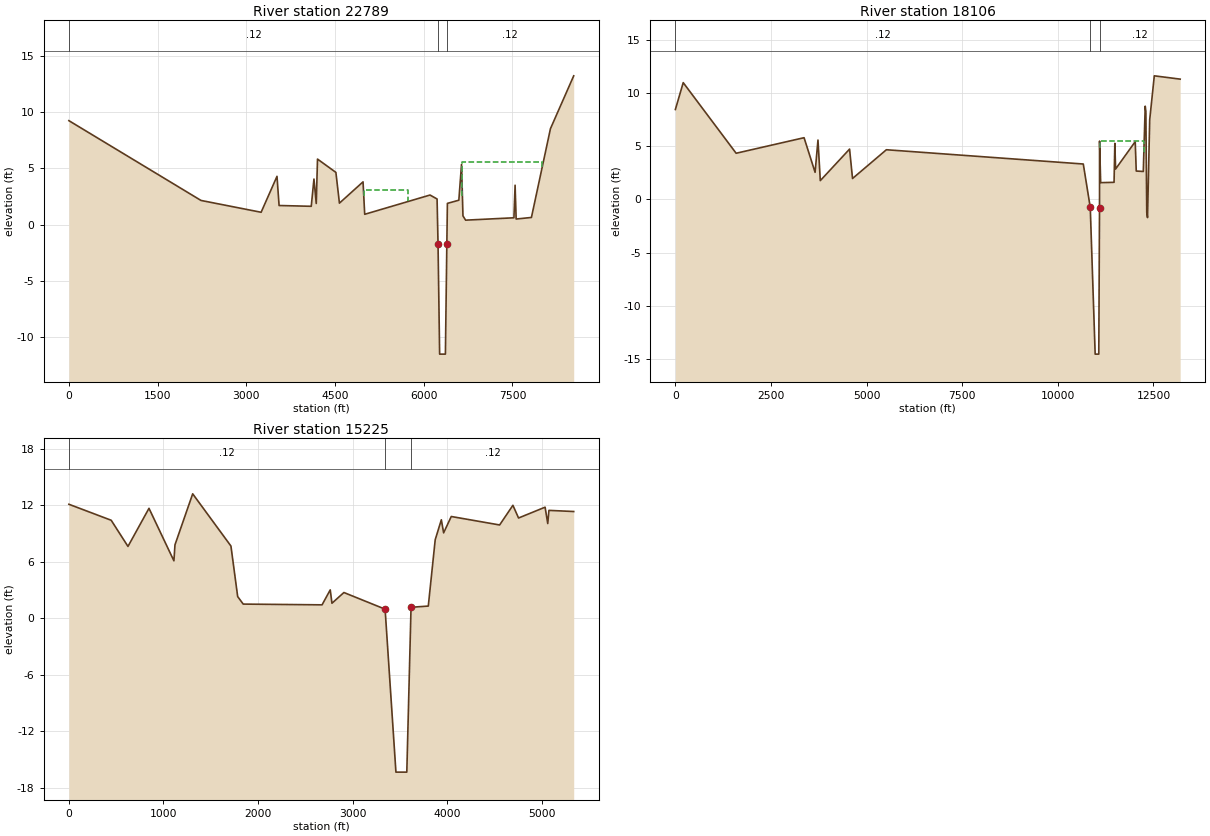
Type RM Length L Ch R = 1 ,22789   ,4683.6,4683.6,4683.6
XS GIS Cut Line= 6
2132490.72681081342747.7794307372134387.27894148337969.420724765
2134045.07224507337683.6217255622133781.83632475337483.061024367
2133155.08413351337119.544753451 2131625.8087869336003.925853054
#Sta/Elev= 30
       0    9.22  2233.2    2.14  3250.1    1.09  3518.5    4.28  3553.8    1.69
  4097.5    1.62  4143.4    4.04  4182.3    1.87  4203.4    5.81  4514.2    4.63
  4574.2     1.9  4973.2    3.79  5001.4     .91  6105.7    2.62  6225.1    2.27
 6241.25   -1.71 6268.35   -11.5 6365.92   -11.5 6390.31   -1.71  6399.6    1.88
  6593.1    2.16  6638.6    5.34  6662.7     .77  6707.4     .39  7524.4      .6
  7544.2    3.49  7561.9     .49  7820.3     .63  8142.1    8.51  8535.3    13.2
#Mann= 3 ,0,0
       0     .12       0 6241.25    .041       0 6390.31     .12       0
#XS Ineff= 2 ,-1
 4985.92 5740.85    3.05 6653.52    8000    5.52
Permanent Ineff=
       T       T
Bank Sta=6241.25,6390.31
XS Rating Curve= 0 ,0
Exp/Cntr(USF)=0,0
Exp/Cntr=0.3,0.1

Type RM Length L Ch R = 1 ,18106   ,2881.7,2881.7,2881.7
BEGIN DESCRIPTION:
HEC-2 RS: 180110
END DESCRIPTION:
XS GIS Cut Line= 6
2133198.10085543343084.9290509452136662.38825996337701.036504507
2136152.49314414334776.638046135  2134562.820136333831.832390353
2133308.94410524333570.6051741552132610.09220737333597.310031031
#Sta/Elev= 30
       0    8.43   205.4   10.95  1589.2    4.32  3365.2    5.78  3653.6    2.53
  3729.1    5.56  3789.7    1.75  4555.1    4.71  4632.8    1.95  5518.2    4.65
 10666.9    3.31 10849.1   -.75910977.39  -14.5411072.04  -14.54   11091   -.859
 11092.4    5.46   11121    1.56 11471.5    1.59 11491.6    5.25 11511.8    2.84
 12024.7    5.41 12051.6    2.65 12235.8    2.61 12286.1    8.74 12302.9    8.25
 12326.4   -1.25 12346.5   -1.72 12403.5    7.46 12523.7   11.5913200.33   11.28
#Mann= 3 ,-1,0
       0     .12       0 10849.1    .041       0   11091     .12       0
#XS Ineff= 1 ,-1
11097.4612249.01    5.48
Permanent Ineff=
       T
Bank Sta=10849.1,11091
XS Rating Curve= 0 ,0
Exp/Cntr(USF)=0,0
Exp/Cntr=0.3,0.1

Type RM Length L Ch R = 1 ,15225   ,,,
BEGIN DESCRIPTION:
HEC-2 RS: 177364 (LTR D)
END DESCRIPTION:
Node Name=D
XS GIS Cut Line= 6
2138686.88981973334170.621266617 2138072.9406002333078.175126334
 2135965.3590348332114.7867726172135877.29752476332038.207900614
2135718.47229846331890.3658788332134495.04402882331143.070104544
#Sta/Elev= 30
       0   12.11   447.2   10.41   624.7    7.63   846.8   11.68  1110.3     6.1
  1121.6     7.8  1308.9   13.22  1713.4    7.67  1784.6     2.3  1843.3     1.5
  2676.8    1.42  2763.4    3.01  2781.5    1.59  2907.8    2.73 3343.51     .96
 3458.03  -16.36 3572.96  -16.36  3617.8   1.161  3800.2    1.29  3873.3    8.34
  3938.2   10.46  3962.3    9.07  4043.1   10.81  4554.5    9.91  4694.9      12
  4754.6   10.65  5035.2    11.8  5063.3   10.06  5075.9   11.46  5337.8   11.34
#Mann= 3 ,-1,0
       0     .12       0 3343.51    .041       0  3617.8     .12       0
Bank Sta=3343.51,3617.8
XS Rating Curve= 0 ,0
Exp/Cntr(USF)=0,0
Exp/Cntr=0.3,0.1
LCMann Table=0

Chan Stop Cuts=-1
Use User Specified Reach Order=0
Composite Channel Slope=5

--- AshepooRiver.g04 (geometry) ---

Geom Title=Proposed Conditions
Program Version=6.60

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
River Reach=River 1         ,Reach 1

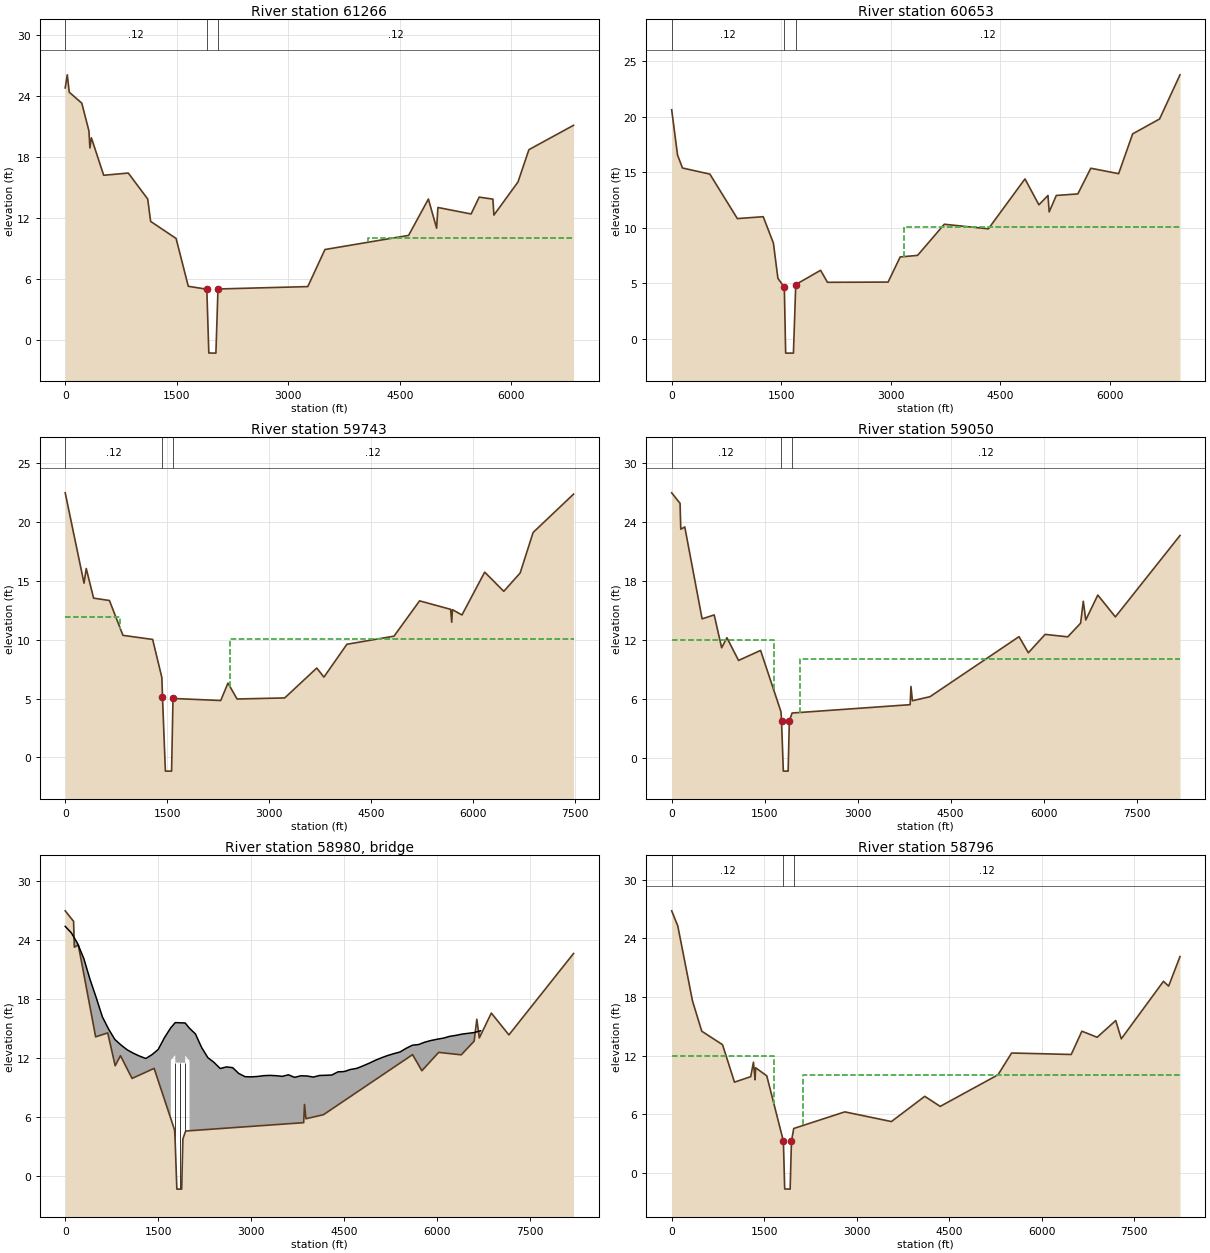
Type RM Length L Ch R = 1 ,61266   ,612.6,612.6,612.6
XS GIS Cut Line= 6
2109643.36416889348136.061039782 2109419.2208664346405.377529302
2108901.83713806345764.4344459052108097.35273658345035.840382716
2107248.48796725344541.4190195852105134.72207127343946.508637072
#Sta/Elev= 30
       0   24.82    27.9   26.11    54.4    24.4   223.1   23.32   319.1   20.59
   332.4   18.91   352.2   19.91   517.7   16.22   848.6   16.44    1110   13.88
  1148.9   11.68  1491.6      10  1655.7    5.29    19055.002243 1931.73   -1.28
 2027.04   -1.29    20555.025343  3262.9    5.26  3493.7    8.91  4618.7    10.3
  4885.3   13.88  4996.1   11.01  5013.1   13.05  5459.7   12.41  5568.8   14.07
  5752.9   13.87  5766.6    12.3  6090.5   15.56  6237.1   18.74  6837.5   21.14
#Mann= 3 ,0,0
       0     .12       0    1905    .041       0    2055     .12       0
#XS Ineff= 2 , 0
                            4079           10.03
Permanent Ineff=
       F       F
Bank Sta=1905,2055
XS Rating Curve= 0 ,0
Exp/Cntr(USF)=0,0
Exp/Cntr=0.5,0.3

Type RM Length L Ch R = 1 ,60653   ,910.6,910.6,910.6
XS GIS Cut Line= 5
2110712.77288746347311.8579898082109773.11276474345805.532602232
2108460.91386474344677.8068074582107503.50920049344364.812564901
2105104.22212249343861.947563075
#Sta/Elev= 30
       0   20.62    80.6   16.54   148.1   15.38   523.3   14.83   900.1   10.83
  1254.4      11  1393.6    8.63  1455.5    5.46 1543.58    4.65 1561.55   -1.27
 1668.17   -1.27    17004.898249  2040.4    6.18  2134.4     5.1  2965.2    5.12
  3130.8    7.38  3368.8    7.52  3734.8   10.32  4339.1    9.91  4840.4    14.4
  5031.2   12.07  5155.6   12.91  5172.3   11.43  5269.6   12.91  5564.6   13.05
  5742.4   15.36  6123.4   14.87  6315.7   18.45  6684.6   19.79  6964.3   23.76
#Mann= 3 ,0,0
       0     .12       0 1543.58    .041       0    1700     .12       0
#XS Ineff= 2 , 0
                            3179           10.03
Permanent Ineff=
       F       F
Bank Sta=1543.58,1700
XS Rating Curve= 0 ,0
Exp/Cntr(USF)=0,0
Exp/Cntr=0.5,0.3

Type RM Length L Ch R = 1 ,59743   ,692.5,692.5,692.5
XS GIS Cut Line= 6
 2111543.9979528346799.4654006252110720.29886494345621.270508605
2110432.87640412345334.4647799842109800.23240003344896.283538183
2108623.27742312  344521.24242642105070.32233361343764.748045568
#Sta/Elev= 30
       0   22.49   277.2   14.81   309.7   16.06   418.2   13.54   651.1   13.34
   849.8   10.38  1287.4   10.03  1423.1    6.79 1432.21    5.13  1474.9   -1.16
 1566.09   -1.16  1586.85.015964  2289.7    4.84  2396.2    6.32  2530.4    4.97
  3231.5    5.06  3703.4     7.6  3808.9    6.83  4147.1    9.62  4840.5   10.31
  5217.1   13.31  5673.7   12.59  5690.5   11.49  5700.5   12.56  5841.1   12.11
  6175.8   15.75  6456.9   14.12  6697.9   15.68  6888.7   19.12  7483.6   22.38
#Mann= 3 ,0,0
       0     .12       0 1432.21    .041       0  1586.8     .12       0
#XS Ineff= 2 , 0
             811   11.95    2429           10.03
Permanent Ineff=
       F       F
Bank Sta=1432.21,1586.8
XS Rating Curve= 0 ,0
Exp/Cntr(USF)=0,0
Exp/Cntr=0.5,0.3

Type RM Length L Ch R = 1 ,59050   ,254.1,254.1,254.1
BEGIN DESCRIPTION:
HEC-2 RS: 218448
END DESCRIPTION:
XS GIS Cut Line= 6
2112282.70593525346571.0636307492111510.76004851345480.860592143
2111131.56207502345054.5707431452110853.32104535344810.025185703
2110729.34134793344740.5849727232105051.66105604343662.589639585
#Sta/Elev= 30
       0   26.96   135.3   25.89     147   23.26   211.4   23.49   490.8   14.14
   685.9   14.54     806    11.2   891.1   12.22  1078.6    9.91  1434.1   10.93
  1763.5    4.68 1772.133.742357  1800.8   -1.35 1878.42   -1.35 1897.79    3.75
    1942    4.56  3846.3    5.41  3859.6    7.26  3882.9    5.81  4166.1    6.22
  5602.5   12.33    5753   10.69  6023.8   12.56  6388.3   12.31  6595.6    13.7
    6639   15.93  6679.2   14.03  6872.8   16.56  7156.3   14.34  8198.7   22.62
#Mann= 3 ,-1,0
       0     .12       0  1763.5    .041       0    1942     .12       0
#XS Ineff= 2 , 0
            1648   11.95    2062           10.03
Permanent Ineff=
       F       F
Bank Sta=1772.13,1897.79
XS Rating Curve= 0 ,0
Exp/Cntr(USF)=0,0
Exp/Cntr=0.5,0.3

Type RM Length L Ch R = 3 ,58980   ,,,
BEGIN DESCRIPTION:
S-15-41 over Ashepoo River
END DESCRIPTION:
Bridge Culvert--1,0,-1,-1, 0
Deck Dist Width WeirC Skew NumUp NumDn MinLoCord MaxHiCord MaxSubmerge Is_Ogee
53.74202,30,2.6,0, 73, 73, , , 0.98, 0, 2,2,,
       0     100     200     300     400     500     600     700     800     900
    1000    1100    1200    1300    1400    1500    1600    1700 1704.99    1705
 1774.99    1775    1935 1935.01    2005 2005.01    2100    2200    2300    2400
    2500    2600    2700    2800    2900    3000    3100    3200    3300    3400
    3500    3600    3700    3800    3900    4000    4100    4200    4300    4400
    4500    4600    4700    4800    4900    5000    5100    5200    5300    5400
    5500    5600    5700    5800    5900    6000    6100    6200    6300    6400
    6500    6600    6700
   25.38   24.71   23.63   22.11   19.99   18.13   16.17   14.93   13.88   13.31
   12.82   12.47   12.18   11.94   12.33   12.86   14.05   15.04   15.08   15.08
   15.59   15.59   15.55   15.55   15.01   15.01   14.44   13.06   12.03   11.54
   10.92   11.08   11.01   10.41   10.09   10.07   10.11   10.19   10.22   10.19
   10.12   10.28   10.02   10.18   10.16   10.05   10.21   10.23   10.26   10.58
   10.61   10.82   10.93   11.18   11.45   11.75   12.01   12.24   12.43    12.6
   12.98   13.29   13.36    13.6   13.77    13.9   14.01   14.19   14.29   14.42
    14.5   14.58   14.76
                                                                                
                                                                           11.78
   12.28   11.53   11.49   12.24    11.7
                                                                                
                                                                                
                                                                                
                                                                                
                        
      41     141     241     341     441     541     641     741     841     941
    1041    1141    1241    1341    1441    1541    1641    1741 1745.99    1746
 1815.99    1816    1976 1976.01    2046 2046.01    2141    2241    2341    2441
    2541    2641    2741    2841    2941    3041    3141    3241    3341    3441
    3541    3641    3741    3800    3900    4041    4141    4241    4341    4441
    4541    4641    4741    4841    4941    5041    5141    5241    5341    5441
    5541    5641    5741    5841    5941    6041    6141    6241    6341    6441
    6541    6641    6741
   25.38   24.71   23.63   22.11   19.99   18.13   16.17   14.93   13.88   13.31
   12.82   12.47   12.18   11.94   12.33   12.86   14.05   15.04   15.08   15.08
   15.59   15.59   15.55   15.55   15.01   15.01   14.44   13.06   12.03   11.54
   10.92   11.08   11.01   10.41   10.09   10.07   10.11   10.19   10.22   10.19
   10.12   10.28   10.02   10.18   10.16   10.05   10.21   10.23   10.26   10.58
   10.61   10.82   10.93   11.18   11.45   11.75   12.01   12.24   12.43    12.6
   12.98   13.29   13.36    13.6   13.77    13.9   14.01   14.19   14.29   14.42
    14.5   14.58   14.76
                                                                                
                                                                           11.78
   12.28   11.53   11.49   12.24    11.7
                                                                                
                                                                                
                                                                                
                                                                                
                        
Pier Skew, UpSta & Num, DnSta & Num=  ,1775, 2 ,1816, 2 , 0 , 0 , 0 ,,
       4       4
       3   12.28
       4       4
       2   12.28
Pier Skew, UpSta & Num, DnSta & Num=  ,1855, 2 ,1896, 2 , 0 , 0 , 0 ,,
       4       4
    -1.5   11.53
       4       4
    -1.7   11.53
Pier Skew, UpSta & Num, DnSta & Num=  ,1935, 2 ,1976, 2 , 0 , 0 , 0 ,,
       4       4
     4.5   12.24
       4       4
     4.5   12.24
Abutment Skew #Up #Dn= , 3 , 3
 1704.99    1707 1716.56
    9.78    9.78       5
 1745.99    1748 1757.56
    9.78    9.78       5
Abutment Skew #Up #Dn= , 3 , 3
 1993.59    2003 2005.01
       5     9.7     9.7
 2034.59    2044 2046.01
       5     9.7     9.7
BR Coef=-1 ,-1 ,-1 ,0.9, 0 ,,,0.8,0,1.2,0,
WSPro=,,,, 1 ,,,, 0 ,,,, 0 ,,,,-1 ,-1 ,-1 , 0 , 0 , 0 , 0 , 0
BC Design=,, 0 ,, 0 ,,,,,,
BC Use User HTab Curves=0
BC User HTab FreeFlow(D)= 0

Type RM Length L Ch R = 1 ,58796   ,616.6,616.6,616.6
BEGIN DESCRIPTION:
HEC-2 RS: 218419
END DESCRIPTION:
XS GIS Cut Line= 6
2112465.11983619 346422.549297062111363.13655015344933.468875854
2111165.40341921344740.6376676242110893.85305968344560.725925455
2110725.69108737 344502.288003772105210.34691174343461.561526106
#Sta/Elev= 30
       0   26.81    98.7   25.28   338.2   17.59     488    14.5   825.3   13.12
  1019.1    9.29  1282.2    9.85  1326.9   11.33  1352.7    9.53  1362.2   10.76
  1543.5    9.93 1812.413.262738 1833.62   -1.63 1922.08   -1.65  1943.2    3.23
  1980.2    4.55  2808.6    6.25  3565.2    5.26  4106.1    7.84  4356.5    6.81
  5294.1   10.04    5515   12.27  6482.5   12.12  6655.3    14.5  6902.9   13.88
  7204.5   15.59  7294.5   13.72  7978.7    19.6  8062.5   19.11    8247   22.13
#Mann= 3 ,-1,0
       0     .12       0 1812.41    .041       0  1980.2     .12       0
#XS Ineff= 2 , 0
            1661   11.95    2131           10.03
Permanent Ineff=
       F       F
Bank Sta=1812.41,1943.2
XS Rating Curve= 0 ,0
Exp/Cntr(USF)=0,0
Exp/Cntr=0.5,0.3

--- AshepooRiver.g05 (geometry) ---

Geom Title=Post Project
Program Version=6.60

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
River Reach=River 1         ,Reach 1
Reach XY= 30
2098396.23576606380646.8009591682097747.70079908376704.682944754
2098349.83399384 375176.529045482097726.69704407373600.953953826
2098114.75192337367841.6387006832099554.59564156365212.903242423
2099428.81121289363681.5771457152100708.15579364362482.324665464
2101289.63273322358523.8663055422100333.06655326351923.692230741
2105558.65619563 346752.098334352109100.83653268346361.782563958
 2111805.7756717  344595.11980812111881.37719572 342976.52674064
2110389.42873442341236.9377136342112009.03935508339315.330548813
2116615.76753564    339445.902442118850.12631383 341189.46406122
2121488.85557328  342010.05266182124117.63341542 340190.58593847
 2128091.1898635 340778.699006762130034.79235487  338498.5211566
2133356.08251692 338118.686337012134731.17271658 332679.67329194
2137633.21854056 330935.617395952135404.68988351 328442.04194944
 2135479.5315566 327368.052712862137781.44848433  324683.1006559
2139929.12472133 324531.725201252141596.00533789 322979.69654025