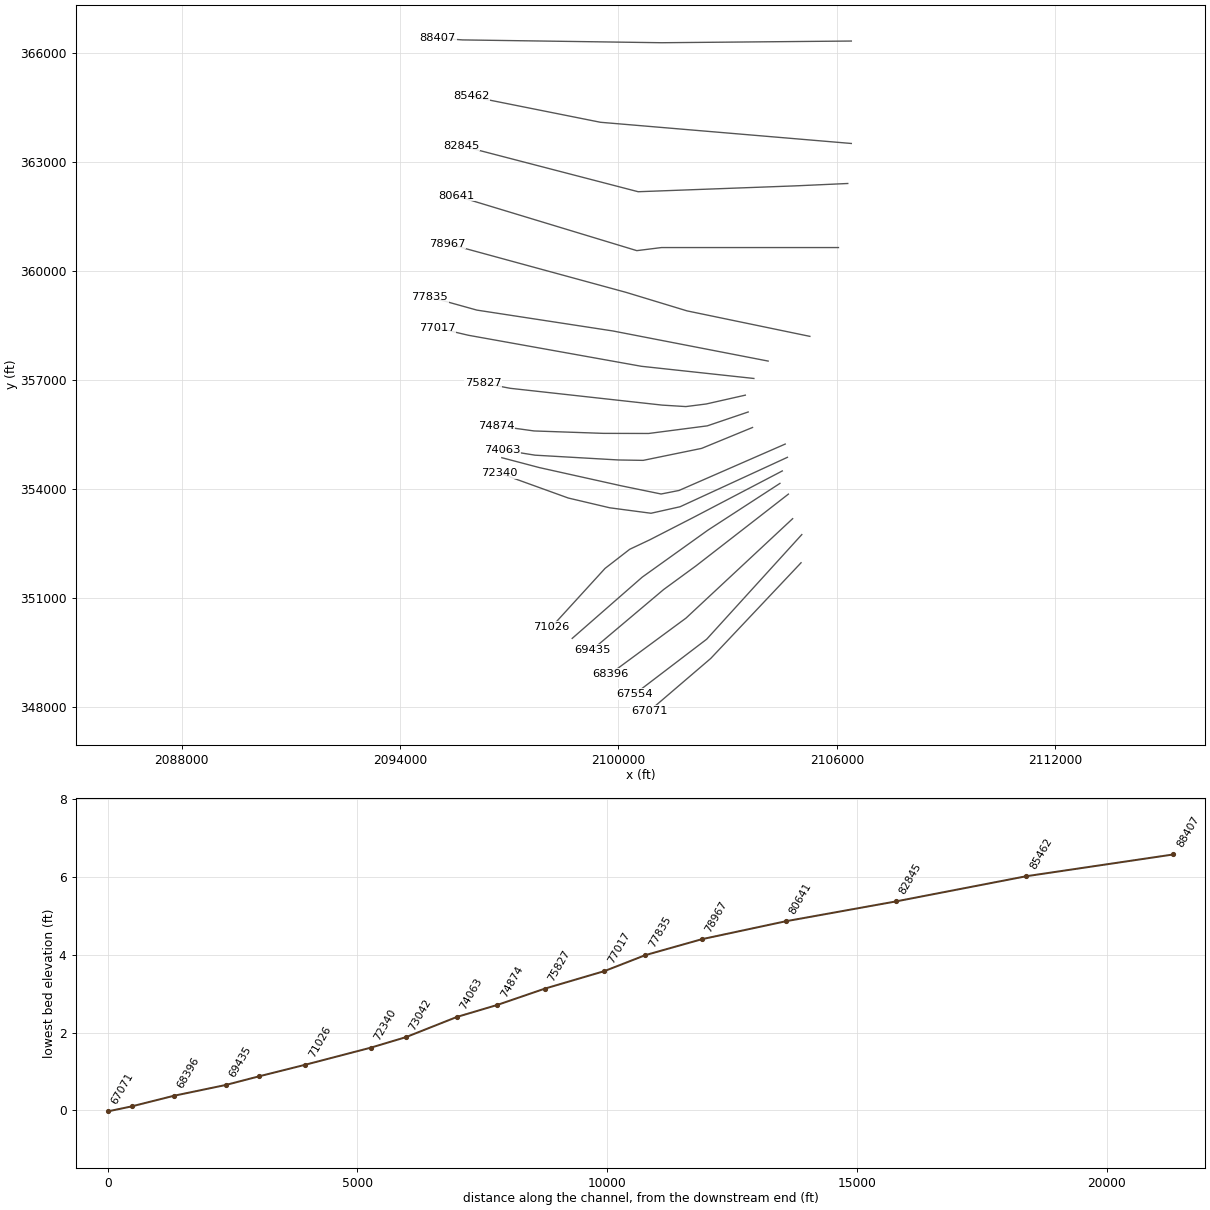
HEC-RAS study AshepooRiver.prj: S-15-41 over Ashepoo River

--- AshepooRiver.g05 (geometry) --- (continued)

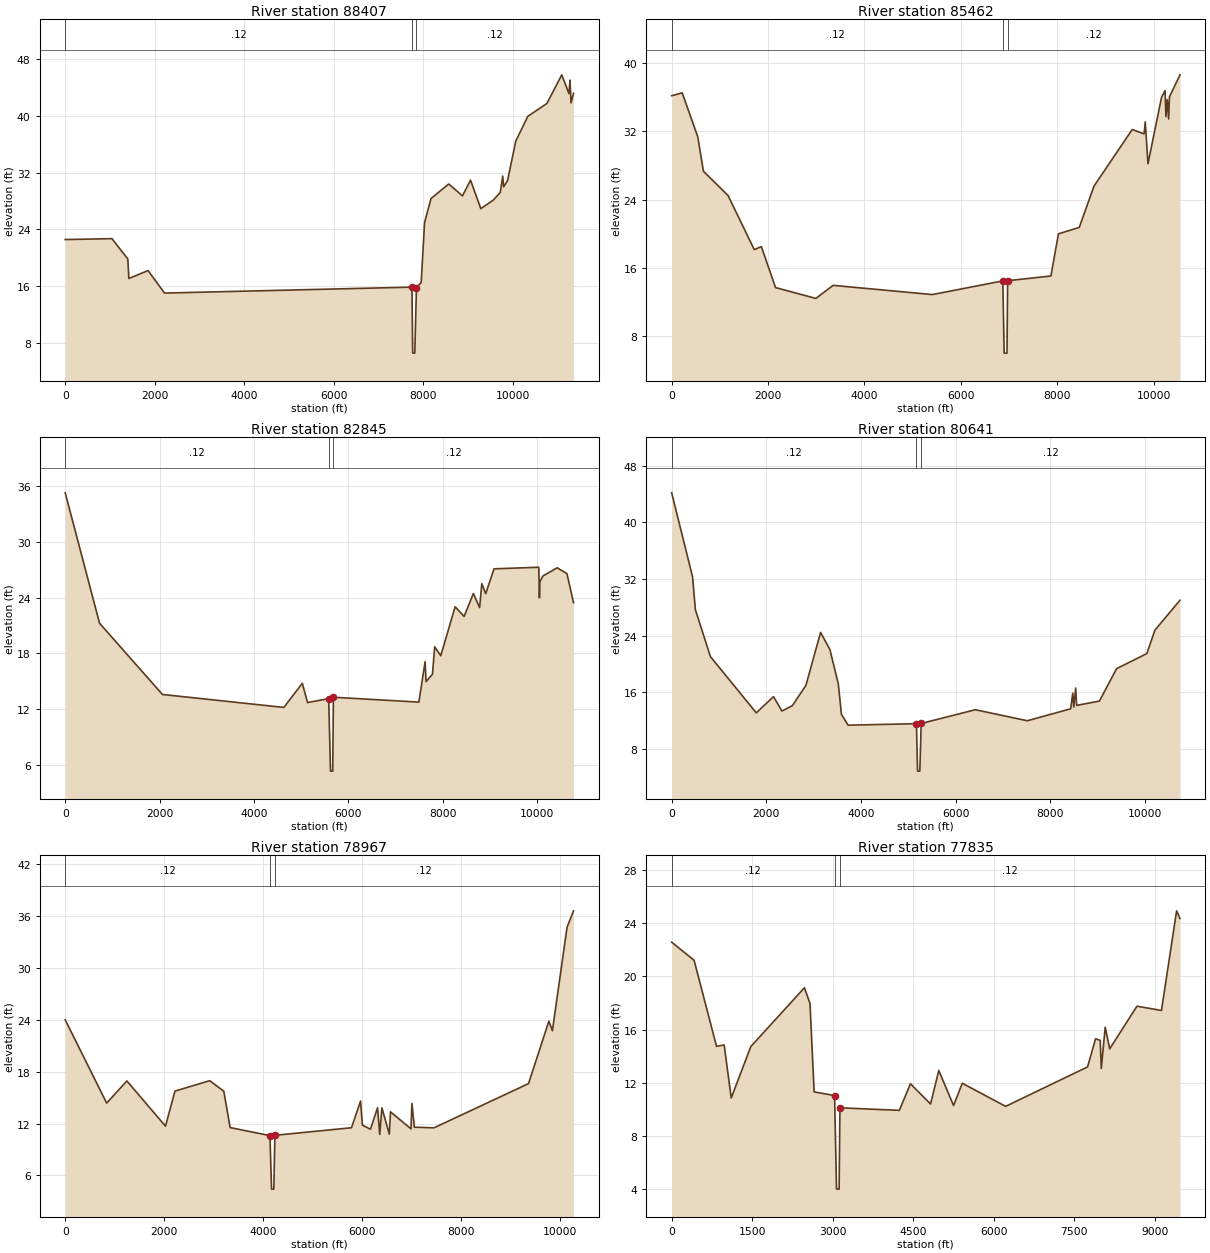
Type RM Length L Ch R = 1 ,88407   ,2944.8,2944.8,2944.8
XS GIS Cut Line= 4
2106397.55682745366319.4387589582101182.35958186366273.012670718
2095719.55653232366350.3894844512095038.64057147366396.815572691
#Sta/Elev= 30
       0   22.58    1045   22.71  1399.4   19.85  1422.4    17.1  1852.3   18.21
  2219.9   15.04    775015.87843 7766.29    6.58  7813.8    6.58    785015.78977
  7956.4   16.54  8031.9   24.97  8176.3   28.36  8572.5   30.41  8878.7   28.74
  9059.2   30.95    9289   26.94  9564.6   28.12  9725.5   29.23    9778   31.53
  9799.6   30.01  9886.4   30.88 10070.1   36.44 10339.2   39.94 10766.1   41.75
 11098.3   45.79 11259.5   43.14 11282.5   45.05 11305.6   41.84 11361.3   43.19
#Mann= 3 ,0,0
       0     .12       0    7750    .041       0    7850     .12       0
Bank Sta=7750,7850
XS Rating Curve= 0 ,0
Exp/Cntr(USF)=0,0
Exp/Cntr=0.3,0.1

Type RM Length L Ch R = 1 ,85462   ,2617.4,2617.4,2617.4
XS GIS Cut Line= 3
2106396.93542404363503.8041623472099505.29078866364086.196666745
  2095946.225484364798.009727677
#Sta/Elev= 30
       0   36.18   218.1   36.52   540.8   31.38     659   27.33  1169.9   24.49
  1713.3   18.15  1861.5    18.5  2154.6    13.7  2991.1   12.43  3350.1   13.96
  5408.5   12.88    687014.48625 6897.76    6.02 6956.29    6.02    697014.50333
  7867.4   15.06  8024.4      20  8456.1   20.75  8760.7   25.58  9554.2   32.22
    9801   31.71  9824.9   33.12  9881.8   28.22   10163      36 10236.6   36.79
 10253.3   33.72 10281.5   35.72 10310.2   33.46 10326.9   36.0510545.76   38.63
#Mann= 3 ,0,0
       0     .12       0    6870    .041       0    6970     .12       0
Bank Sta=6870,6970
XS Rating Curve= 0 ,0
Exp/Cntr(USF)=0,0
Exp/Cntr=0.3,0.1

Type RM Length L Ch R = 1 ,82845   ,2203.7,2203.7,2203.7
XS GIS Cut Line= 4
2106299.87000664362403.7294318162104876.24388478 362339.01915355
2100540.65524092362177.2434578832095687.38437094 363439.09388408
#Sta/Elev= 30
       0   35.25   728.1   21.25  2061.7    13.6  4636.3   12.21  5027.1    14.8
  5139.1   12.735586.82113.15396 5625.24    5.37 5672.39    5.375686.82113.30377
  7498.9   12.78  7631.1   17.12  7651.4   14.98  7787.1   15.77  7834.6   18.72
    7963   17.76  8268.2   23.02  8458.1   21.98  8654.8   24.44    8787   22.93
  8833.9    25.5  8915.9   24.42  9092.2   27.09 10041.7   27.26 10055.2   23.98
 10065.4   25.71 10129.8   26.32 10431.6    27.2 10638.5   26.5810778.33   23.46
#Mann= 3 ,0,0
       0     .12       05586.821    .041       05686.821     .12       0
Bank Sta=5586.821,5686.821
XS Rating Curve= 0 ,0
Exp/Cntr(USF)=0,0
Exp/Cntr=0.3,0.1

Type RM Length L Ch R = 1 ,80641   ,1673.9,1673.9,1673.9
XS GIS Cut Line= 4
2106043.70142807 360642.752451782101182.44207423 360642.75245178
 2100503.1394571360557.8396246392095535.73906933362065.042306397
#Sta/Elev= 30
       0   44.15   441.6   32.28   500.7   27.65     819   21.02  1787.2   13.09
  2151.4   15.38  2328.7   13.34  2548.5    14.1    2834   16.94  3145.8   24.44
  3342.7   22.02  3519.9   17.17  3585.6   12.88  3726.7   11.355170.20611.55534
 5193.38    4.86 5241.73    4.865270.20611.58589  6414.5   13.53  7511.9   11.97
  8427.2   13.66  8471.8   15.87  8492.4   13.91  8533.5    16.6  8554.1   14.14
  9034.8   14.75  9397.8   19.33 10035.7   21.45 10207.1   24.76 10736.9   28.99
#Mann= 3 ,0,0
       0     .12       05170.206    .041       05270.206     .12       0
Bank Sta=5170.206,5270.206
XS Rating Curve= 0 ,0
Exp/Cntr(USF)=0,0
Exp/Cntr=0.3,0.1

Type RM Length L Ch R = 1 ,78967   ,1132.2,1132.2,1132.2
XS GIS Cut Line= 4
2105258.25777701358201.5086714672101882.97289815358902.039495383
 2100205.9445621359411.5164582312095302.22879469360748.893485707
#Sta/Elev= 30
       0   24.01   838.7   14.36  1247.6   16.93  2028.6   11.69  2219.6   15.75
  2923.5   16.96  3208.4   15.74  3335.7   11.534141.57110.59565 4173.95     4.4
 4220.34     4.44241.57110.63325  5790.9   11.51  5974.6    14.6    6012   11.81
  6175.2   11.34  6318.1   13.82  6362.3   10.73  6406.4   13.81  6556.2   10.78
    6580   13.35    6995   11.38  7013.6   14.33  7062.7   11.57  7460.7    11.5
  9372.4   16.62    9784   23.85  9855.4   22.74 10151.4   34.7210282.74   36.63
#Mann= 3 ,0,0
       0     .12       04141.571    .041       04241.571     .12       0
Bank Sta=4141.571,4241.571
XS Rating Curve= 0 ,0
Exp/Cntr(USF)=0,0
Exp/Cntr=0.3,0.1

Type RM Length L Ch R = 1 ,77835   ,817.9,817.9,817.9
XS GIS Cut Line= 4
 2104111.9346106357522.2060543372099845.06504675358350.106118965
2096108.90065254358923.2677021682094813.98003863359284.147217519
#Sta/Elev= 30
       0   22.58   417.7   21.22   835.5   14.74   978.3   14.84  1109.7   10.85
    1474   14.72  2473.6   19.15  2577.2   17.97  2654.1   11.31    303511.03299
  3071.3       4 3119.82    3.99    313510.11057    4242    9.92  4448.6   11.92
  4823.7    10.4  4976.5   12.92    5252   10.28  5414.3   11.96    6222   10.22
  7748.4   13.19  7897.9   15.31  7984.2   15.19  8004.1   13.07  8077.2   16.18
    8161   14.55  8668.7   17.76  9125.3   17.44  9407.9   24.949470.586   24.36
#Mann= 3 ,0,0
       0     .12       0    3035    .041       0    3135     .12       0
Bank Sta=3035,3135
XS Rating Curve= 0 ,0
Exp/Cntr(USF)=0,0
Exp/Cntr=0.3,0.1

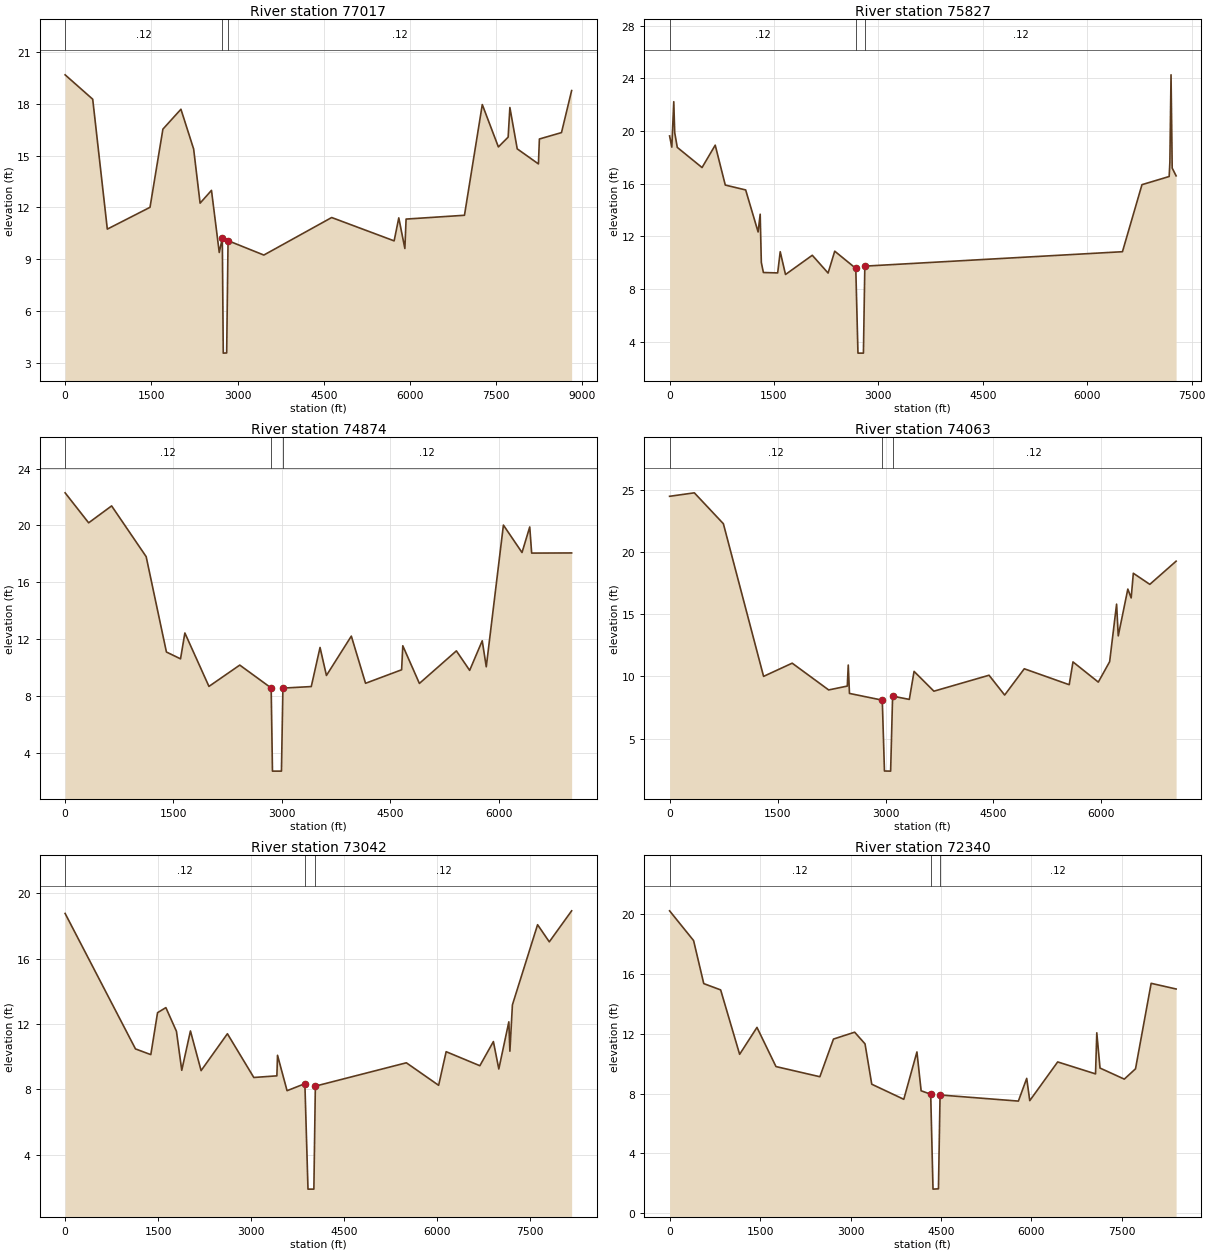
Type RM Length L Ch R = 1 ,77017   ,1190.2,1190.2,1190.2
XS GIS Cut Line= 4
2103719.85250626357044.0968831052100627.32658961357379.108622936
2095876.54498006358231.4916030132095024.16199999358432.052304208
#Sta/Elev= 30
       0   19.67   480.2   18.26   734.3   10.75  1477.1   12.01  1701.5   16.53
  2015.1   17.68  2236.3   15.38  2348.5   12.25  2546.6   12.99  2681.9     9.4
    273510.22525  2751.7    3.58 2810.91    3.59    283510.08146  3457.8    9.25
  4638.1   11.42  5724.7   10.07  5805.5    11.4  5911.4    9.63  5932.7   11.33
  6948.3   11.55  7258.4   17.95  7538.5    15.5  7708.5   16.07  7738.5   17.78
  7866.4   15.39  8235.3   14.52  8252.1   15.96  8636.5   16.338812.922   18.76
#Mann= 3 ,0,0
       0     .12       0    2735    .041       0    2835     .12       0
Bank Sta=2735,2835
XS Rating Curve= 0 ,0
Exp/Cntr(USF)=0,0
Exp/Cntr=0.3,0.1

Type RM Length L Ch R = 1 ,75827   ,952.8,952.8,952.8
XS GIS Cut Line= 6
2103484.77253227356585.643760793 2102409.3881305356342.559731688
2101850.75576887356271.4910918842101200.12087369356311.763392387
2097028.31291086356773.2007179292096279.54032397356915.172039683
#Sta/Elev= 30
       0   19.62    31.9   18.77      60   22.22    73.5   19.87   110.5   18.75
   466.4   17.22   655.5   18.92   800.2   15.89  1092.9   15.52  1271.7   12.33
  1301.5   13.68    1318   10.01  1347.8    9.25  1552.9    9.22  1589.3   10.83
  1665.4     9.1  2050.1   10.56    2277    9.21  2372.6   10.87    26759.566566
 2706.35    3.13 2784.84    3.13    28059.734908  6506.2   10.83  6786.7   15.92
  7177.5   16.54  7187.5   17.61  7204.2   24.26  7220.9   17.18  7277.1   16.59
#Mann= 3 ,0,0
       0     .12       0    2675    .041       0    2805     .12       0
Bank Sta=2675,2805
XS Rating Curve= 0 ,0
Exp/Cntr(USF)=0,0
Exp/Cntr=0.3,0.1

Type RM Length L Ch R = 1 ,74874   ,811.4,811.4,811.4
XS GIS Cut Line= 6
2103563.33853893356122.9023916632102439.46191877355741.479447767
2100828.15808317355532.0491173452099585.11723442355535.141277814
2097678.49577922355601.6040459542096639.78637301355746.062602483
#Sta/Elev= 30
       0   22.29   325.8   20.18   643.8   21.37  1122.1    17.8  1402.5   11.09
  1597.9   10.61  1657.9   12.43  1991.3    8.67  2417.9   10.17 2852.64    8.56
 2870.41    2.71 2994.83    2.71    30158.550438  3407.7    8.66  3529.1   11.41
  3617.7    9.44  3962.3   12.21  4159.2    8.89  4658.4    9.84  4674.8   11.53
  4904.7    8.88  5416.6   11.17  5600.5     9.8  5774.5   11.88  5830.3   10.05
  6067.7   20.02  6325.2   18.09  6432.2   19.89  6458.7   18.05  7012.1   18.06
#Mann= 3 ,0,0
       0     .12       0 2852.64    .041       0    3015     .12       0
Bank Sta=2852.64,3015
XS Rating Curve= 0 ,0
Exp/Cntr(USF)=0,0
Exp/Cntr=0.3,0.1

Type RM Length L Ch R = 1 ,74063   ,1021,1021,1021
XS GIS Cut Line= 6
2103682.61513281355697.0549044052102284.70829131355122.464937907
2100677.49266574354792.8194410942099999.66209378354803.752192255
2097708.15364479354935.6286455442096807.74356719 355079.52451163
#Sta/Elev= 30
       0   24.47   343.8   24.75   747.2   22.27  1305.9   10.01  1703.3   11.07
  2210.3    8.92  2468.9    9.23  2482.3   10.92  2499.1    8.64    29558.099456
 2985.25    2.41 3071.13     2.4 3098.528.422089  3330.9    8.16  3396.7   10.41
  3672.3    8.82  4438.2    10.1  4655.3    8.51  4928.1   10.62  5552.2    9.34
  5604.7   11.17  5956.4    9.55  6114.1   11.19  6210.4   15.81  6233.6   13.26
  6366.6   17.02  6413.3   16.31    6443   18.29  6672.3    17.4  7037.4   19.26
#Mann= 3 ,0,0
       0     .12       0    2955    .041       0 3098.52     .12       0
Bank Sta=2955,3098.52
XS Rating Curve= 0 ,0
Exp/Cntr(USF)=0,0
Exp/Cntr=0.3,0.1

Type RM Length L Ch R = 1 ,73042   ,702.4,702.4,702.4
XS GIS Cut Line= 6
2104580.48483008 355241.062238682101661.80877761353965.224877458
2101171.16157919353868.206247267 2100082.3226075354092.234792296
2097823.82905937354594.7347783322096794.35129549 354866.19170869
#Sta/Elev= 30
       0   18.77  1135.9   10.47  1383.4   10.12    1492   12.69  1626.4      13
  1796.9   11.55  1882.8    9.16  2022.9   11.57    2195    9.14  2619.6    11.4
  3045.7    8.72    3418    8.82  3428.5   10.08  3582.4    7.91    3870 8.34008
 3920.28    1.88 4015.14    1.88 4039.05    8.19  5507.9    9.62    6029    8.24
  6150.1    10.3  6694.3    9.44  6912.9   10.92  7000.3    9.24  7162.1   12.13
  7179.1   10.33  7219.8   13.17    7626   18.08  7815.1   17.03  8175.6   18.93
#Mann= 3 ,0,0
       0     .12       0    3870    .041       0 4039.05     .12       0
Bank Sta=3870,4039.05
XS Rating Curve= 0 ,0
Exp/Cntr(USF)=0,0
Exp/Cntr=0.3,0.1

Type RM Length L Ch R = 1 ,72340   ,1313.4,1313.4,1313.4
XS GIS Cut Line= 6
2104641.45660154354877.0331971342101692.11568816353517.983834757
2100893.78222901353339.0597686792099760.68197156  353489.0289204
2098619.17759005 353758.006675212096722.45335365354443.507094647
#Sta/Elev= 30
       0   20.23     398   18.24   566.7   15.36   846.7   14.94  1161.5   10.63
    1449   12.43  1764.3    9.81  2491.9    9.13  2717.6   11.65  3068.8   12.11
  3240.8   11.33  3352.3    8.63  3883.7    7.62  4101.7   10.79  4171.3    8.19
    43307.960487 4368.31    1.61 4458.54    1.63 4485.35    7.91    5784     7.5
  5922.2    9.02  5972.8    7.53  6435.8   10.12  7063.4    9.32  7084.3   12.07
  7137.8    9.71  7540.5    8.97  7726.5    9.66  7985.9   15.38  8399.6      15
#Mann= 3 ,0,0
       0     .12       0    4330    .041       0 4485.35     .12       0
Bank Sta=4330,4485.35
XS Rating Curve= 0 ,0
Exp/Cntr(USF)=0,0
Exp/Cntr=0.3,0.1

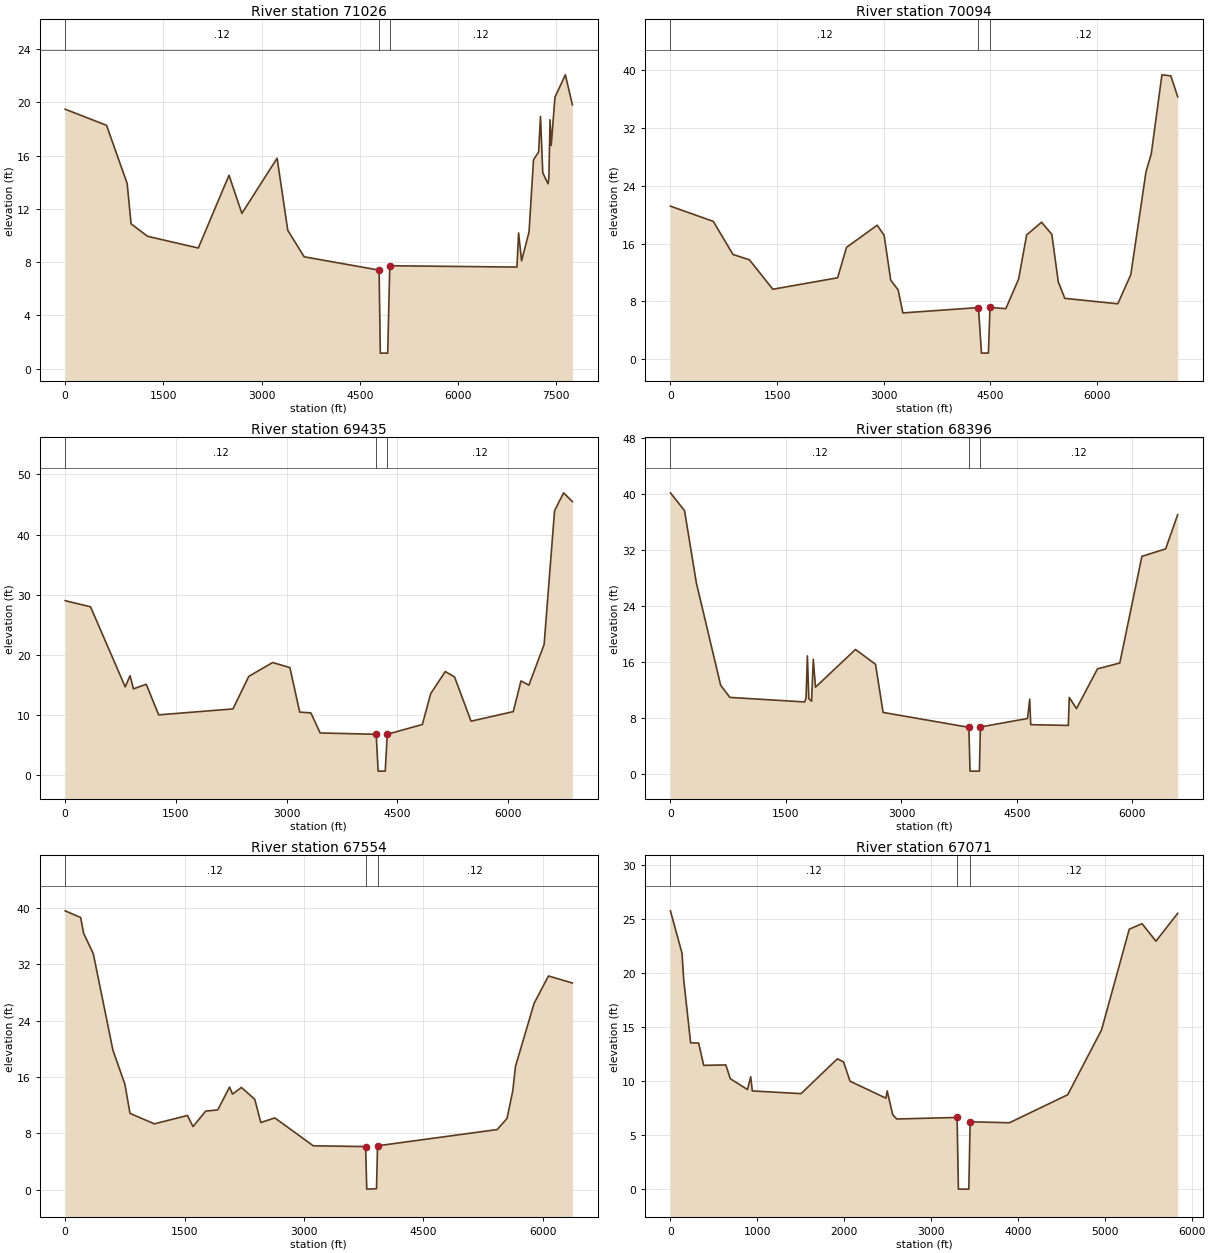
Type RM Length L Ch R = 1 ,71026   ,932,932,932
XS GIS Cut Line= 6
2104500.83237574354502.2540987692102059.37782849353224.823799985
2100860.60817398352609.7235453542100308.18738998352348.740765757
2099630.38953622351822.9891955322098164.55244227350216.185473509
#Sta/Elev= 30
       0   19.48   632.4   18.27   947.2    13.9  1006.5   10.88  1258.3    9.94
  2033.5    9.06  2502.8   14.52  2699.1   11.66  3237.4    15.8  3399.9   10.39
  3650.8     8.4  4794.8     7.4 4813.52    1.17  4926.2    1.17  4958.17.728683
  6900.1    7.63  6925.6   10.19  6971.1     8.1  7085.2   10.27  7153.2   15.68
  7231.3   16.27  7259.9   18.94  7294.6   14.71  7374.6   13.88  7387.9   14.32
  7405.7   18.69  7423.5   16.76  7481.2   20.38  7639.7   22.06  7747.3   19.81
#Mann= 3 ,0,0
       0     .12       0  4794.8    .041       0  4958.1     .12       0
Bank Sta=4794.8,4958.1
XS Rating Curve= 0 ,0
Exp/Cntr(USF)=0,0
Exp/Cntr=0.3,0.1

Type RM Length L Ch R = 1 ,70094   ,659,659,659
XS GIS Cut Line= 4
2104436.01786635354160.1425241452102459.03756485352876.263836931
2100652.50396726351583.2095389232098728.33976301 349899.56586021
#Sta/Elev= 30
       0   21.16   602.7   19.06   879.8   14.49  1111.3   13.75  1440.2    9.69
  2351.7   11.27  2476.7   15.47  2908.5   18.53  3005.4   17.15  3099.1   10.94
  3203.1     9.6  3269.6    6.42  4333.2    7.16 4375.27     .87 4473.31     .88
    44957.172149  4718.3    7.01  4897.7    11.1  5011.1   17.19  5220.8   18.94
  5364.8   17.27  5455.9   10.72  5547.5    8.43  6293.2    7.68  6476.3   11.71
    6690   25.91  6764.2   28.39  6913.8   39.29  7038.9   39.15  7135.7   36.27
#Mann= 3 ,0,0
       0     .12       0  4333.2    .041       0    4495     .12       0
Bank Sta=4333.2,4495
XS Rating Curve= 0 ,0
Exp/Cntr(USF)=0,0
Exp/Cntr=0.3,0.1

Type RM Length L Ch R = 1 ,69435   ,1039,1039,1039
XS GIS Cut Line= 5
 2104668.4043109353865.4570101392103846.66691624353225.991559639
2102131.87292103351894.7699054612101242.87252992351244.294252948
 2099285.9100722349593.448827716
#Sta/Elev= 30
       0   29.01   343.8   27.99   814.2   14.66   879.3   16.53   925.7   14.34
  1099.2    15.1  1267.3   10.01  2274.1      11  2488.7   16.42  2812.8   18.72
  3045.5   17.87  3178.6   10.47  3329.6   10.34  3455.6       7    42156.777931
 4241.53     .65 4337.39     .65    43656.781381  4840.6    8.41  4953.4   13.54
    5151   17.22  5276.8   16.32  5500.4    8.96  6072.3   10.55  6177.1   15.66
  6284.4   14.96  6490.5   21.72  6632.2   43.97  6754.4   46.95  6873.9   45.49
#Mann= 3 ,0,0
       0     .12       0    4215    .041       0    4365     .12       0
Bank Sta=4215,4365
XS Rating Curve= 0 ,0
Exp/Cntr(USF)=0,0
Exp/Cntr=0.3,0.1

Type RM Length L Ch R = 1 ,68396   ,842,842,842
XS GIS Cut Line= 3
2104785.08390592353190.3239595122101855.10659491350457.136169394
2099777.88387442348926.551006928
#Sta/Elev= 30
       0   40.19   183.1   37.64   336.3   27.32   652.1   12.66   772.2   10.92
  1742.9   10.27  1760.9   10.82  1778.3   16.86    1797   10.74  1832.7   10.38
  1855.1   16.38  1883.6   12.38  2402.9   17.78    2663   15.66  2761.7    8.77
    38756.639429 3890.62    .372 4012.31    .372    40256.689871  4636.9     7.9
  4665.5   10.67  4678.7    7.02  5166.9    6.91  5179.1   10.92  5272.9    9.32
    5546   15.01  5835.4   15.84  6122.2    31.1  6430.6   32.17  6587.1   37.07
#Mann= 3 ,0,0
       0     .12       0    3875    .041       0    4025     .12       0
Bank Sta=3875,4025
XS Rating Curve= 0 ,0
Exp/Cntr(USF)=0,0
Exp/Cntr=0.3,0.1

Type RM Length L Ch R = 1 ,67554   ,483.1,483.1,483.1
XS GIS Cut Line= 3
2105036.53718261352753.0139130932102423.60965525349877.700357889
2100444.78169521348368.980697743
#Sta/Elev= 30
       0   39.62     195   38.67   231.7   36.44   353.6   33.53   599.9   19.85
   751.3   14.96   814.7   10.86  1120.3    9.37    1537   10.56  1606.4    8.98
  1766.1   11.18  1917.6   11.35  2065.9    14.6    2103   13.59  2214.6   14.54
  2382.4   12.86  2458.5    9.56  2635.1   10.21    3118    6.25    37756.143803
 3789.86      .1 3912.11     .15    39256.251347  5428.5    8.56  5552.2   10.14
  5624.8   14.06  5657.6    17.5  5891.7   26.46  6072.6   30.37  6373.6   29.37
#Mann= 3 ,0,0
       0     .12       0    3775    .041       0    3925     .12       0
Bank Sta=3775,3925
XS Rating Curve= 0 ,0
Exp/Cntr(USF)=0,0
Exp/Cntr=0.3,0.1

Type RM Length L Ch R = 1 ,67071   ,535.9,535.9,535.9
XS GIS Cut Line= 3
2105016.33473616351978.5532578462102532.84558371349346.594645189
2100845.69262688347902.391714141
#Sta/Elev= 30
       0   25.76     133   21.84   152.1   19.44   232.3   13.53   324.3   13.51
   383.2   11.44   637.4   11.48   689.7    10.2     887     9.2   924.2   10.38
   942.7    9.07  1503.8    8.82  1922.4   12.05  1993.2   11.75  2067.8    9.97
  2480.9     8.4  2495.3    9.07  2558.6    6.87  2605.2    6.47    33006.612388
    3315    -.03    3435    -.03    34506.212595  3902.8    6.12  4573.7    8.72
  4962.6   14.72  5282.2   24.06  5429.1   24.57  5588.9   22.95  5839.5   25.53
#Mann= 3 ,0,0
       0     .12       0    3300    .041       0    3450     .12       0
Bank Sta=3300,3450
XS Rating Curve= 0 ,0
Exp/Cntr(USF)=0,0
Exp/Cntr=0.3,0.1