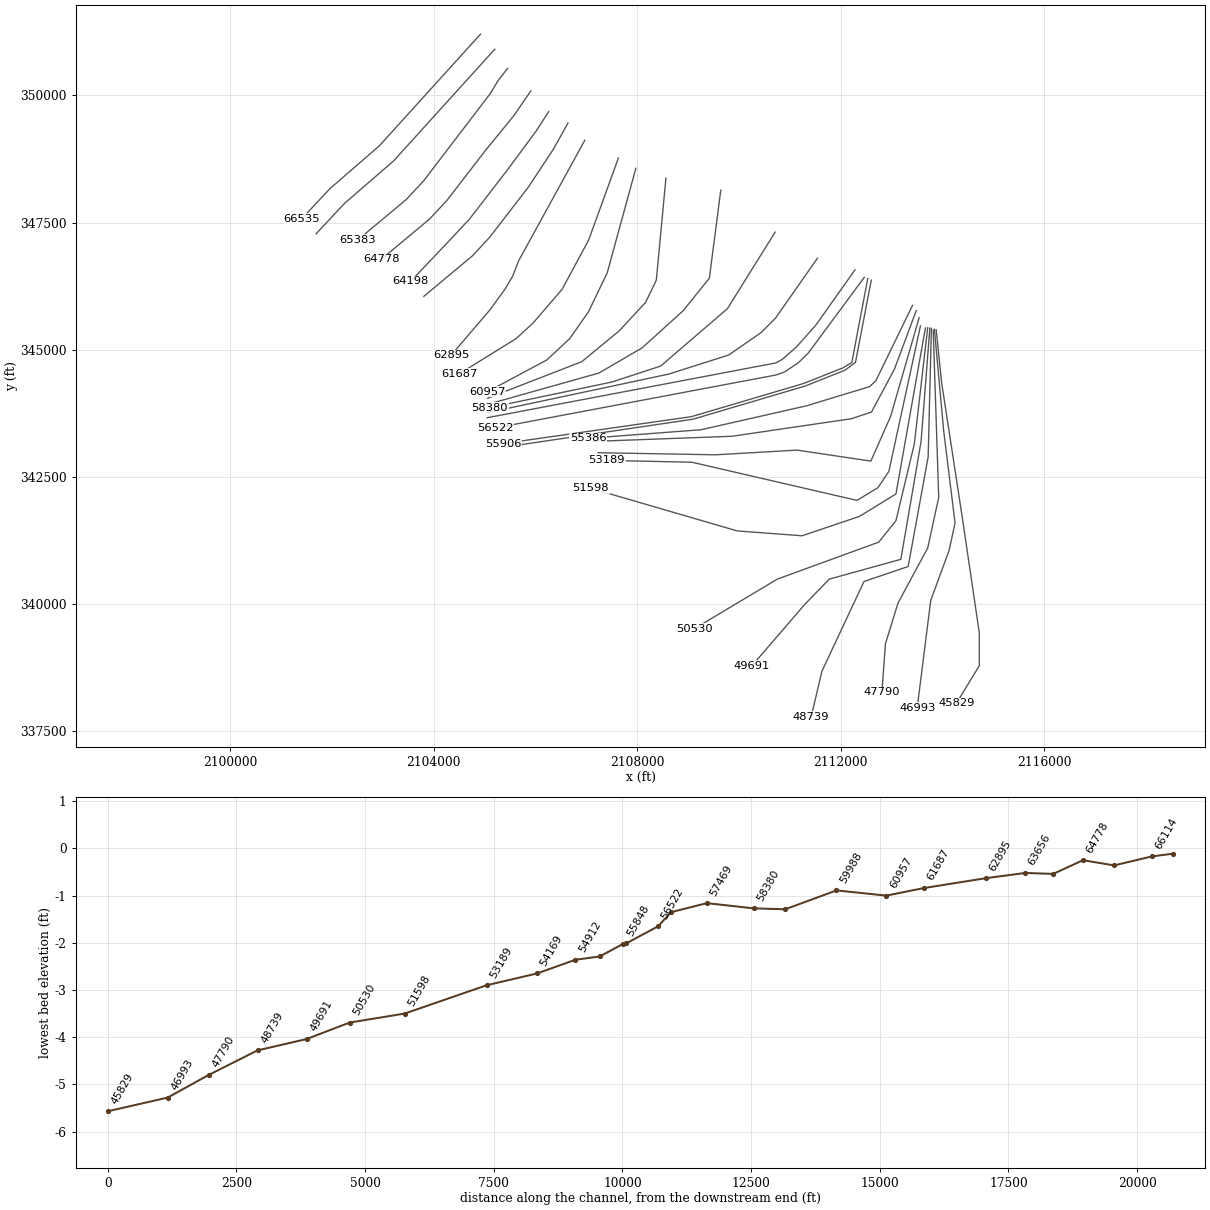
HEC-RAS study AshepooRiver.prj: S-15-41 over Ashepoo River

--- AshepooRiver.g05 (geometry) --- (continued)

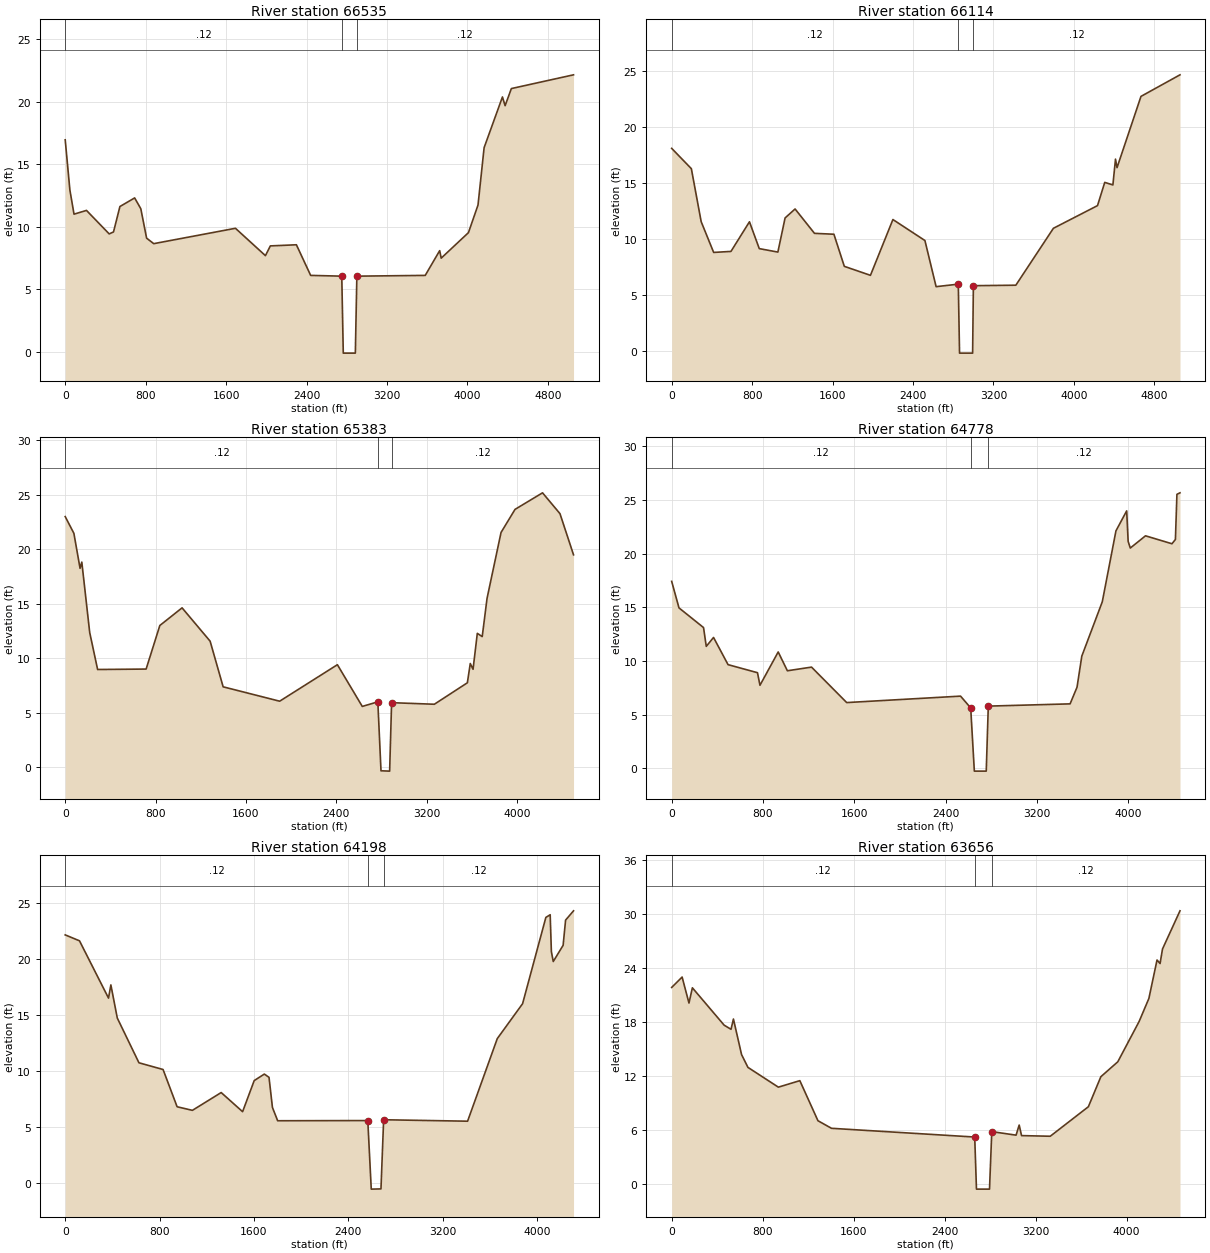
Type RM Length L Ch R = 1 ,66535   ,421.1,421.1,421.1
XS GIS Cut Line= 5
2104919.42897314351202.4621204592102931.07946149349007.530841367
2101969.18310683348174.7480913592101762.60133939347955.733161985
2101408.81412269347575.326226796
#Sta/Elev= 30
       0   16.96    46.6   12.94    87.6   11.01   211.6   11.31   437.4    9.43
   480.4    9.59     544   11.62   690.6   12.31   751.9   11.44   809.4    9.09
   880.3    8.65  1692.7    9.88  1990.9    7.69  2039.8    8.47  2298.9    8.56
  2440.6    6.11    27506.049471    2765    -.11    2885    -.11    29006.049471
  3579.8    6.11  3723.6    8.09  3738.7    7.49  4009.5    9.53  4104.7   11.74
  4165.4   16.33  4347.7   20.39  4374.2   19.69  4436.3   21.06  5054.5   22.16
#Mann= 3 ,0,0
       0     .12       0    2750    .041       0    2900     .12       0
Bank Sta=2750,2900
XS Rating Curve= 0 ,0
Exp/Cntr(USF)=0,0
Exp/Cntr=0.3,0.1

Type RM Length L Ch R = 1 ,66114   ,730.7,730.7,730.7
XS GIS Cut Line= 5
2105200.84078447350906.7282358382103212.49127282348711.796956746
2102250.59491816347879.0142067382102044.01315072347659.999277365
2101690.22593402347279.592342175
#Sta/Elev= 30
       0   18.07   195.7   16.26   293.4   11.54   417.5     8.8   589.5    8.89
   773.5   11.53   870.9    9.14    1056    8.83  1127.7   11.87  1227.1   12.67
    1420    10.5  1613.3   10.42  1716.7    7.56  1976.6    6.76  2199.9   11.73
  2518.2    9.86  2629.4    5.75    28505.973382 2862.49    -.17  2992.5    -.17
    30005.837326  3422.2    5.88  3795.8   10.95  4234.3   12.97  4306.3   15.04
  4387.3   14.81  4413.1   17.11  4428.4   16.35  4666.6    22.7  5054.5   24.62
#Mann= 3 ,0,0
       0     .12       0    2850    .041       0    3000     .12       0
Bank Sta=2850,3000
XS Rating Curve= 0 ,0
Exp/Cntr(USF)=0,0
Exp/Cntr=0.3,0.1

Type RM Length L Ch R = 1 ,65383   ,605.7,605.7,605.7
XS GIS Cut Line= 6
2105451.07381229350530.1259079532105264.97539394350287.841441331
2105110.69420985 350033.553074562103802.92056539348320.054379324
2103460.76951306347952.0806060652102508.91532765347158.908634768
#Sta/Elev= 30
       0   23.01    76.9   21.47   131.5   18.26     147   18.83     217   12.36
     287    8.97   716.3    9.01   837.7   13.01  1034.6   14.63  1282.9   11.57
  1398.1    7.38  1898.5    6.06  2409.6    9.41  2629.9    5.58  2767.5       6
 2795.61    -.33 2872.13    -.362889.3975.924609    3268    5.78  3560.2    7.75
  3585.9    9.52  3610.5    8.99  3648.2   12.29  3691.7   11.99  3734.4    15.5
  3858.3   21.55  3982.1   23.67  4225.6   25.19  4379.9   23.28    4500    19.5
#Mann= 3 ,0,0
       0     .12       0  2767.5    .041       02889.397     .12       0
Bank Sta=2767.5,2889.397
XS Rating Curve= 0 ,0
Exp/Cntr(USF)=0,0
Exp/Cntr=0.3,0.1

Type RM Length L Ch R = 1 ,64778   ,579.5,579.5,579.5
XS GIS Cut Line= 6
2105909.72849235350087.8721371012105579.00780553 349605.21654921
2105023.86638157348925.1271643062104262.09611412347937.408088715
2103919.94506179347569.4343154562102968.09087638346776.262344159
#Sta/Elev= 30
       0   17.41    64.2   14.94   279.1   13.11     303   11.36   366.7   12.19
   493.7    9.66   751.5    8.91   773.3    7.74   932.9   10.84  1013.4    9.09
  1224.8    9.43  1532.9    6.13  2529.9    6.73  2618.9    5.63  2650.7    -.25
 2754.93    -.25 2772.91     5.8  3489.3    6.01    3550    7.56  3591.8   10.45
  3771.3   15.51  3890.9   22.11  3984.9   23.97  3997.7   21.13  4016.5   20.51
  4149.8   21.65  4381.4   20.91  4411.7   21.31  4424.9   25.51  4451.8   25.65
#Mann= 3 ,0,0
       0     .12       0  2618.9    .041       0 2772.91     .12       0
Bank Sta=2618.9,2772.91
XS Rating Curve= 0 ,0
Exp/Cntr(USF)=0,0
Exp/Cntr=0.3,0.1

Type RM Length L Ch R = 1 ,64198   ,541.8,541.8,541.8
XS GIS Cut Line= 6
2106260.49878914349680.3857755222106014.05120195 349298.24870406
2105472.10917914348564.3463760172104710.33891169347576.627300427
2104368.18785936347208.6535271672103548.32768542346344.407857385
#Sta/Elev= 30
       0   22.18   121.1   21.65   367.1   16.53     387   17.71   441.4   14.75
     625   10.75   829.4   10.15   948.4    6.82    1078     6.5  1321.9    8.09
  1503.5    6.38  1601.8    9.16  1687.8    9.74  1727.3    9.45  1756.3    6.76
  1800.6    5.572564.3975.587436 2593.82    -.54 2676.09    -.52 2698.72    5.66
  3410.2    5.53  3661.9   12.91  3876.3   16.03  4073.6   23.74  4110.2   23.98
  4120.4   20.68  4136.3    19.8  4219.9   21.25  4240.8    23.5  4308.1   24.33
#Mann= 3 ,0,0
       0     .12       02564.397    .041       0 2698.72     .12       0
Bank Sta=2564.397,2698.72
XS Rating Curve= 0 ,0
Exp/Cntr(USF)=0,0
Exp/Cntr=0.3,0.1

Type RM Length L Ch R = 1 ,63656   ,761.5,761.5,761.5
XS GIS Cut Line= 6
2106639.91538697349455.4434211342106352.85425779348941.312338199
2105861.67916247348197.2566246582105099.90889502347209.537549068
2104757.75784269346841.5637758082103805.90365728346048.391804512
#Sta/Elev= 30
       0   21.83    91.9   22.98   152.1    20.1   182.1   21.79   461.3   17.65
   521.9   17.19     543   18.33   614.5   14.39   670.6   12.97     938   10.78
  1126.8    11.5  1286.1    7.06  1405.3    6.222664.3975.251529 2679.74    -.52
 2794.45    -.522814.3975.853982  3027.9    5.46  3055.4    6.58  3076.1    5.41
  3328.5    5.34  3663.6    8.61  3773.6   11.94  3922.3   13.59  4110.3   18.07
  4195.7   20.61  4267.2   24.87    4294   24.48  4315.4   26.09  4469.2   30.32
#Mann= 3 ,0,0
       0     .12       02664.397    .041       02814.397     .12       0
Bank Sta=2664.397,2814.397
XS Rating Curve= 0 ,0
Exp/Cntr(USF)=0,0
Exp/Cntr=0.3,0.1

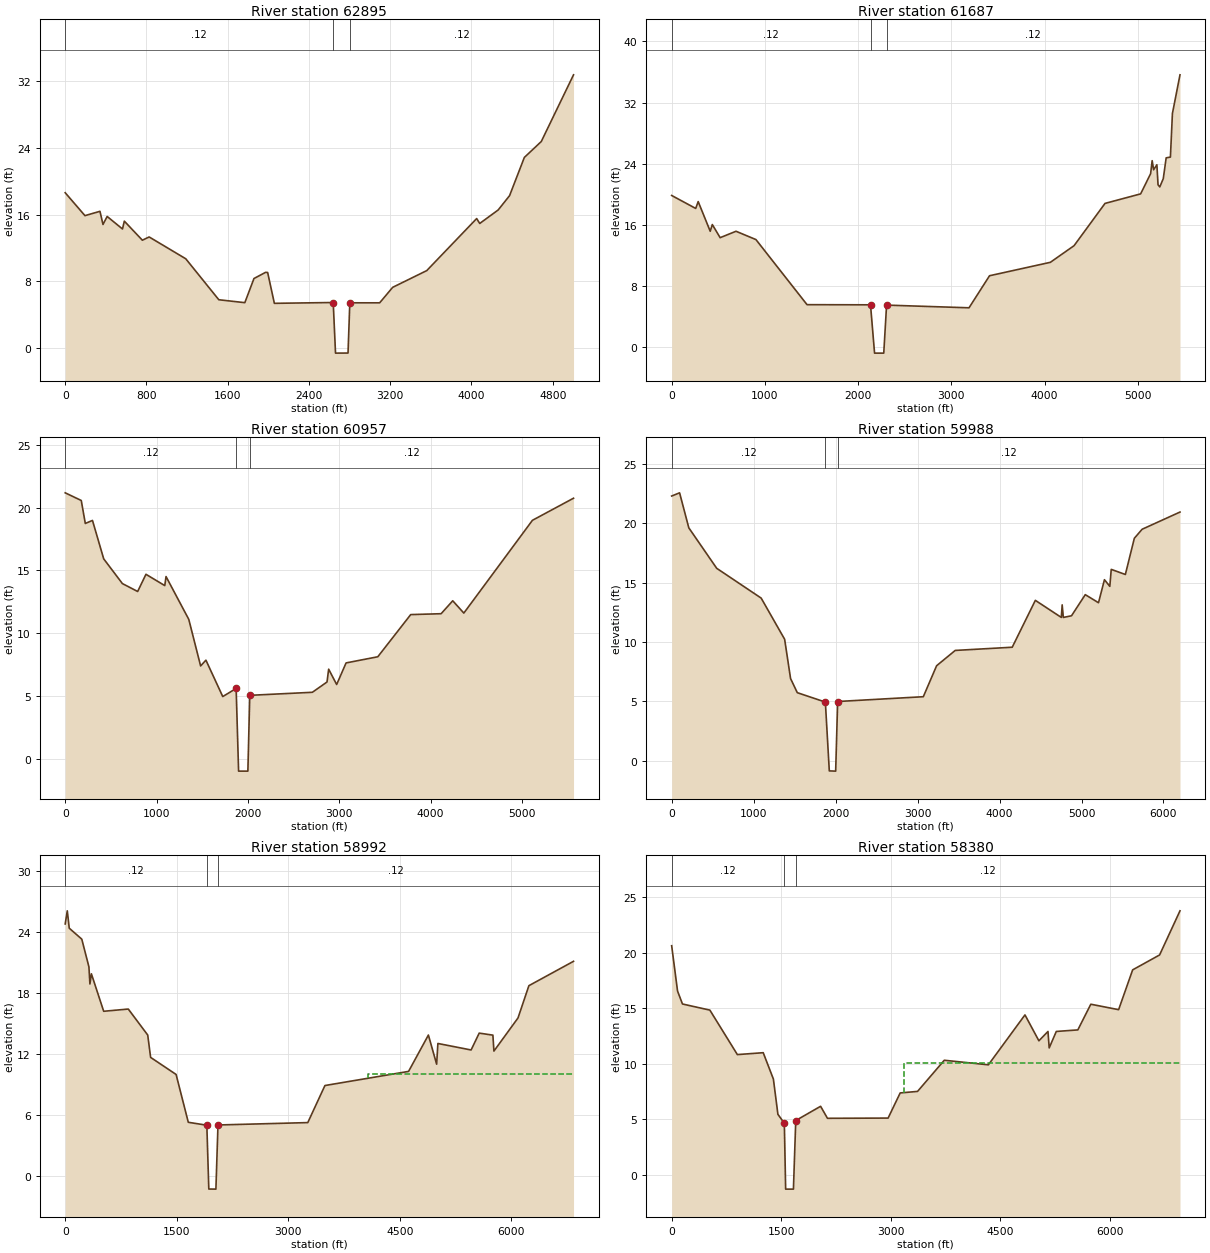
Type RM Length L Ch R = 1 ,62895   ,1208.3,1208.3,1208.3
XS GIS Cut Line= 6
2106971.16762549349118.6353251632105668.00875549346744.728572319
2105552.85570614346446.1605709182105408.38327427346199.065693092
2105106.05692631345783.8167286512104341.20857382344889.364607303
#Sta/Elev= 30
       0   18.63   194.5   15.88   342.3    16.4   372.1   14.82   413.1   15.78
     564   14.28   582.2   15.22   759.7   12.93   826.8   13.32  1187.1    10.7
  1512.5    5.78  1768.7    5.43  1858.7    8.33  1972.9    9.07  1993.4    9.05
  2059.5    5.352639.0085.448291 2661.63    -.63 2784.71    -.62  2802.45.411972
  3096.3    5.41  3224.5    7.27    3560    9.28  4051.4   15.53  4081.6   14.94
  4263.1   16.56  4375.4   18.28  4520.9   22.87  4687.6   24.78  5005.2   32.79
#Mann= 3 ,0,0
       0     .12       02639.008    .041       0  2802.4     .12       0
Bank Sta=2639.008,2802.4
XS Rating Curve= 0 ,0
Exp/Cntr(USF)=0,0
Exp/Cntr=0.3,0.1

Type RM Length L Ch R = 1 ,61687   ,729.3,729.3,729.3
XS GIS Cut Line= 6
2107631.10497338348767.652928333 2107046.5754343347156.298112087
2106523.02960873346185.5518378322105958.50709774345530.207926267
2105621.25247013345218.5302854072104507.20787529  344528.6153287
#Sta/Elev= 30
       0   19.82   257.9   18.12   284.4   19.02   413.5   15.13     436   16.01
   519.8   14.29   690.2   15.13   903.8   14.04  1451.9    5.51 2132.67    5.49
 2176.17    -.84 2274.74    -.84    23055.451851  3189.2     5.1  3409.3     9.3
  4061.6   11.06  4315.9   13.24  4647.9   18.78  5030.1   20.03  5137.1   22.68
  5153.6   24.38    5169   23.19  5204.1   23.84  5216.6   21.22  5235.3   20.94
  5272.7   22.02  5303.8   24.75  5349.3   24.85  5370.8   30.56  5452.1   35.63
#Mann= 3 ,0,0
       0     .12       0 2132.67    .041       0    2305     .12       0
Bank Sta=2132.67,2305
XS Rating Curve= 0 ,0
Exp/Cntr(USF)=0,0
Exp/Cntr=0.3,0.1

Type RM Length L Ch R = 1 ,60957   ,969.4,969.4,969.4
XS GIS Cut Line= 6
2107974.03011954348566.1976154132107411.41057779 346511.09306813
2107043.38284408345745.963747439 2106676.2036752345220.885833417
2106224.69277549 344798.982205822105057.85128235344174.523806138
#Sta/Elev= 30
       0   21.17   175.7   20.56     220   18.73   298.5   18.97   421.4   15.91
   625.9   13.94   793.1   13.31   883.8   14.68  1089.8   13.78  1103.5    14.5
  1352.5   11.09  1482.1    7.38  1540.1    7.84  1724.3    4.94 1870.875.583691
 1897.71      -1 1999.23      -1    20205.037807    2705    5.28  2865.4     6.1
  2883.6    7.12    2971     5.9  3074.1    7.62  3421.2    8.11  3781.5   11.47
  4114.3   11.54  4241.5   12.57  4362.9   11.59  5113.6   18.98  5563.5   20.74
#Mann= 3 ,0,0
       0     .12       0 1870.87    .041       0    2020     .12       0
Bank Sta=1870.87,2020
XS Rating Curve= 0 ,0
Exp/Cntr(USF)=0,0
Exp/Cntr=0.3,0.1

Type RM Length L Ch R = 1 ,59988   ,995.7,995.7,995.7
XS GIS Cut Line= 6
2108565.32228052348371.6293052752108376.18519788346366.723367857
2108166.34421596345931.3629740592107645.84183687345368.922193977
2106910.35740571344764.4410710632105062.22230429344046.441724679
#Sta/Elev= 30
       0   22.29    96.6   22.56     209   19.61   549.5    16.2  1091.8   13.69
  1378.2   10.22  1450.5    6.91  1532.7    5.72    1875  4.9276 1923.02    -.87
 2000.65    -.89    2025 4.97617    3070    5.38  3232.1    7.99  3459.3    9.28
  4154.7    9.55  4436.8    13.5  4753.6   12.06  4763.9   13.12  4778.2   12.06
    4878    12.2  5045.8   13.98  5207.2    13.3  5279.7   15.24  5345.1   14.68
  5362.7   16.11  5534.7   15.68  5644.4   18.73  5739.4   19.49  6201.4   20.94
#Mann= 3 ,0,0
       0     .12       0    1875    .041       0    2025     .12       0
Bank Sta=1875,2025
XS Rating Curve= 0 ,0
Exp/Cntr(USF)=0,0
Exp/Cntr=0.5,0.3

Type RM Length L Ch R = 1 ,58992   ,612.6,612.6,612.6
XS GIS Cut Line= 6
2109643.36416889348136.061039782 2109419.2208664346405.377529302
2108901.83713806345764.4344459052108097.35273658345035.840382716
2107248.48796725344541.4190195852105134.72207127343946.508637072
#Sta/Elev= 30
       0   24.82    27.9   26.11    54.4    24.4   223.1   23.32   319.1   20.59
   332.4   18.91   352.2   19.91   517.7   16.22   848.6   16.44    1110   13.88
  1148.9   11.68  1491.6      10  1655.7    5.29    19055.002243 1931.73   -1.28
 2027.04   -1.29    20555.025343  3262.9    5.26  3493.7    8.91  4618.7    10.3
  4885.3   13.88  4996.1   11.01  5013.1   13.05  5459.7   12.41  5568.8   14.07
  5752.9   13.87  5766.6    12.3  6090.5   15.56  6237.1   18.74  6837.5   21.14
#Mann= 3 ,0,0
       0     .12       0    1905    .041       0    2055     .12       0
#XS Ineff= 2 , 0
                            4079           10.03
Permanent Ineff=
       F       F
Bank Sta=1905,2055
XS Rating Curve= 0 ,0
Exp/Cntr(USF)=0,0
Exp/Cntr=0.5,0.3

Type RM Length L Ch R = 1 ,58380   ,910.6,910.6,910.6
XS GIS Cut Line= 5
2110712.77288746347311.8579898082109773.11276474345805.532602232
2108460.91386474344677.8068074582107503.50920049344364.812564901
2105104.22212249343861.947563075
#Sta/Elev= 30
       0   20.62    80.6   16.54   148.1   15.38   523.3   14.83   900.1   10.83
  1254.4      11  1393.6    8.63  1455.5    5.46 1543.58    4.65 1561.55   -1.27
 1668.17   -1.27    17004.898249  2040.4    6.18  2134.4     5.1  2965.2    5.12
  3130.8    7.38  3368.8    7.52  3734.8   10.32  4339.1    9.91  4840.4    14.4
  5031.2   12.07  5155.6   12.91  5172.3   11.43  5269.6   12.91  5564.6   13.05
  5742.4   15.36  6123.4   14.87  6315.7   18.45  6684.6   19.79  6964.3   23.76
#Mann= 3 ,0,0
       0     .12       0 1543.58    .041       0    1700     .12       0
#XS Ineff= 2 , 0
                            3179           10.03
Permanent Ineff=
       F       F
Bank Sta=1543.58,1700
XS Rating Curve= 0 ,0
Exp/Cntr(USF)=0,0
Exp/Cntr=0.5,0.3

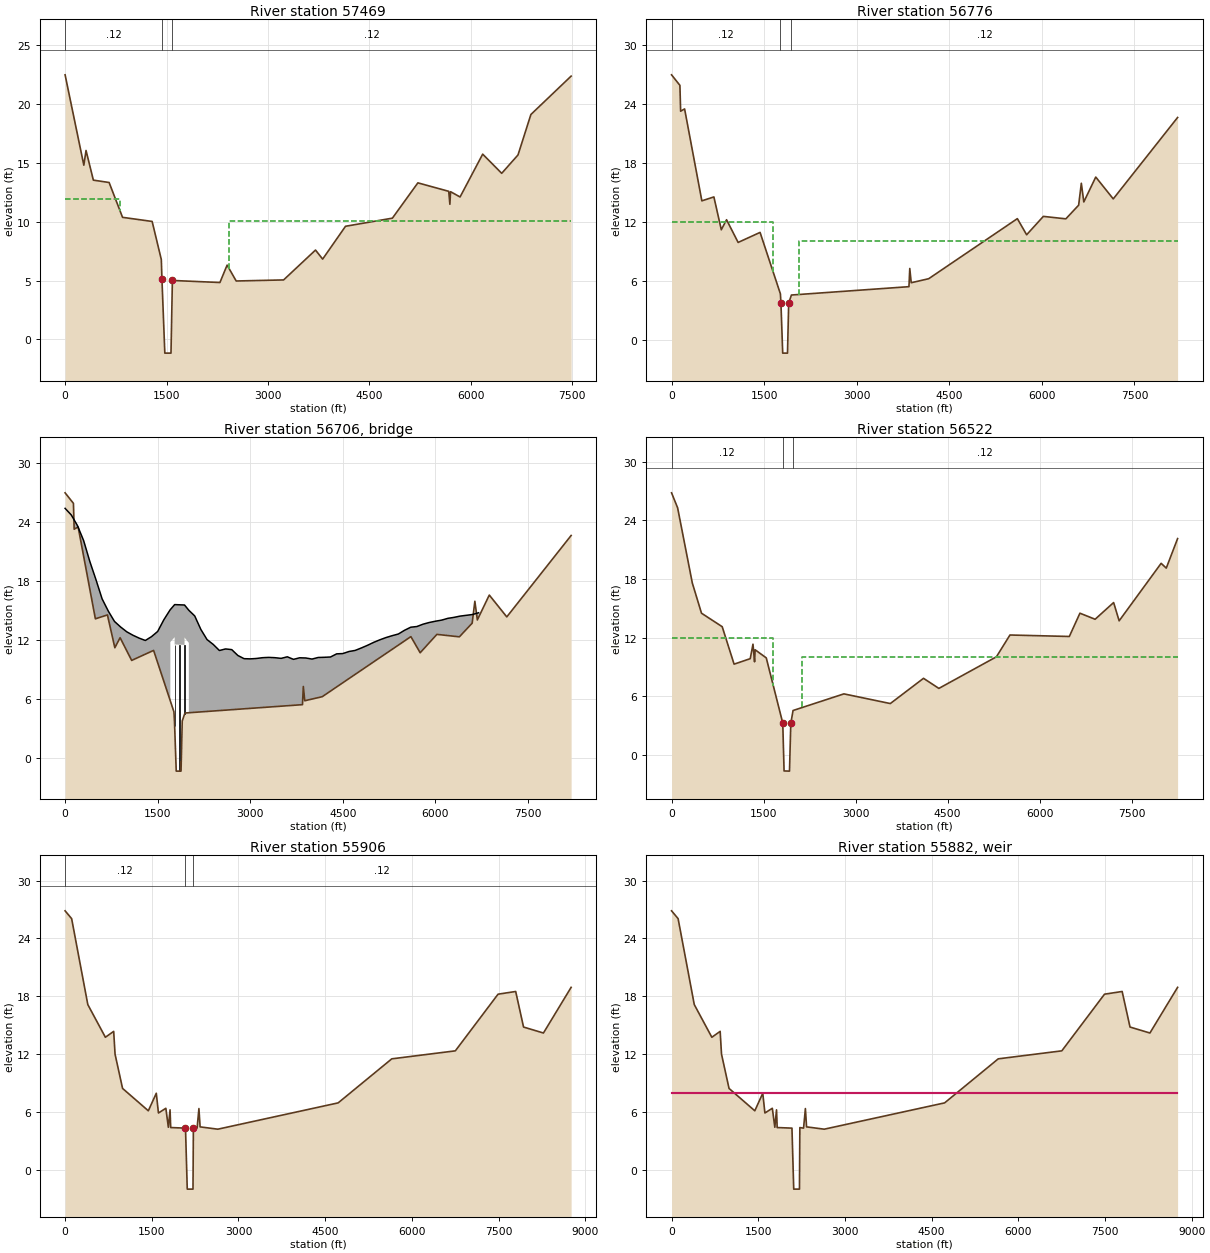
Type RM Length L Ch R = 1 ,57469   ,692.5,692.5,692.5
XS GIS Cut Line= 6
 2111543.9979528346799.4654006252110720.29886494345621.270508605
2110432.87640412345334.4647799842109800.23240003344896.283538183
2108623.27742312  344521.24242642105070.32233361343764.748045568
#Sta/Elev= 30
       0   22.49   277.2   14.81   309.7   16.06   418.2   13.54   651.1   13.34
   849.8   10.38  1287.4   10.03  1423.1    6.79 1432.21    5.13  1474.9   -1.16
 1566.09   -1.16  1586.85.015964  2289.7    4.84  2396.2    6.32  2530.4    4.97
  3231.5    5.06  3703.4     7.6  3808.9    6.83  4147.1    9.62  4840.5   10.31
  5217.1   13.31  5673.7   12.59  5690.5   11.49  5700.5   12.56  5841.1   12.11
  6175.8   15.75  6456.9   14.12  6697.9   15.68  6888.7   19.12  7483.6   22.38
#Mann= 3 ,0,0
       0     .12       0 1432.21    .041       0  1586.8     .12       0
#XS Ineff= 2 , 0
             811   11.95    2429           10.03
Permanent Ineff=
       F       F
Bank Sta=1432.21,1586.8
XS Rating Curve= 0 ,0
Exp/Cntr(USF)=0,0
Exp/Cntr=0.5,0.3

Type RM Length L Ch R = 1 ,56776   ,254.1,254.1,254.1
BEGIN DESCRIPTION:
HEC-2 RS: 218448
END DESCRIPTION:
XS GIS Cut Line= 6
2112282.70593525346571.0636307492111510.76004851345480.860592143
2111131.56207502345054.5707431452110853.32104535344810.025185703
2110729.34134793344740.5849727232105051.66105604343662.589639585
#Sta/Elev= 30
       0   26.96   135.3   25.89     147   23.26   211.4   23.49   490.8   14.14
   685.9   14.54     806    11.2   891.1   12.22  1078.6    9.91  1434.1   10.93
  1763.5    4.68 1772.133.742357  1800.8   -1.35 1878.42   -1.35 1897.79    3.75
    1942    4.56  3846.3    5.41  3859.6    7.26  3882.9    5.81  4166.1    6.22
  5602.5   12.33    5753   10.69  6023.8   12.56  6388.3   12.31  6595.6    13.7
    6639   15.93  6679.2   14.03  6872.8   16.56  7156.3   14.34  8198.7   22.62
#Mann= 3 ,-1,0
       0     .12       0  1763.5    .041       0    1942     .12       0
#XS Ineff= 2 , 0
            1648   11.95    2062           10.03
Permanent Ineff=
       F       F
Bank Sta=1772.13,1897.79
XS Rating Curve= 0 ,0
Exp/Cntr(USF)=0,0
Exp/Cntr=0.5,0.3

Type RM Length L Ch R = 3 ,56706   ,,,
BEGIN DESCRIPTION:
S-15-41 over Ashepoo River
END DESCRIPTION:
Bridge Culvert--1,0,-1,-1, 0
Deck Dist Width WeirC Skew NumUp NumDn MinLoCord MaxHiCord MaxSubmerge Is_Ogee
53.74202,30,2.6,0, 73, 73, , , 0.98, 0, 2,2,,
       0     100     200     300     400     500     600     700     800     900
    1000    1100    1200    1300    1400    1500    1600    1700 1704.99    1705
 1774.99    1775    1935 1935.01    2005 2005.01    2100    2200    2300    2400
    2500    2600    2700    2800    2900    3000    3100    3200    3300    3400
    3500    3600    3700    3800    3900    4000    4100    4200    4300    4400
    4500    4600    4700    4800    4900    5000    5100    5200    5300    5400
    5500    5600    5700    5800    5900    6000    6100    6200    6300    6400
    6500    6600    6700
   25.38   24.71   23.63   22.11   19.99   18.13   16.17   14.93   13.88   13.31
   12.82   12.47   12.18   11.94   12.33   12.86   14.05   15.04   15.08   15.08
   15.59   15.59   15.55   15.55   15.01   15.01   14.44   13.06   12.03   11.54
   10.92   11.08   11.01   10.41   10.09   10.07   10.11   10.19   10.22   10.19
   10.12   10.28   10.02   10.18   10.16   10.05   10.21   10.23   10.26   10.58
   10.61   10.82   10.93   11.18   11.45   11.75   12.01   12.24   12.43    12.6
   12.98   13.29   13.36    13.6   13.77    13.9   14.01   14.19   14.29   14.42
    14.5   14.58   14.76
                                                                                
                                                                           11.78
   12.28   11.53   11.49   12.24    11.7
                                                                                
                                                                                
                                                                                
                                                                                
                        
      41     141     241     341     441     541     641     741     841     941
    1041    1141    1241    1341    1441    1541    1641    1741 1745.99    1746
 1815.99    1816    1976 1976.01    2046 2046.01    2141    2241    2341    2441
    2541    2641    2741    2841    2941    3041    3141    3241    3341    3441
    3541    3641    3741    3800    3900    4041    4141    4241    4341    4441
    4541    4641    4741    4841    4941    5041    5141    5241    5341    5441
    5541    5641    5741    5841    5941    6041    6141    6241    6341    6441
    6541    6641    6741
   25.38   24.71   23.63   22.11   19.99   18.13   16.17   14.93   13.88   13.31
   12.82   12.47   12.18   11.94   12.33   12.86   14.05   15.04   15.08   15.08
   15.59   15.59   15.55   15.55   15.01   15.01   14.44   13.06   12.03   11.54
   10.92   11.08   11.01   10.41   10.09   10.07   10.11   10.19   10.22   10.19
   10.12   10.28   10.02   10.18   10.16   10.05   10.21   10.23   10.26   10.58
   10.61   10.82   10.93   11.18   11.45   11.75   12.01   12.24   12.43    12.6
   12.98   13.29   13.36    13.6   13.77    13.9   14.01   14.19   14.29   14.42
    14.5   14.58   14.76
                                                                                
                                                                           11.78
   12.28   11.53   11.49   12.24    11.7
                                                                                
                                                                                
                                                                                
                                                                                
                        
Pier Skew, UpSta & Num, DnSta & Num=  ,1775, 2 ,1816, 2 , 0 , 0 , 0 ,,
       4       4
       3   12.28
       4       4
       2   12.28
Pier Skew, UpSta & Num, DnSta & Num=  ,1855, 2 ,1896, 2 , 0 , 0 , 0 ,,
       4       4
    -1.5   11.53
       4       4
    -1.7   11.53
Pier Skew, UpSta & Num, DnSta & Num=  ,1935, 2 ,1976, 2 , 0 , 0 , 0 ,,
       4       4
     4.5   12.24
       4       4
     4.5   12.24
Abutment Skew #Up #Dn= , 3 , 3
 1704.99    1707 1716.56
    9.78    9.78       5
 1745.99    1748 1757.56
    9.78    9.78       5
Abutment Skew #Up #Dn= , 3 , 3
 1993.59    2003 2005.01
       5     9.7     9.7
 2034.59    2044 2046.01
       5     9.7     9.7
BR Coef=-1 ,-1 ,-1 ,0.9, 0 ,,,0.8,0,1.2,0,
WSPro=,,,, 1 ,,,, 0 ,,,, 0 ,,,,-1 ,-1 ,-1 , 0 , 0 , 0 , 0 , 0
BC Design=,, 0 ,, 0 ,,,,,,
BC Use User HTab Curves=0
BC User HTab FreeFlow(D)= 0

Type RM Length L Ch R = 1 ,56522   ,616.6,616.6,616.6
BEGIN DESCRIPTION:
HEC-2 RS: 218419
END DESCRIPTION:
XS GIS Cut Line= 6
2112465.11983619 346422.549297062111363.13655015344933.468875854
2111165.40341921344740.6376676242110893.85305968344560.725925455
2110725.69108737 344502.288003772105210.34691174343461.561526106
#Sta/Elev= 30
       0   26.81    98.7   25.28   338.2   17.59     488    14.5   825.3   13.12
  1019.1    9.29  1282.2    9.85  1326.9   11.33  1352.7    9.53  1362.2   10.76
  1543.5    9.93 1812.413.262738 1833.62   -1.63 1922.08   -1.65  1943.2    3.23
  1980.2    4.55  2808.6    6.25  3565.2    5.26  4106.1    7.84  4356.5    6.81
  5294.1   10.04    5515   12.27  6482.5   12.12  6655.3    14.5  6902.9   13.88
  7204.5   15.59  7294.5   13.72  7978.7    19.6  8062.5   19.11    8247   22.13
#Mann= 3 ,-1,0
       0     .12       0 1812.41    .041       0  1980.2     .12       0
#XS Ineff= 2 , 0
            1661   11.95    2131           10.03
Permanent Ineff=
       F       F
Bank Sta=1812.41,1943.2
XS Rating Curve= 0 ,0
Exp/Cntr(USF)=0,0
Exp/Cntr=0.5,0.3

Type RM Length L Ch R = 1 ,55906   ,57.8,57.8,57.8
BEGIN DESCRIPTION:
HEC-2 RS: 217655 (LTR N)
END DESCRIPTION:
Node Name=N
XS GIS Cut Line= 6
2112533.15905625346400.8927124982112220.07912493344749.760027028
2112055.98129461344647.4896658622111273.13088891 344336.30716421
2109066.92062286343683.8963280072105367.39154218343155.008802025
#Sta/Elev= 30
       0   26.87   113.3   26.06   393.2   17.14   697.2   13.75   840.9   14.36
   864.4      12   994.6    8.44  1440.4    6.12  1578.2    7.94  1615.4    5.89
  1743.6    6.38  1786.9    4.41  1816.3    6.22  1827.4    4.38 2083.48    4.32
 2113.92   -2.01 2213.14   -2.01    22204.374556  2284.3    4.32  2315.9    6.35
  2336.1    4.45  2642.3    4.21    4725    6.94  5652.9   11.51  6752.9   12.34
  7491.9   18.22  7797.1    18.5  7933.1   14.81  8277.4   14.19  8756.4   18.93
#Mann= 3 ,-1,0
       0     .12       0 2083.48    .041       0    2220     .12       0
Bank Sta=2083.48,2220
XS Rating Curve= 0 ,0
Exp/Cntr(USF)=0,0
Exp/Cntr=0.3,0.1

Type RM Length L Ch R = 5 ,55882   ,,,
IW Pilot Flow=0
#Inline Weir SE= 2
       0       88751.605       8
IW Dist,WD,Coef,Skew,MaxSub,Min_El,Is_Ogee,SpillHt,DesHd
14,16,2.6,0,0.98,, 0 ,,,2,2,
Inline Weir Flap Gates= 0
IW Outlet Rating Curve= 0 ,False,,

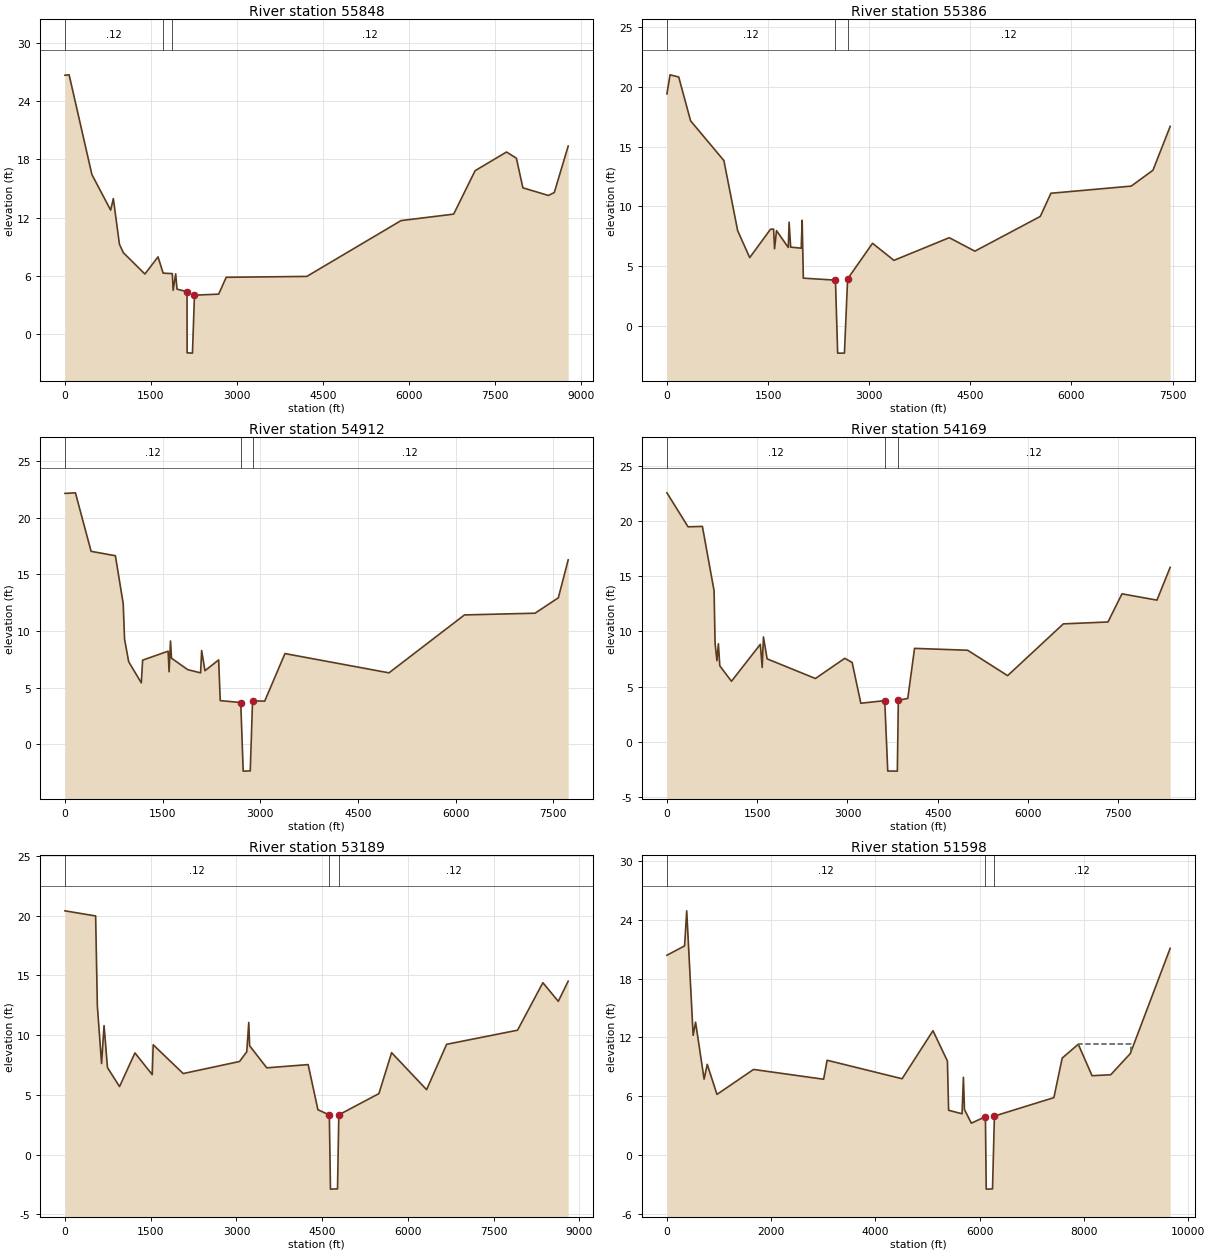
Type RM Length L Ch R = 1 ,55848   ,461.9,461.9,461.9
XS GIS Cut Line= 6
2112602.22771004346368.3947165712112291.51670559344751.338327519
 2112086.1399642 344597.12224529 2111303.2895585344285.939743638
2109097.07929245343633.5289074342105413.49016296343088.701430261
#Sta/Elev= 30
       0   26.71    72.8   26.75   470.2   16.44   797.5   12.76   844.3   13.96
   951.1    9.23  1017.9    8.37    1395    6.16  1624.2    7.93  1713.3    6.25
  1873.8     6.2    1888    4.48  1932.5    6.18  1955.7    4.59    2130    4.33
 2131.85   -1.99 2224.95   -2.02    2260    3.97  2682.7    4.08  2813.6    5.82
  4220.1    5.91  5864.6   11.68  6782.7   12.35  7157.2   16.84  7705.1   18.77
  7877.8   18.13  7990.7   15.07  8435.6   14.28  8538.5   14.58  8781.5   19.39
#Mann= 3 ,-1,0
       0     .12       0  1713.3    .041       0  1873.8     .12       0
Bank Sta=2130,2260
XS Rating Curve= 0 ,0
Exp/Cntr(USF)=0,0
Exp/Cntr=0.3,0.1

Type RM Length L Ch R = 1 ,55386   ,473.7,473.7,473.7
XS GIS Cut Line= 6
2113412.80357095345872.1360190542112692.51382011344389.192395445
2112568.93658486344274.0096954432111325.14543062343895.675353461
2109255.17654151343426.6027141322107037.10774411343258.632919787
#Sta/Elev= 30
       0   19.42      46   21.02   174.8   20.84   350.9   17.17     845   13.84
  1049.3    7.97  1228.1    5.71    1537    8.09    1582     8.1  1596.6    6.45
  1625.4    7.97  1800.2    6.56  1812.4    8.68  1835.5    6.59  1992.1     6.5
  2006.1    8.84  2023.5    3.99    2500 3.82269 2532.68   -2.29 2633.02   -2.29
 2680.38    3.93  3050.2    6.91  3367.6    5.48  4188.1    7.38    4568    6.25
  5538.3    9.16  5696.3    11.1  6887.7    11.7  7209.9   13.03  7465.1    16.7
#Mann= 3 ,-1,0
       0     .12       0    2500    .041       0 2680.38     .12       0
Bank Sta=2500,2680.38
XS Rating Curve= 0 ,0
Exp/Cntr(USF)=0,0
Exp/Cntr=0.3,0.1

Type RM Length L Ch R = 1 ,54912   ,742.9,742.9,742.9
BEGIN DESCRIPTION:
HEC-2 RS: 216847
END DESCRIPTION:
XS GIS Cut Line= 6
2113486.58521938345768.4686934842113057.02499013344616.224982676
2112606.63455243343774.9088022842112213.00337047343643.294728209
2109864.08764517343298.3666103682107113.53128844343196.340419961
#Sta/Elev= 30
       0   22.14   160.9   22.19   401.6   17.03   774.8   16.64   894.7   12.41
   915.5    9.28     979    7.29  1172.3    5.43    1193    7.43  1584.5    8.22
  1599.4    6.41    1621    9.12  1636.7     7.6  1886.1    6.59  2083.4    6.31
  2099.5    8.28  2150.4     6.5  2360.7    7.45  2384.9    3.86    2700    3.69
 2737.58   -2.36 2846.02   -2.34 2881.093.846987  3067.5    3.81    3379    8.01
  4976.3    6.31  6136.1   11.42  7219.6   11.57  7577.5   12.93    7729   16.28
#Mann= 3 ,-1,0
       0     .12       0    2700    .041       0 2881.09     .12       0
Bank Sta=2700,2881.09
XS Rating Curve= 0 ,0
Exp/Cntr(USF)=0,0
Exp/Cntr=0.3,0.1

Type RM Length L Ch R = 1 ,54169   ,980.8,980.8,980.8
BEGIN DESCRIPTION:
HEC-2 RS: 215997
END DESCRIPTION:
XS GIS Cut Line= 6
 2113542.7384924345627.2632154992112982.60128618343689.622050567
2112594.04871233342810.1317107832111140.64623269343026.164538765
2109541.92443561342933.8618398392107232.32289834342975.171662578
#Sta/Elev= 30
       0   22.56   351.7   19.48   589.4   19.52   783.5    13.7   800.5    8.91
   831.1    7.36     855    8.89   878.8    6.89  1072.8    5.49  1552.4    8.84
  1583.5    6.74  1603.9    9.51  1665.2    7.52  2467.9    5.74  2955.8    7.57
  3078.6    7.19  3222.5     3.5    3620 3.73413 3669.99   -2.64 3829.28   -2.65
 3846.123.762544  4003.1    3.94  4115.4    8.47    4998     8.3  5662.3       6
  6588.3   10.69  7330.1   10.86  7563.1   13.41  8144.1   12.84  8363.9   15.81
#Mann= 3 ,-1,0
       0     .12       0    3620    .041       0 3846.12     .12       0
Bank Sta=3620,3846.12
XS Rating Curve= 0 ,0
Exp/Cntr(USF)=0,0
Exp/Cntr=0.3,0.1

Type RM Length L Ch R = 1 ,53189   ,1590.3,1590.3,1590.3
BEGIN DESCRIPTION:
HEC-2 RS: 215090 (LTR M)
END DESCRIPTION:
Node Name=M
XS GIS Cut Line= 6
2113568.81423419345468.007339637 2112947.9376938342607.997925717
2112732.08088266342287.2343462792112321.38115258342037.902023321
2109072.61770797342788.5819753352107403.45554704  342823.5553852
#Sta/Elev= 30
       0   20.41   536.7   19.98   566.8   12.46   640.4    7.62   683.9    10.8
   744.1    7.28   954.8    5.69    1224    8.51  1526.9    6.69  1543.5    9.19
  2068.7    6.78  3053.7    7.79    3180     8.6  3215.6   11.06  3230.4    9.11
  3530.1    7.26  4254.4    7.53  4425.2    3.75    46253.314335 4644.54    -2.9
 4768.05   -2.88 4790.713.322143    5492     5.1  5714.1    8.53  6326.5    5.43
  6676.4    9.23  7916.8   10.41  8360.3   14.39  8629.8   12.83  8803.3   14.52
#Mann= 3 ,-1,0
       0     .12       0    4625    .041       0 4790.71     .12       0
Bank Sta=4625,4790.71
XS Rating Curve= 0 ,0
Exp/Cntr(USF)=0,0
Exp/Cntr=0.3,0.1

Type RM Length L Ch R = 1 ,51598   ,1068.4,1068.4,1068.4
BEGIN DESCRIPTION:
HEC-2 RS: 214067
END DESCRIPTION:
XS GIS Cut Line= 6
2113665.95705568 345426.336509692113086.88115373342163.439416852
2112369.53776723341723.0682256752111241.00129154341342.111761542
2109965.28864871341437.8266651632107086.50153097342275.881131254
#Sta/Elev= 30
       0    20.4   338.9   21.36   379.5   24.94     503   12.22   549.7   13.56
   713.2    7.74   773.5    9.25   960.1    6.18  1661.4    8.73  3006.1    7.73
  3073.2    9.67  4510.9    7.78  5103.9   12.69  5380.9    9.59    5404    4.56
  5661.7     4.2  5687.9    7.93    5708    4.63  5840.1    3.24    61103.904998
 6125.35    -3.5 6246.04   -3.48 6282.263.966102  7423.3    5.85  7582.9    9.89
  7891.5   11.31  8155.4    8.09  8513.9    8.19    8889   10.35  9654.2   21.11
#Mann= 3 ,-1,0
       0     .12       0    6110    .041       0 6282.26     .12       0
#XS Ineff= 1 ,-1
 7904.23 8907.04   11.37
Permanent Ineff=
       T
Bank Sta=6110,6282.26
XS Rating Curve= 0 ,0
Exp/Cntr(USF)=0,0
Exp/Cntr=0.3,0.1

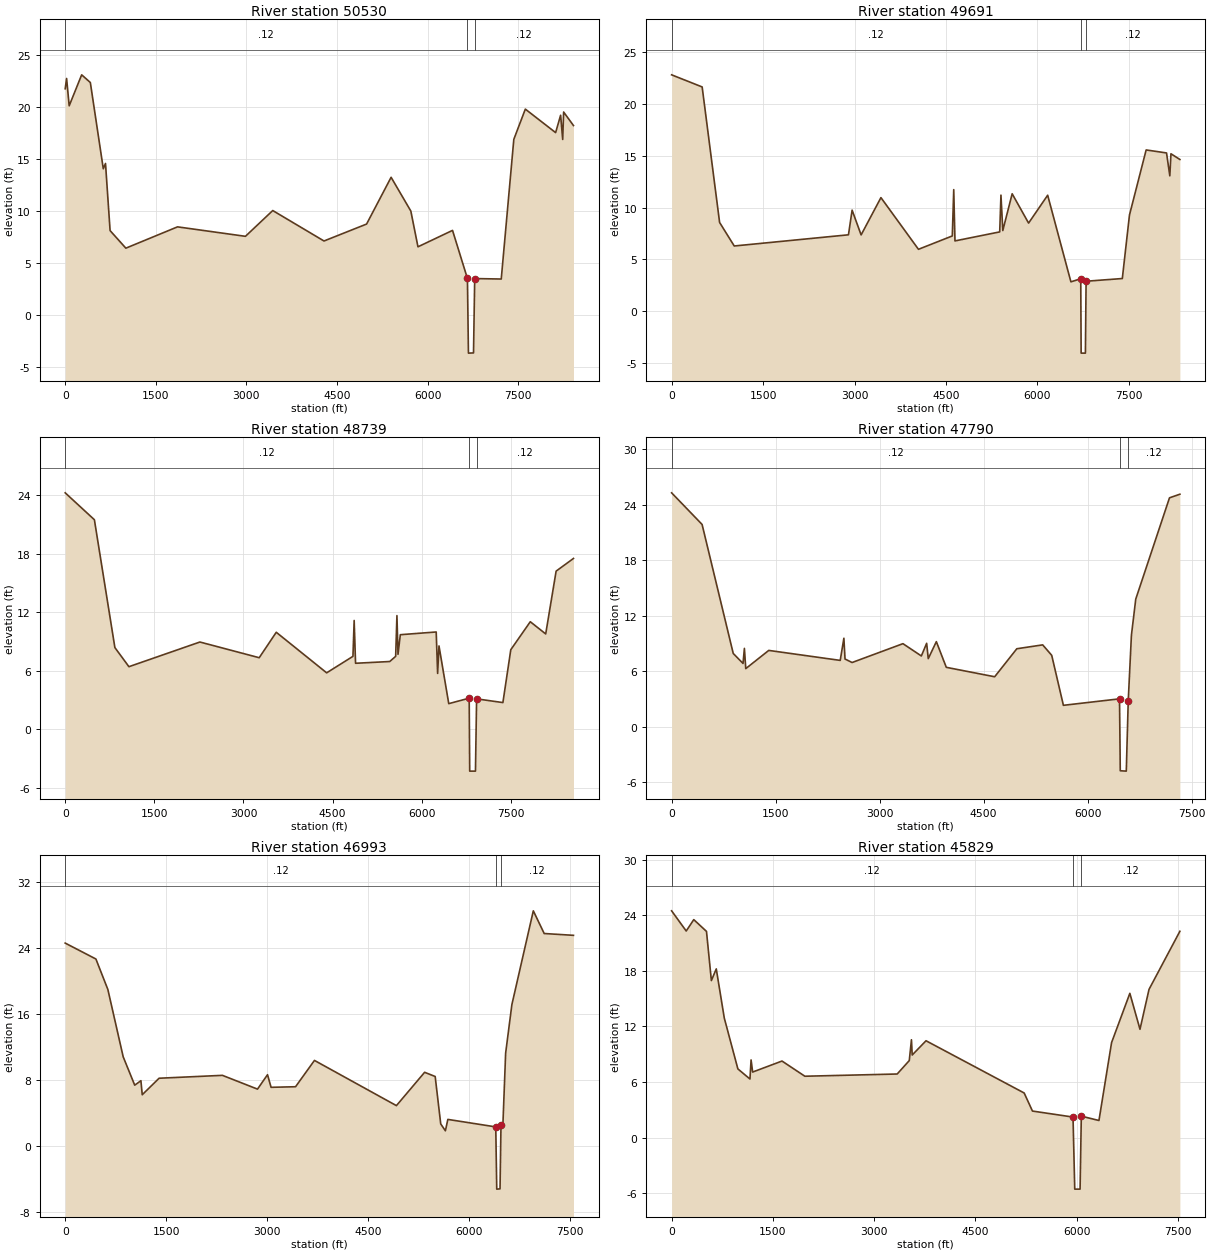
Type RM Length L Ch R = 1 ,50530   ,839.1,839.1,839.1
BEGIN DESCRIPTION:
HEC-2 RS: 213236
END DESCRIPTION:
XS GIS Cut Line= 6
2113710.59355572345430.4006670612113448.33330875343148.228105745
2113086.53357444341637.1573886812112748.97970278 341217.20142283
2110755.64770619340490.302856961 2109124.3484468339515.562594273
#Sta/Elev= 30
       0   21.75    23.1   22.74    66.1   20.11   272.6   23.09   416.2   22.35
   630.7   14.05   667.3   14.56   743.3     8.1  1004.2    6.41  1859.8    8.46
  2984.3    7.55  3436.5   10.03    4285     7.1  4990.1    8.73  5396.3   13.23
  5722.9    9.98  5840.9    6.54  6413.2    8.12    66603.492058 6676.48   -3.69
 6760.69   -3.67 6780.463.485386  7219.8    3.44    7428   16.88  7618.6   19.79
  8120.2   17.53  8202.9    19.2  8237.4   16.87  8252.8   19.51  8415.8   18.21
#Mann= 3 ,-1,0
       0     .12       0    6660    .041       0 6780.46     .12       0
Bank Sta=6660,6780.46
XS Rating Curve= 0 ,0
Exp/Cntr(USF)=0,0
Exp/Cntr=0.3,0.1

Type RM Length L Ch R = 1 ,49691   ,952,952,952
BEGIN DESCRIPTION:
HEC-2 RS: 212304
END DESCRIPTION:
XS GIS Cut Line= 6
2113753.67471267345423.5593204752113580.43345627 343190.64241309
2113183.51759426340879.1236672472111775.48857235340489.480415901
2111290.56987558 339988.659403132110252.98432053338783.358492686
#Sta/Elev= 30
       0   22.82   500.9   21.65   787.2    8.57  1027.4     6.3  2900.5    7.38
  2960.4    9.76  3108.2    7.37    3433   10.97  4048.6    5.98  4603.5    7.27
  4627.1   11.74  4647.4    6.79  5381.2    7.66  5401.5   11.21  5431.7    7.79
  5585.5   11.34  5854.9    8.51  6167.8    11.2  6548.8    2.84    6710 3.13754
 6716.82   -4.04 6786.62   -4.04 6797.952.897896  7392.1    3.16  7509.4    9.29
  7782.9   15.57  8117.3   15.28  8171.1   13.07  8189.7    15.2  8336.2   14.65
#Mann= 3 ,-1,0
       0     .12       0    6710    .041       0 6797.95     .12       0
Bank Sta=6710,6797.95
XS Rating Curve= 0 ,0
Exp/Cntr(USF)=0,0
Exp/Cntr=0.3,0.1

Type RM Length L Ch R = 1 ,48739   ,948.3,948.3,948.3
BEGIN DESCRIPTION:
HEC-2 RS: 211308
END DESCRIPTION:
XS GIS Cut Line= 6
2113784.01759306345418.4051467052113720.27176802342893.723116748
2113327.76276237340738.0580405182112459.28196653340443.410629815
2111632.31338533338680.5684926832111419.26402097337778.426294558
#Sta/Elev= 30
       0   24.26   491.3    21.5   836.3    8.39  1072.6    6.43  2267.3    8.96
  3265.6    7.35  3552.6    9.96  4400.8     5.8  4843.4    7.49  4863.7   11.17
  4887.2    6.78  5462.6    6.96  5562.3    7.49  5583.7   11.67  5601.8     7.7
  5640.9    9.71  6244.7    9.99  6268.6    5.74  6291.6    8.56    6456    2.64
    68003.201209 6808.59   -4.28 6905.56   -4.28 6924.723.132063  7367.3    2.75
  7500.2    8.17  7828.2   11.04  8087.9    9.79  8263.2   16.23  8555.3   17.53
#Mann= 3 ,-1,0
       0     .12       0    6800    .041       0 6924.72     .12       0
Bank Sta=6800,6924.72
XS Rating Curve= 0 ,0
Exp/Cntr(USF)=0,0
Exp/Cntr=0.3,0.1

Type RM Length L Ch R = 1 ,47790   ,797,797,797
BEGIN DESCRIPTION:
HEC-2 RS: 210260
END DESCRIPTION:
XS GIS Cut Line= 6
2113819.67999959345380.3975931412113927.97080106342095.905734601
2113711.50232809341102.1186541492113127.51502048340019.569395021
2112880.30446054339219.3152655542112811.38049324338267.623629299
#Sta/Elev= 30
       0   25.31   439.5   21.89   888.8    7.93    1030    6.85  1049.7    8.48
  1069.4    6.29  1401.1    8.26  2431.8    7.18  2484.6    9.58    2501    7.33
  2602.9    6.95  3336.4    8.99    3602    7.66  3678.4    9.03  3701.6    7.37
  3818.2    9.21  3961.6    6.43  4659.4    5.41    4979    8.44  5351.9    8.86
  5482.1    7.73  5650.7    2.32    64603.021096 6470.79   -4.76 6557.69    -4.8
 6585.91    2.83  6631.7     9.9  6694.2   13.81  7180.9   24.77  7330.7   25.16
#Mann= 3 ,-1,0
       0     .12       0    6460    .041       0 6585.91     .12       0
Bank Sta=6460,6585.91
XS Rating Curve= 0 ,0
Exp/Cntr(USF)=0,0
Exp/Cntr=0.3,0.1

Type RM Length L Ch R = 1 ,46993   ,1164.1,1164.1,1164.1
BEGIN DESCRIPTION:
HEC-2 RS: 209434
END DESCRIPTION:
XS GIS Cut Line= 6
2113842.64379361  345402.5263264 2114026.3655615343394.716572421
2114248.95082345341596.1784298422114134.59979798341062.760749973
2113770.53918435 340068.973669522113505.26959665337962.936515315
#Sta/Elev= 30
       0   24.54   456.4   22.61   634.4   18.91   861.8   10.76  1033.3    7.32
  1125.4    7.86  1145.2    6.16  1395.7    8.16  2336.8    8.51  2858.5    6.84
  3007.3    8.59  3060.2    7.06    3424    7.13    3705   10.32  4923.2    4.84
  5342.6    8.88  5499.5    8.37  5582.1    2.62  5651.4    1.79  5687.8    3.17
    64002.261818 6414.62   -5.28 6463.46   -5.25 6477.612.433743  6507.1    2.75
  6546.8    11.2  6639.6   17.08  6958.3   28.45  7119.9    25.7  7555.2   25.48
#Mann= 3 ,-1,0
       0     .12       0    6400    .041       0 6477.61     .12       0
Bank Sta=6400,6477.61
XS Rating Curve= 0 ,0
Exp/Cntr(USF)=0,0
Exp/Cntr=0.3,0.1

Type RM Length L Ch R = 1 ,45829   ,717.4,717.4,717.4
BEGIN DESCRIPTION:
HEC-2 RS: 208274 (LTR L)
END DESCRIPTION:
Node Name=L
XS GIS Cut Line= 6
2113877.86478229345392.9455559052113984.30492154344357.593753259
2114390.07680005 341709.099288592114726.00750383339431.354087047
 2114725.9193221338789.0864046892114276.75018094338049.327786138
#Sta/Elev= 30
       0   24.48   216.4    22.3   328.5   23.53   516.6   22.26   589.2   16.95
   661.7   18.21   780.5    12.9   981.8    7.41  1160.7    6.32  1177.3    8.38
  1200.5    7.07  1635.5    8.26  1974.1    6.62    3342    6.86  3521.3    8.31
  3553.3   10.56  3564.4    8.91  3769.4   10.45  5223.3    4.81  5346.1    2.86
 5947.11    2.21  5972.7   -5.57 6051.68   -5.57 6069.96    2.31  6331.3    1.84
  6518.3   10.25  6789.1   15.57  6939.3   11.69  7073.2      16  7530.4   22.27
#Mann= 3 ,-1,0
       0     .12       0 5947.11    .041       0 6069.96     .12       0
Bank Sta=5947.11,6069.96
XS Rating Curve= 0 ,0
Exp/Cntr(USF)=0,0
Exp/Cntr=0.5,0.3