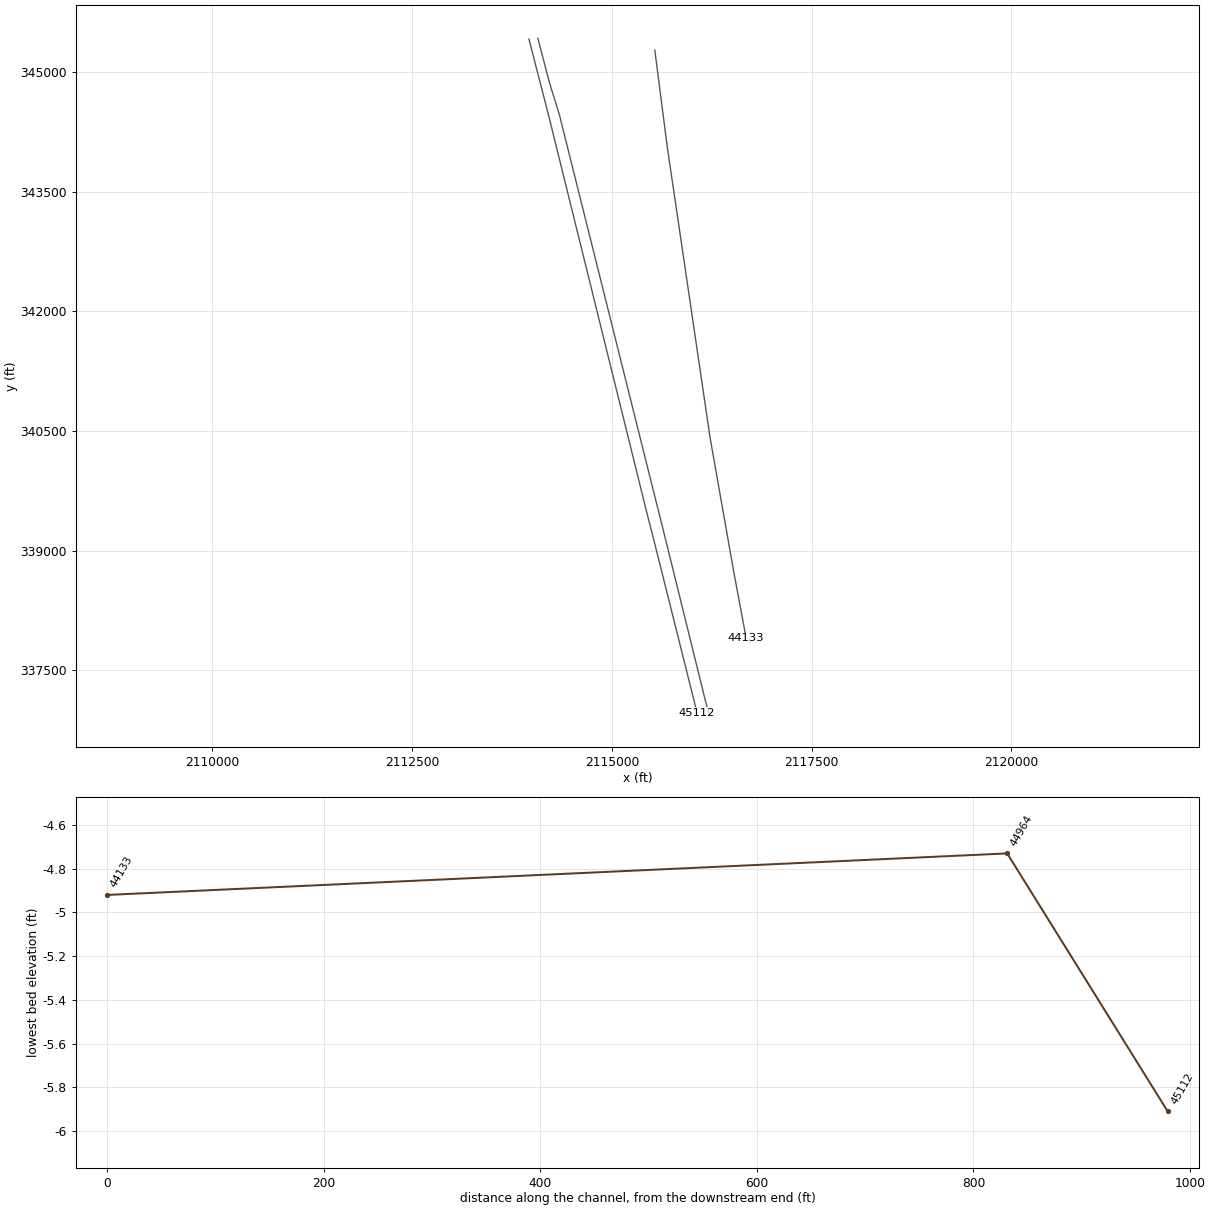
HEC-RAS study AshepooRiver.prj: S-15-41 over Ashepoo River

--- AshepooRiver.g05 (geometry) --- (continued)

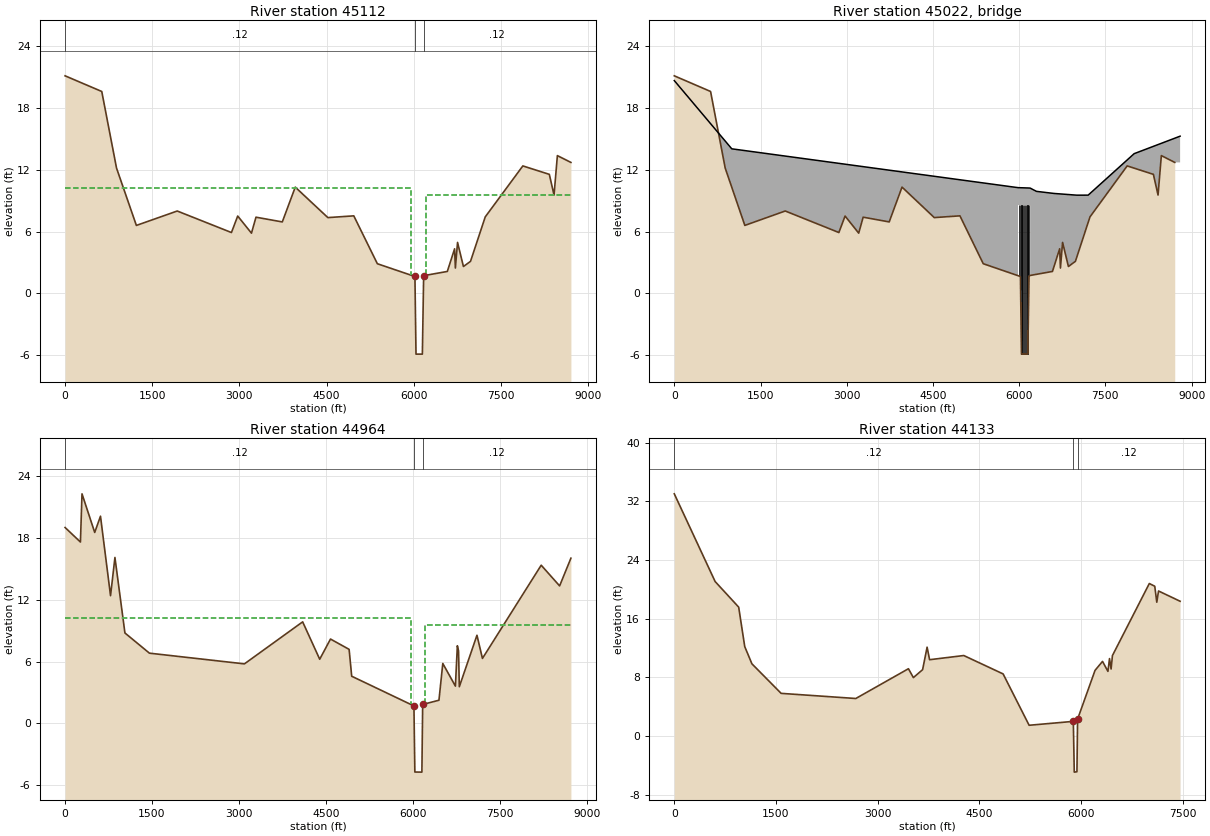
Type RM Length L Ch R = 1 ,45112   ,148.2,148.2,148.2
BEGIN DESCRIPTION:
HEC-2 RS: 207385
END DESCRIPTION:
XS GIS Cut Line= 5
2113961.77074045345415.0293650792114204.83077183344471.731700322
2115437.79764054339477.5591892312115543.63379055339062.969763302
2116067.18892544336966.980577882
#Sta/Elev= 30
       0   21.12   631.4    19.6   885.6   12.16  1227.2    6.59  1930.4    7.99
  2863.3     5.9  2971.5     7.5  3208.1    5.84  3285.9    7.39  3738.9    6.93
    3962   10.31  4523.1    7.35  4969.3    7.52  5374.9    2.87  6021.8    1.63
 6040.13   -5.91 6149.65   -5.91 6171.84    1.71  6579.2    2.12  6704.4    4.32
  6717.9    2.45  6755.2    4.94  6856.6     2.6  6978.4     3.1  7232.1    7.42
  7879.2   12.37  8334.8   11.55    8416    9.54  8473.5   13.37  8706.5   12.71
#Mann= 3 ,-1,0
       0     .12       0  6021.8    .041       0 6171.84     .12       0
#XS Ineff= 2 , 0
            5955   10.27    6215            9.53
Permanent Ineff=
       F       F
Bank Sta=6021.8,6171.84
XS Rating Curve= 0 ,0
Exp/Cntr(USF)=0,0
Exp/Cntr=0.5,0.3

Type RM Length L Ch R = 3 ,45022   ,,,
BEGIN DESCRIPTION:
SC-303 over Ashepoo River
END DESCRIPTION:
Bridge Culvert--1,0,-1,-1, 0
Deck Dist Width WeirC Skew NumUp NumDn MinLoCord MaxHiCord MaxSubmerge Is_Ogee
25,90,2.6,0, 14, 14, , , 0.98, 0, 2,2,,
       0    1000 5979.99    5980    5980    6190    6190 6190.01    6300    6600
    7000    7200    8000    8800
  20.657  14.031   10.26   10.26   10.26   10.22   10.22   10.22     9.9     9.7
    9.53   9.531   13.56   15.26
                                    8.57    8.53
                                
       0    1000 5979.99    5980    5980    6190    6190 6190.01    6300    6900
    7000    7200    8000    8800
  20.657  14.031   10.26   10.26   10.26   10.22   10.22   10.22     9.9     9.7
    9.53   9.531   13.56   15.26
                                    8.57    8.53
                                
Pier Skew, UpSta & Num, DnSta & Num=  ,5995, 2 ,5995, 2 , 0 , 0 , 0 ,,
     1.5     1.5
      -6    9.95
     1.5     1.5
      -6    9.95
Pier Skew, UpSta & Num, DnSta & Num=  ,6010, 2 ,6010, 2 , 0 , 0 , 0 ,,
     1.5     1.5
   -5.91    9.95
     1.5     1.5
   -5.91    9.95
Pier Skew, UpSta & Num, DnSta & Num=  ,6025, 2 ,6025, 2 , 0 , 0 , 0 ,,
     1.5     1.5
      -6    9.95
     1.5     1.5
      -6    9.95
Pier Skew, UpSta & Num, DnSta & Num=  ,6040, 2 ,6040, 2 , 0 , 0 , 0 ,,
     1.5     1.5
   -5.91    9.95
     1.5     1.5
   -5.91    9.95
Pier Skew, UpSta & Num, DnSta & Num=  ,6055, 2 ,6055, 2 , 0 , 0 , 0 ,,
     1.5     1.5
      -6    9.95
     1.5     1.5
      -6    9.95
Pier Skew, UpSta & Num, DnSta & Num=  ,6070, 2 ,6070, 2 , 0 , 0 , 0 ,,
     1.5     1.5
   -5.91    9.95
     1.5     1.5
   -5.91    9.95
Pier Skew, UpSta & Num, DnSta & Num=  ,6085, 2 ,6085, 2 , 0 , 0 , 0 ,,
     1.5     1.5
      -6    9.95
     1.5     1.5
      -6    9.95
Pier Skew, UpSta & Num, DnSta & Num=  ,6100, 2 ,6100, 2 , 0 , 0 , 0 ,,
     1.5     1.5
   -5.91    9.95
     1.5     1.5
   -5.91    9.95
Pier Skew, UpSta & Num, DnSta & Num=  ,6115, 2 ,6115, 2 , 0 , 0 , 0 ,,
     1.5     1.5
      -6    9.95
     1.5     1.5
      -6    9.95
Pier Skew, UpSta & Num, DnSta & Num=  ,6130, 2 ,6130, 2 , 0 , 0 , 0 ,,
     1.5     1.5
   -5.91    9.95
     1.5     1.5
   -5.91    9.95
Pier Skew, UpSta & Num, DnSta & Num=  ,6145, 2 ,6145, 2 , 0 , 0 , 0 ,,
     1.5     1.5
      -6    9.95
     1.5     1.5
      -6    9.95
Pier Skew, UpSta & Num, DnSta & Num=  ,6160, 2 ,6160, 2 , 0 , 0 , 0 ,,
     1.5     1.5
   -5.91    9.95
     1.5     1.5
   -5.91    9.95
Pier Skew, UpSta & Num, DnSta & Num=  ,6175, 2 ,6175, 2 , 0 , 0 , 0 ,,
     1.5     1.5
      -6    9.95
     1.5     1.5
      -6    9.95
Abutment Skew #Up #Dn= , 3 , 3
    5980    5982  5990.7
    6.57    6.57    2.22
    5980    5982  5990.7
    6.57    6.57    2.22
Abutment Skew #Up #Dn= , 3 , 3
 6178.38    6188    6190
    1.72    6.53    6.53
 6178.38    6188    6190
    1.72    6.53    6.53
BR Coef=-1 ,-1 ,-1 ,0.9, 0 ,,,0.8,0,1.2,0,
WSPro=,,,, 1 ,,,, 0 ,,,, 0 ,,,,-1 ,-1 ,-1 , 0 , 0 , 0 , 0 , 0
BC Design=,, 0 ,, 0 ,,,,,,
BC Use User HTab Curves=0
BC User HTab FreeFlow(D)= 0

Type RM Length L Ch R = 1 ,44964   ,831.2,831.2,831.2
BEGIN DESCRIPTION:
HEC-2 RS: 207243
END DESCRIPTION:
XS GIS Cut Line= 6
2114073.47904332  345423.60386612114221.42584184344858.595689091
2114341.76739176344471.5221031752115658.66614636339198.105657315
2116169.30860132337126.505086102 2116213.6270204336961.916215067
#Sta/Elev= 30
       0   19.02   264.9   17.61     292   22.29   511.5   18.54     611   20.12
   784.4    12.4   860.3   16.11  1032.8    8.78  1455.5    6.82  3094.8    5.78
  4099.9    9.86  4394.1    6.23  4580.1    8.19  4901.3    7.19  4946.1    4.58
    60201.697643 6035.72   -4.72 6157.21   -4.73  6170.8    1.84  6451.8    2.25
  6518.1    5.82  6735.6    3.62  6769.4    7.54  6789.7    7.04  6803.2    3.56
  7107.5    8.56  7202.2    6.31  8216.2   15.36  8533.9   13.35  8728.9   16.04
#Mann= 3 ,-1,0
       0     .12       0    6020    .041       0  6170.8     .12       0
#XS Ineff= 2 , 0
            5963   10.27    6207            9.53
Permanent Ineff=
       F       F
Bank Sta=6020,6170.8
XS Rating Curve= 0 ,0
Exp/Cntr(USF)=0,0
Exp/Cntr=0.5,0.3

Type RM Length L Ch R = 1 ,44133   ,,,
BEGIN DESCRIPTION:
HEC-2 RS: 206515 (LTR K)
END DESCRIPTION:
Node Name=K
XS GIS Cut Line= 5
2115537.78628686345276.3727564262115691.65318385344076.177599645
2116229.20633682340420.1299743212116525.06356667338740.926794892
2116681.20054587337905.065912506
#Sta/Elev= 30
       0   33.03   602.4   21.07   949.8   17.58    1039    12.2    1145    9.85
  1576.1    5.82  2677.4    5.12  3453.6    9.18  3526.5    7.97  3662.5    9.05
  3728.9   12.12  3765.6   10.41  4269.6   10.98  4850.1    8.47  5233.7    1.47
 5885.54       2 5899.47   -4.92 5938.86   -4.87 5948.39     2.3  6206.1    8.96
  6316.1   10.18    6396    8.82  6419.4   10.56  6442.7    9.14  6462.7   10.98
  7006.6    20.8  7086.7   20.43  7116.8   18.25  7142.3   19.78  7460.8   18.38
#Mann= 3 ,-1,0
       0     .12       0 5885.54    .041       0 5948.39     .12       0
Bank Sta=5885.54,5948.39
XS Rating Curve= 0 ,0
Exp/Cntr(USF)=0,0
Exp/Cntr=0.3,0.1
LCMann Table=0

--- AshepooRiver.g10 (geometry) ---

Geom Title=Natural Conditions
Program Version=6.60

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
River Reach=River 1         ,Reach 1

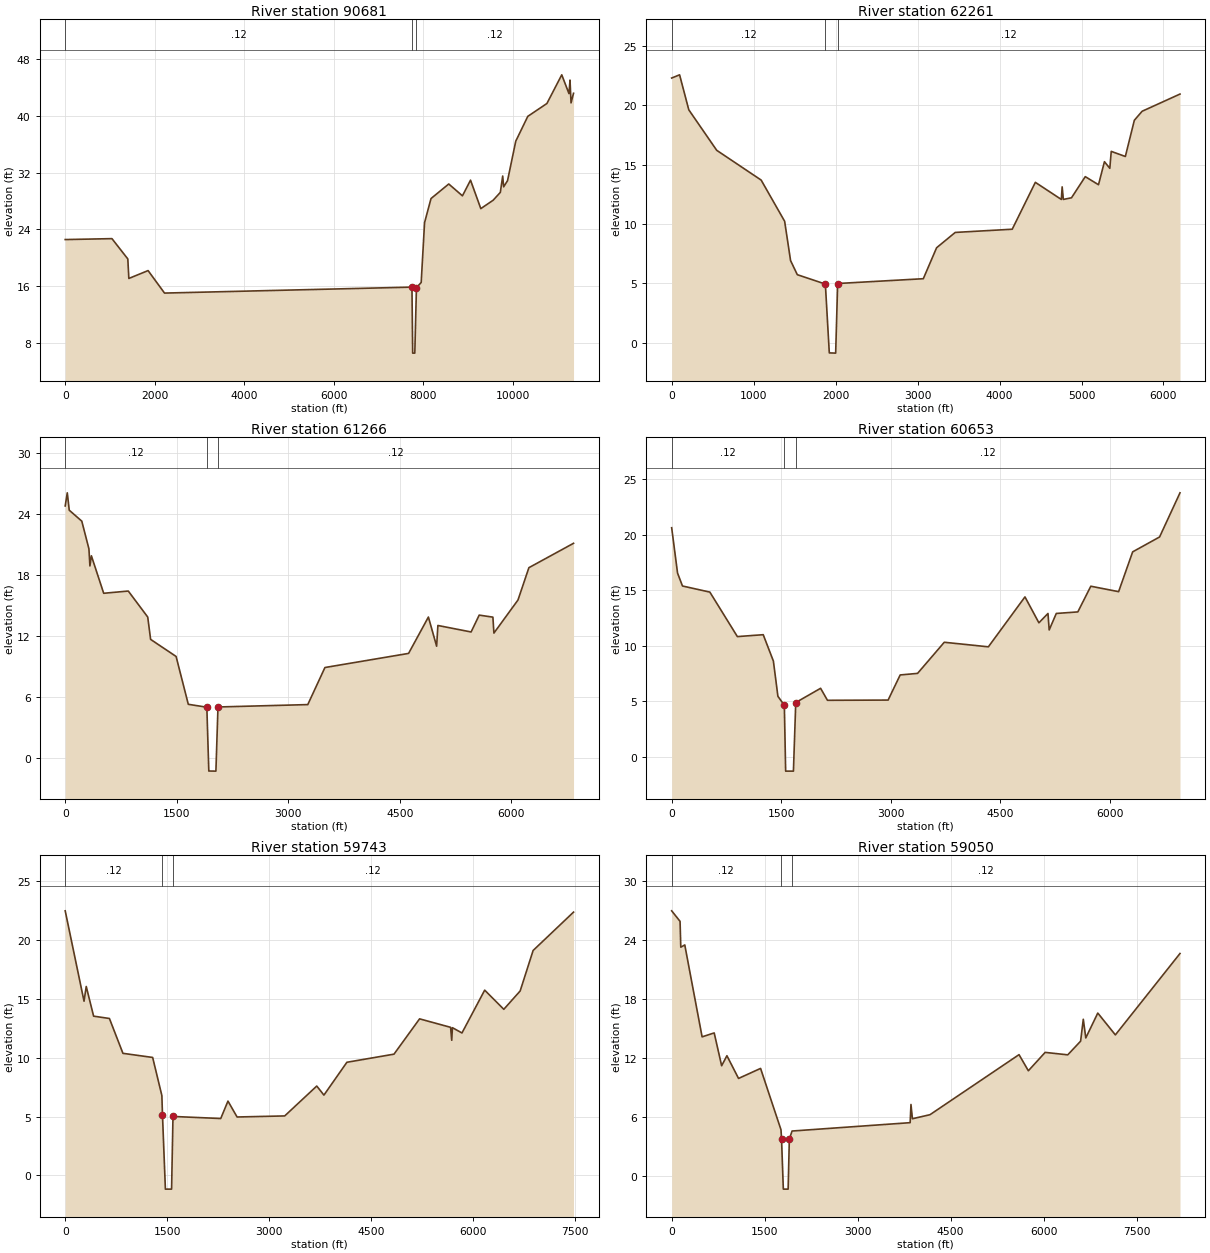
Type RM Length L Ch R = 1 ,90681   ,2944.8,2944.8,2944.8
XS GIS Cut Line= 4
2106397.55682745366319.4387589582101182.35958186366273.012670718
2095719.55653232366350.3894844512095038.64057147366396.815572691
#Sta/Elev= 30
       0   22.58    1045   22.71  1399.4   19.85  1422.4    17.1  1852.3   18.21
  2219.9   15.04    775015.87843 7766.29    6.58  7813.8    6.58    785015.78977
  7956.4   16.54  8031.9   24.97  8176.3   28.36  8572.5   30.41  8878.7   28.74
  9059.2   30.95    9289   26.94  9564.6   28.12  9725.5   29.23    9778   31.53
  9799.6   30.01  9886.4   30.88 10070.1   36.44 10339.2   39.94 10766.1   41.75
 11098.3   45.79 11259.5   43.14 11282.5   45.05 11305.6   41.84 11361.3   43.19
#Mann= 3 ,0,0
       0     .12       0    7750    .041       0    7850     .12       0
Bank Sta=7750,7850
XS Rating Curve= 0 ,0
Exp/Cntr(USF)=0,0
Exp/Cntr=0.3,0.1

Type RM Length L Ch R = 1 ,62261   ,995.7,995.7,995.7
XS GIS Cut Line= 6
2108565.32228052348371.6293052752108376.18519788346366.723367857
2108166.34421596345931.3629740592107645.84183687345368.922193977
2106910.35740571344764.4410710632105062.22230429344046.441724679
#Sta/Elev= 30
       0   22.29    96.6   22.56     209   19.61   549.5    16.2  1091.8   13.69
  1378.2   10.22  1450.5    6.91  1532.7    5.72    1875  4.9276 1923.02    -.87
 2000.65    -.89    2025 4.97617    3070    5.38  3232.1    7.99  3459.3    9.28
  4154.7    9.55  4436.8    13.5  4753.6   12.06  4763.9   13.12  4778.2   12.06
    4878    12.2  5045.8   13.98  5207.2    13.3  5279.7   15.24  5345.1   14.68
  5362.7   16.11  5534.7   15.68  5644.4   18.73  5739.4   19.49  6201.4   20.94
#Mann= 3 ,0,0
       0     .12       0    1875    .041       0    2025     .12       0
Bank Sta=1875,2025
XS Rating Curve= 0 ,0
Exp/Cntr(USF)=0,0
Exp/Cntr=0.3,0.1

Type RM Length L Ch R = 1 ,61266   ,612.6,612.6,612.6
XS GIS Cut Line= 6
2109643.36416889348136.061039782 2109419.2208664346405.377529302
2108901.83713806345764.4344459052108097.35273658345035.840382716
2107248.48796725344541.4190195852105134.72207127343946.508637072
#Sta/Elev= 30
       0   24.82    27.9   26.11    54.4    24.4   223.1   23.32   319.1   20.59
   332.4   18.91   352.2   19.91   517.7   16.22   848.6   16.44    1110   13.88
  1148.9   11.68  1491.6      10  1655.7    5.29    19055.002243 1931.73   -1.28
 2027.04   -1.29    20555.025343  3262.9    5.26  3493.7    8.91  4618.7    10.3
  4885.3   13.88  4996.1   11.01  5013.1   13.05  5459.7   12.41  5568.8   14.07
  5752.9   13.87  5766.6    12.3  6090.5   15.56  6237.1   18.74  6837.5   21.14
#Mann= 3 ,0,0
       0     .12       0    1905    .041       0    2055     .12       0
Bank Sta=1905,2055
XS Rating Curve= 0 ,0
Exp/Cntr(USF)=0,0
Exp/Cntr=0.3,0.1

Type RM Length L Ch R = 1 ,60653   ,910.6,910.6,910.6
XS GIS Cut Line= 5
2110712.77288746347311.8579898082109773.11276474345805.532602232
2108460.91386474344677.8068074582107503.50920049344364.812564901
2105104.22212249343861.947563075
#Sta/Elev= 30
       0   20.62    80.6   16.54   148.1   15.38   523.3   14.83   900.1   10.83
  1254.4      11  1393.6    8.63  1455.5    5.46 1543.58    4.65 1561.55   -1.27
 1668.17   -1.27    17004.898249  2040.4    6.18  2134.4     5.1  2965.2    5.12
  3130.8    7.38  3368.8    7.52  3734.8   10.32  4339.1    9.91  4840.4    14.4
  5031.2   12.07  5155.6   12.91  5172.3   11.43  5269.6   12.91  5564.6   13.05
  5742.4   15.36  6123.4   14.87  6315.7   18.45  6684.6   19.79  6964.3   23.76
#Mann= 3 ,0,0
       0     .12       0 1543.58    .041       0    1700     .12       0
Bank Sta=1543.58,1700
XS Rating Curve= 0 ,0
Exp/Cntr(USF)=0,0
Exp/Cntr=0.3,0.1

Type RM Length L Ch R = 1 ,59743   ,692.5,692.5,692.5
XS GIS Cut Line= 6
 2111543.9979528346799.4654006252110720.29886494345621.270508605
2110432.87640412345334.4647799842109800.23240003344896.283538183
2108623.27742312  344521.24242642105070.32233361343764.748045568
#Sta/Elev= 30
       0   22.49   277.2   14.81   309.7   16.06   418.2   13.54   651.1   13.34
   849.8   10.38  1287.4   10.03  1423.1    6.79 1432.21    5.13  1474.9   -1.16
 1566.09   -1.16  1586.85.015964  2289.7    4.84  2396.2    6.32  2530.4    4.97
  3231.5    5.06  3703.4     7.6  3808.9    6.83  4147.1    9.62  4840.5   10.31
  5217.1   13.31  5673.7   12.59  5690.5   11.49  5700.5   12.56  5841.1   12.11
  6175.8   15.75  6456.9   14.12  6697.9   15.68  6888.7   19.12  7483.6   22.38
#Mann= 3 ,0,0
       0     .12       0 1432.21    .041       0  1586.8     .12       0
Bank Sta=1432.21,1586.8
XS Rating Curve= 0 ,0
Exp/Cntr(USF)=0,0
Exp/Cntr=0.3,0.1

Type RM Length L Ch R = 1 ,59050   ,254.1,254.1,254.1
BEGIN DESCRIPTION:
HEC-2 RS: 218448
END DESCRIPTION:
XS GIS Cut Line= 6
2112282.70593525346571.0636307492111510.76004851345480.860592143
2111131.56207502345054.5707431452110853.32104535344810.025185703
2110729.34134793344740.5849727232105051.66105604343662.589639585
#Sta/Elev= 30
       0   26.96   135.3   25.89     147   23.26   211.4   23.49   490.8   14.14
   685.9   14.54     806    11.2   891.1   12.22  1078.6    9.91  1434.1   10.93
  1763.5    4.68 1772.133.742357  1800.8   -1.35 1878.42   -1.35 1897.79    3.75
    1942    4.56  3846.3    5.41  3859.6    7.26  3882.9    5.81  4166.1    6.22
  5602.5   12.33    5753   10.69  6023.8   12.56  6388.3   12.31  6595.6    13.7
    6639   15.93  6679.2   14.03  6872.8   16.56  7156.3   14.34  8198.7   22.62
#Mann= 3 ,-1,0
       0     .12       0  1763.5    .041       0    1942     .12       0
Bank Sta=1772.13,1897.79
XS Rating Curve= 0 ,0
Exp/Cntr(USF)=0,0
Exp/Cntr=0.3,0.1

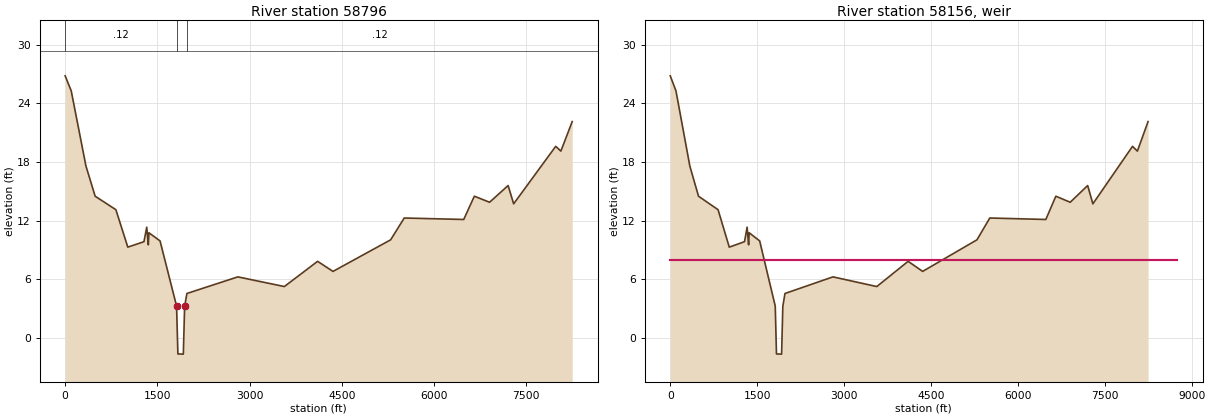
Type RM Length L Ch R = 1 ,58796   ,616.6,616.6,616.6
BEGIN DESCRIPTION:
HEC-2 RS: 218419
END DESCRIPTION:
XS GIS Cut Line= 6
2112465.11983619 346422.549297062111363.13655015344933.468875854
2111165.40341921344740.6376676242110893.85305968344560.725925455
2110725.69108737 344502.288003772105210.34691174343461.561526106
#Sta/Elev= 30
       0   26.81    98.7   25.28   338.2   17.59     488    14.5   825.3   13.12
  1019.1    9.29  1282.2    9.85  1326.9   11.33  1352.7    9.53  1362.2   10.76
  1543.5    9.93 1812.413.262738 1833.62   -1.63 1922.08   -1.65  1943.2    3.23
  1980.2    4.55  2808.6    6.25  3565.2    5.26  4106.1    7.84  4356.5    6.81
  5294.1   10.04    5515   12.27  6482.5   12.12  6655.3    14.5  6902.9   13.88
  7204.5   15.59  7294.5   13.72  7978.7    19.6  8062.5   19.11    8247   22.13
#Mann= 3 ,-1,0
       0     .12       0 1812.41    .041       0  1980.2     .12       0
Bank Sta=1812.41,1943.2
XS Rating Curve= 0 ,0
Exp/Cntr(USF)=0,0
Exp/Cntr=0.3,0.1

Type RM Length L Ch R = 5 ,58156   ,,,
IW Pilot Flow=0
#Inline Weir SE= 2
       0       88751.605       8
IW Dist,WD,Coef,Skew,MaxSub,Min_El,Is_Ogee,SpillHt,DesHd
14.05228,16,2.6,0,0.98,, 0 ,,,2,2,
Inline Weir Flap Gates= 0
IW Outlet Rating Curve= 0 ,False,,

--- AshepooRiver.g12 (geometry) ---

Geom Title=Corrected Effective
Program Version=6.60

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
River Reach=River 1         ,Reach 1
Reach XY= 30
2098396.23576606380646.8009591682097747.70079908376704.682944754
2098349.83399384 375176.529045482097726.69704407373600.953953826
2098114.75192337367841.6387006832099554.59564156365212.903242423
2099428.81121289363681.5771457152100708.15579364362482.324665464
2101289.63273322358523.8663055422100333.06655326351923.692230741
2105558.65619563 346752.098334352109100.83653268346361.782563958
 2111805.7756717  344595.11980812111881.37719572 342976.52674064
2110389.42873442341236.9377136342112009.03935508339315.330548813
2116615.76753564    339445.902442118850.12631383 341189.46406122
2121488.85557328  342010.05266182124117.63341542 340190.58593847
 2128091.1898635 340778.699006762130034.79235487  338498.5211566
2133356.08251692 338118.686337012134731.17271658 332679.67329194
2137633.21854056 330935.617395952135404.68988351 328442.04194944
 2135479.5315566 327368.052712862137781.44848433  324683.1006559
2139929.12472133 324531.725201252141596.00533789 322979.69654025

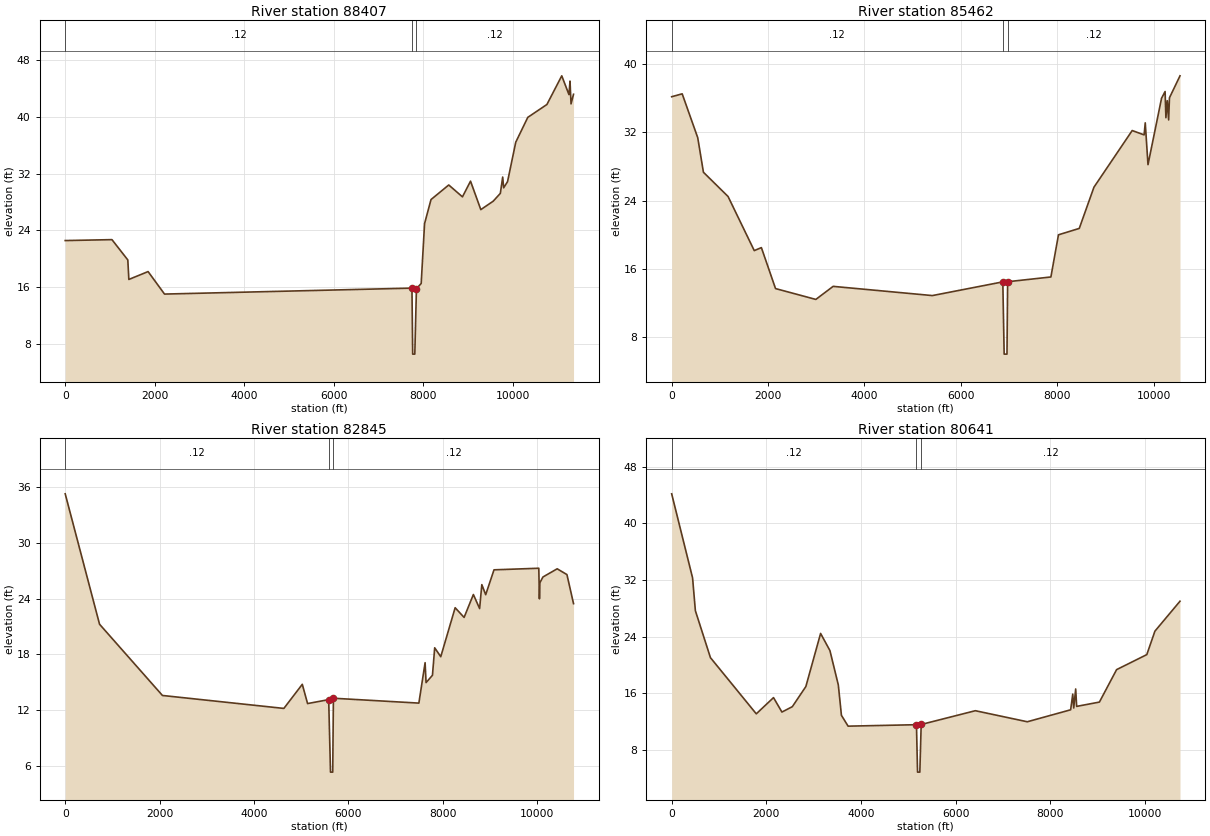
Type RM Length L Ch R = 1 ,88407   ,2944.8,2944.8,2944.8
XS GIS Cut Line= 4
2106397.55682745366319.4387589582101182.35958186366273.012670718
2095719.55653232366350.3894844512095038.64057147366396.815572691
#Sta/Elev= 30
       0   22.58    1045   22.71  1399.4   19.85  1422.4    17.1  1852.3   18.21
  2219.9   15.04    775015.87843 7766.29    6.58  7813.8    6.58    785015.78977
  7956.4   16.54  8031.9   24.97  8176.3   28.36  8572.5   30.41  8878.7   28.74
  9059.2   30.95    9289   26.94  9564.6   28.12  9725.5   29.23    9778   31.53
  9799.6   30.01  9886.4   30.88 10070.1   36.44 10339.2   39.94 10766.1   41.75
 11098.3   45.79 11259.5   43.14 11282.5   45.05 11305.6   41.84 11361.3   43.19
#Mann= 3 ,0,0
       0     .12       0    7750    .041       0    7850     .12       0
Bank Sta=7750,7850
XS Rating Curve= 0 ,0
Exp/Cntr(USF)=0,0
Exp/Cntr=0.3,0.1

Type RM Length L Ch R = 1 ,85462   ,2617.4,2617.4,2617.4
XS GIS Cut Line= 3
2106396.93542404363503.8041623472099505.29078866364086.196666745
  2095946.225484364798.009727677
#Sta/Elev= 30
       0   36.18   218.1   36.52   540.8   31.38     659   27.33  1169.9   24.49
  1713.3   18.15  1861.5    18.5  2154.6    13.7  2991.1   12.43  3350.1   13.96
  5408.5   12.88    687014.48625 6897.76    6.02 6956.29    6.02    697014.50333
  7867.4   15.06  8024.4      20  8456.1   20.75  8760.7   25.58  9554.2   32.22
    9801   31.71  9824.9   33.12  9881.8   28.22   10163      36 10236.6   36.79
 10253.3   33.72 10281.5   35.72 10310.2   33.46 10326.9   36.0510545.76   38.63
#Mann= 3 ,0,0
       0     .12       0    6870    .041       0    6970     .12       0
Bank Sta=6870,6970
XS Rating Curve= 0 ,0
Exp/Cntr(USF)=0,0
Exp/Cntr=0.3,0.1

Type RM Length L Ch R = 1 ,82845   ,2203.7,2203.7,2203.7
XS GIS Cut Line= 4
2106299.87000664362403.7294318162104876.24388478 362339.01915355
2100540.65524092362177.2434578832095687.38437094 363439.09388408
#Sta/Elev= 30
       0   35.25   728.1   21.25  2061.7    13.6  4636.3   12.21  5027.1    14.8
  5139.1   12.735586.82113.15396 5625.24    5.37 5672.39    5.375686.82113.30377
  7498.9   12.78  7631.1   17.12  7651.4   14.98  7787.1   15.77  7834.6   18.72
    7963   17.76  8268.2   23.02  8458.1   21.98  8654.8   24.44    8787   22.93
  8833.9    25.5  8915.9   24.42  9092.2   27.09 10041.7   27.26 10055.2   23.98
 10065.4   25.71 10129.8   26.32 10431.6    27.2 10638.5   26.5810778.33   23.46
#Mann= 3 ,0,0
       0     .12       05586.821    .041       05686.821     .12       0
Bank Sta=5586.821,5686.821
XS Rating Curve= 0 ,0
Exp/Cntr(USF)=0,0
Exp/Cntr=0.3,0.1

Type RM Length L Ch R = 1 ,80641   ,1673.9,1673.9,1673.9
XS GIS Cut Line= 4
2106043.70142807 360642.752451782101182.44207423 360642.75245178
 2100503.1394571360557.8396246392095535.73906933362065.042306397
#Sta/Elev= 30
       0   44.15   441.6   32.28   500.7   27.65     819   21.02  1787.2   13.09
  2151.4   15.38  2328.7   13.34  2548.5    14.1    2834   16.94  3145.8   24.44
  3342.7   22.02  3519.9   17.17  3585.6   12.88  3726.7   11.355170.20611.55534
 5193.38    4.86 5241.73    4.865270.20611.58589  6414.5   13.53  7511.9   11.97
  8427.2   13.66  8471.8   15.87  8492.4   13.91  8533.5    16.6  8554.1   14.14
  9034.8   14.75  9397.8   19.33 10035.7   21.45 10207.1   24.76 10736.9   28.99
#Mann= 3 ,0,0
       0     .12       05170.206    .041       05270.206     .12       0
Bank Sta=5170.206,5270.206
XS Rating Curve= 0 ,0
Exp/Cntr(USF)=0,0
Exp/Cntr=0.3,0.1