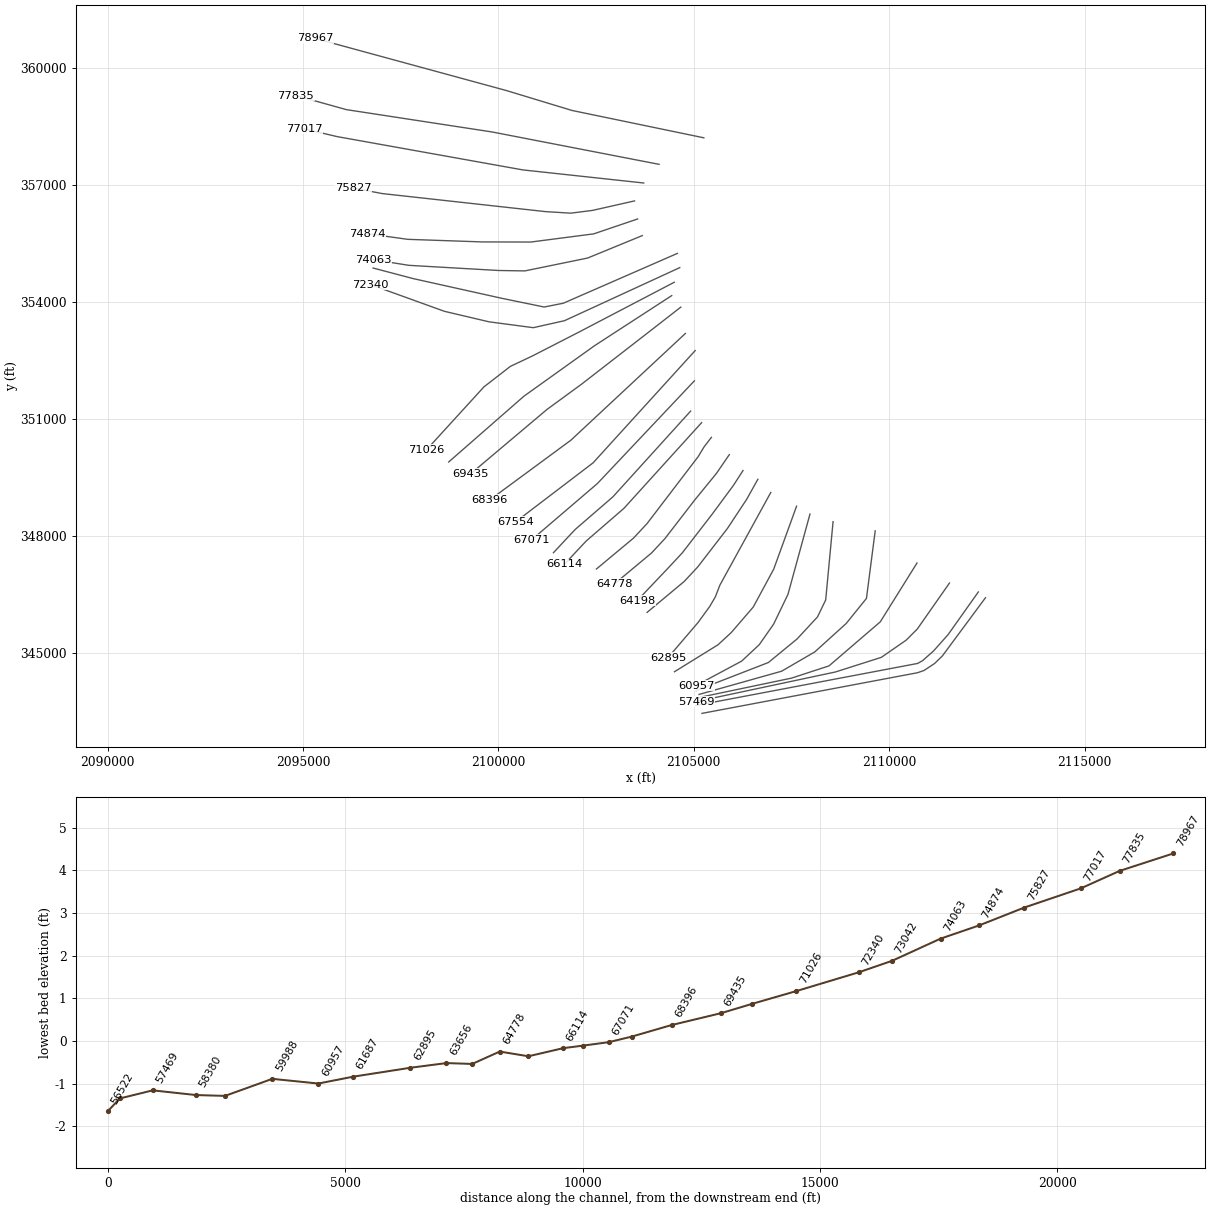
HEC-RAS study AshepooRiver.prj: S-15-41 over Ashepoo River

--- AshepooRiver.g12 (geometry) --- (continued)

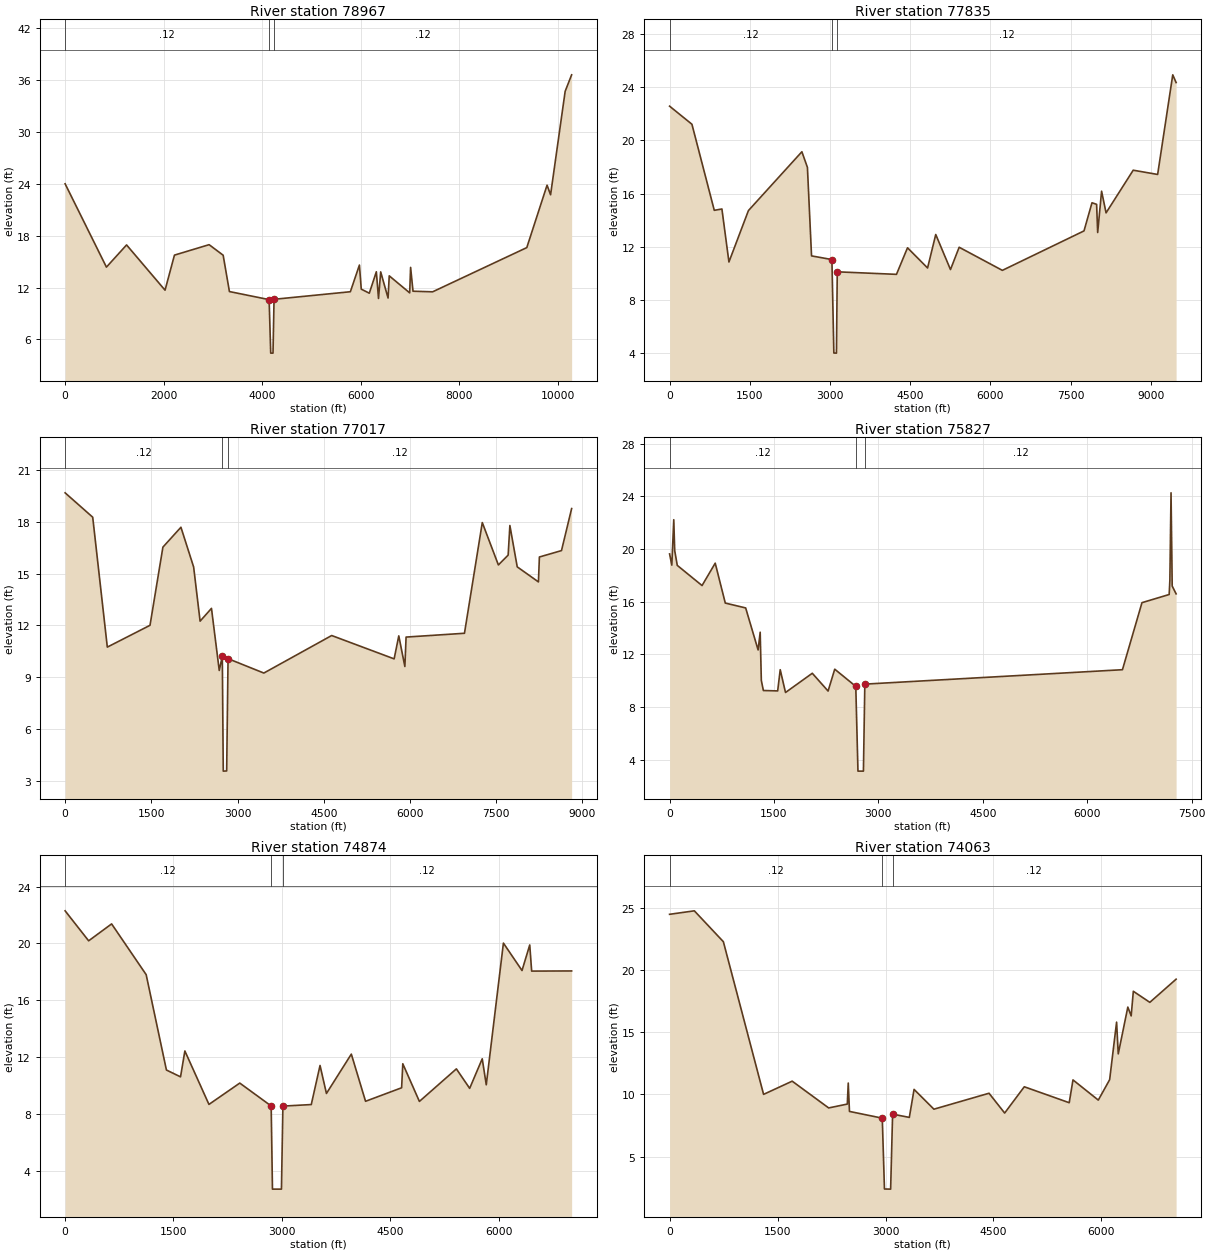
Type RM Length L Ch R = 1 ,78967   ,1132.2,1132.2,1132.2
XS GIS Cut Line= 4
2105258.25777701358201.5086714672101882.97289815358902.039495383
 2100205.9445621359411.5164582312095302.22879469360748.893485707
#Sta/Elev= 30
       0   24.01   838.7   14.36  1247.6   16.93  2028.6   11.69  2219.6   15.75
  2923.5   16.96  3208.4   15.74  3335.7   11.534141.57110.59565 4173.95     4.4
 4220.34     4.44241.57110.63325  5790.9   11.51  5974.6    14.6    6012   11.81
  6175.2   11.34  6318.1   13.82  6362.3   10.73  6406.4   13.81  6556.2   10.78
    6580   13.35    6995   11.38  7013.6   14.33  7062.7   11.57  7460.7    11.5
  9372.4   16.62    9784   23.85  9855.4   22.74 10151.4   34.7210282.74   36.63
#Mann= 3 ,0,0
       0     .12       04141.571    .041       04241.571     .12       0
Bank Sta=4141.571,4241.571
XS Rating Curve= 0 ,0
Exp/Cntr(USF)=0,0
Exp/Cntr=0.3,0.1

Type RM Length L Ch R = 1 ,77835   ,817.9,817.9,817.9
XS GIS Cut Line= 4
 2104111.9346106357522.2060543372099845.06504675358350.106118965
2096108.90065254358923.2677021682094813.98003863359284.147217519
#Sta/Elev= 30
       0   22.58   417.7   21.22   835.5   14.74   978.3   14.84  1109.7   10.85
    1474   14.72  2473.6   19.15  2577.2   17.97  2654.1   11.31    303511.03299
  3071.3       4 3119.82    3.99    313510.11057    4242    9.92  4448.6   11.92
  4823.7    10.4  4976.5   12.92    5252   10.28  5414.3   11.96    6222   10.22
  7748.4   13.19  7897.9   15.31  7984.2   15.19  8004.1   13.07  8077.2   16.18
    8161   14.55  8668.7   17.76  9125.3   17.44  9407.9   24.949470.586   24.36
#Mann= 3 ,0,0
       0     .12       0    3035    .041       0    3135     .12       0
Bank Sta=3035,3135
XS Rating Curve= 0 ,0
Exp/Cntr(USF)=0,0
Exp/Cntr=0.3,0.1

Type RM Length L Ch R = 1 ,77017   ,1190.2,1190.2,1190.2
XS GIS Cut Line= 4
2103719.85250626357044.0968831052100627.32658961357379.108622936
2095876.54498006358231.4916030132095024.16199999358432.052304208
#Sta/Elev= 30
       0   19.67   480.2   18.26   734.3   10.75  1477.1   12.01  1701.5   16.53
  2015.1   17.68  2236.3   15.38  2348.5   12.25  2546.6   12.99  2681.9     9.4
    273510.22525  2751.7    3.58 2810.91    3.59    283510.08146  3457.8    9.25
  4638.1   11.42  5724.7   10.07  5805.5    11.4  5911.4    9.63  5932.7   11.33
  6948.3   11.55  7258.4   17.95  7538.5    15.5  7708.5   16.07  7738.5   17.78
  7866.4   15.39  8235.3   14.52  8252.1   15.96  8636.5   16.338812.922   18.76
#Mann= 3 ,0,0
       0     .12       0    2735    .041       0    2835     .12       0
Bank Sta=2735,2835
XS Rating Curve= 0 ,0
Exp/Cntr(USF)=0,0
Exp/Cntr=0.3,0.1

Type RM Length L Ch R = 1 ,75827   ,952.8,952.8,952.8
XS GIS Cut Line= 6
2103484.77253227356585.643760793 2102409.3881305356342.559731688
2101850.75576887356271.4910918842101200.12087369356311.763392387
2097028.31291086356773.2007179292096279.54032397356915.172039683
#Sta/Elev= 30
       0   19.62    31.9   18.77      60   22.22    73.5   19.87   110.5   18.75
   466.4   17.22   655.5   18.92   800.2   15.89  1092.9   15.52  1271.7   12.33
  1301.5   13.68    1318   10.01  1347.8    9.25  1552.9    9.22  1589.3   10.83
  1665.4     9.1  2050.1   10.56    2277    9.21  2372.6   10.87    26759.566566
 2706.35    3.13 2784.84    3.13    28059.734908  6506.2   10.83  6786.7   15.92
  7177.5   16.54  7187.5   17.61  7204.2   24.26  7220.9   17.18  7277.1   16.59
#Mann= 3 ,0,0
       0     .12       0    2675    .041       0    2805     .12       0
Bank Sta=2675,2805
XS Rating Curve= 0 ,0
Exp/Cntr(USF)=0,0
Exp/Cntr=0.3,0.1

Type RM Length L Ch R = 1 ,74874   ,811.4,811.4,811.4
XS GIS Cut Line= 6
2103563.33853893356122.9023916632102439.46191877355741.479447767
2100828.15808317355532.0491173452099585.11723442355535.141277814
2097678.49577922355601.6040459542096639.78637301355746.062602483
#Sta/Elev= 30
       0   22.29   325.8   20.18   643.8   21.37  1122.1    17.8  1402.5   11.09
  1597.9   10.61  1657.9   12.43  1991.3    8.67  2417.9   10.17 2852.64    8.56
 2870.41    2.71 2994.83    2.71    30158.550438  3407.7    8.66  3529.1   11.41
  3617.7    9.44  3962.3   12.21  4159.2    8.89  4658.4    9.84  4674.8   11.53
  4904.7    8.88  5416.6   11.17  5600.5     9.8  5774.5   11.88  5830.3   10.05
  6067.7   20.02  6325.2   18.09  6432.2   19.89  6458.7   18.05  7012.1   18.06
#Mann= 3 ,0,0
       0     .12       0 2852.64    .041       0    3015     .12       0
Bank Sta=2852.64,3015
XS Rating Curve= 0 ,0
Exp/Cntr(USF)=0,0
Exp/Cntr=0.3,0.1

Type RM Length L Ch R = 1 ,74063   ,1021,1021,1021
XS GIS Cut Line= 6
2103682.61513281355697.0549044052102284.70829131355122.464937907
2100677.49266574354792.8194410942099999.66209378354803.752192255
2097708.15364479354935.6286455442096807.74356719 355079.52451163
#Sta/Elev= 30
       0   24.47   343.8   24.75   747.2   22.27  1305.9   10.01  1703.3   11.07
  2210.3    8.92  2468.9    9.23  2482.3   10.92  2499.1    8.64    29558.099456
 2985.25    2.41 3071.13     2.4 3098.528.422089  3330.9    8.16  3396.7   10.41
  3672.3    8.82  4438.2    10.1  4655.3    8.51  4928.1   10.62  5552.2    9.34
  5604.7   11.17  5956.4    9.55  6114.1   11.19  6210.4   15.81  6233.6   13.26
  6366.6   17.02  6413.3   16.31    6443   18.29  6672.3    17.4  7037.4   19.26
#Mann= 3 ,0,0
       0     .12       0    2955    .041       0 3098.52     .12       0
Bank Sta=2955,3098.52
XS Rating Curve= 0 ,0
Exp/Cntr(USF)=0,0
Exp/Cntr=0.3,0.1

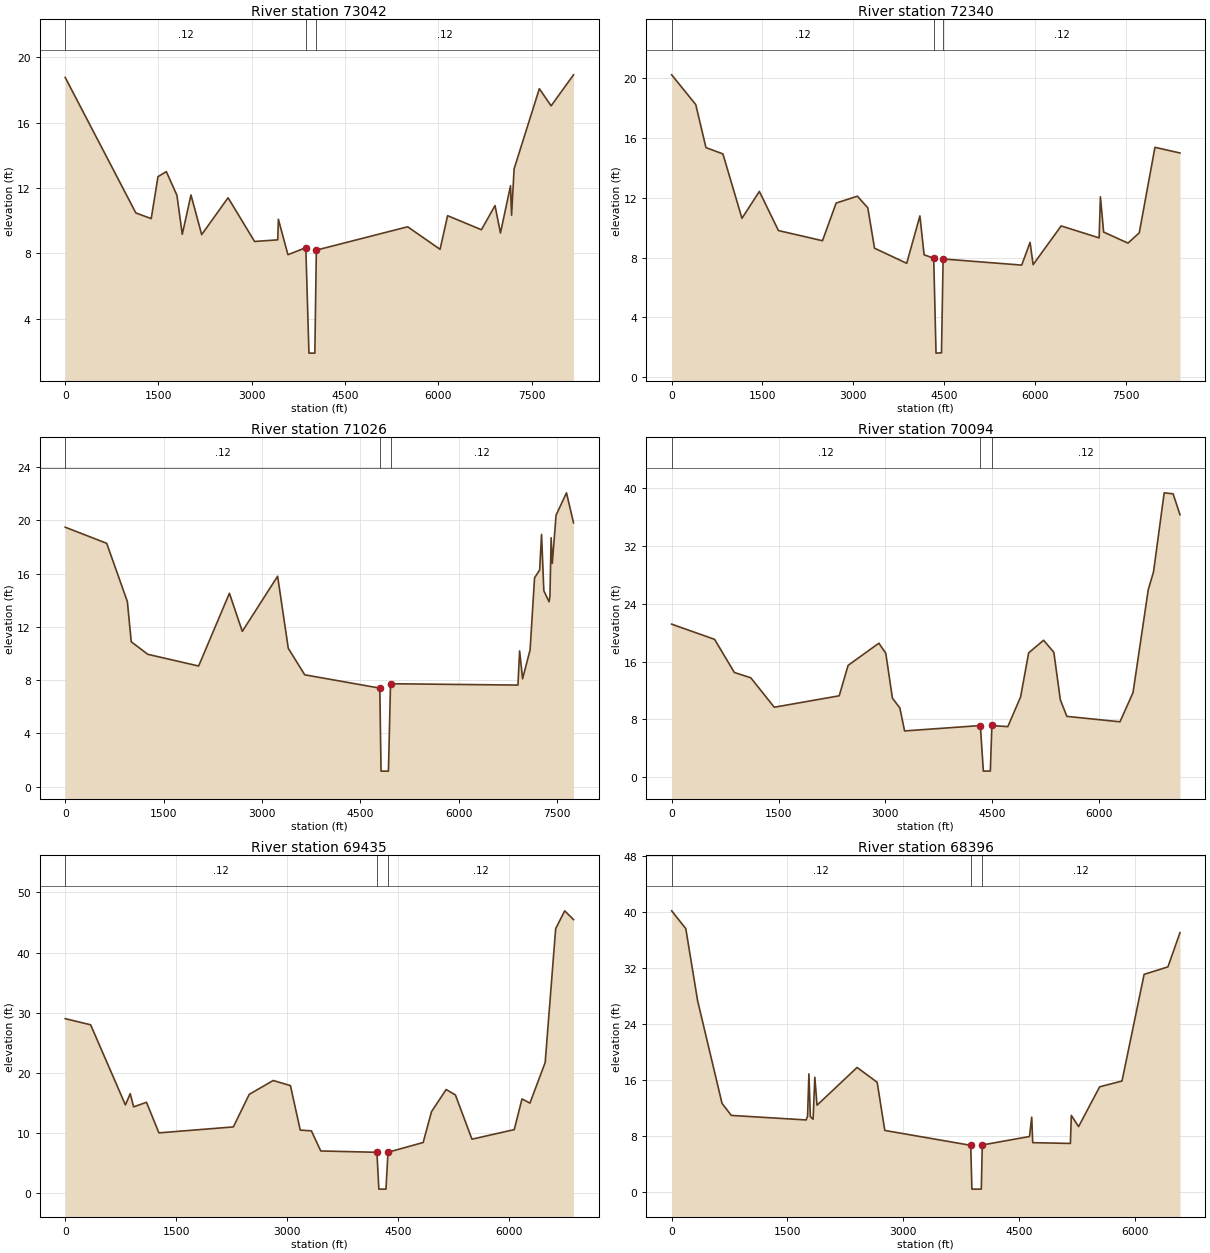
Type RM Length L Ch R = 1 ,73042   ,702.4,702.4,702.4
XS GIS Cut Line= 6
2104580.48483008 355241.062238682101661.80877761353965.224877458
2101171.16157919353868.206247267 2100082.3226075354092.234792296
2097823.82905937354594.7347783322096794.35129549 354866.19170869
#Sta/Elev= 30
       0   18.77  1135.9   10.47  1383.4   10.12    1492   12.69  1626.4      13
  1796.9   11.55  1882.8    9.16  2022.9   11.57    2195    9.14  2619.6    11.4
  3045.7    8.72    3418    8.82  3428.5   10.08  3582.4    7.91    3870 8.34008
 3920.28    1.88 4015.14    1.88 4039.05    8.19  5507.9    9.62    6029    8.24
  6150.1    10.3  6694.3    9.44  6912.9   10.92  7000.3    9.24  7162.1   12.13
  7179.1   10.33  7219.8   13.17    7626   18.08  7815.1   17.03  8175.6   18.93
#Mann= 3 ,0,0
       0     .12       0    3870    .041       0 4039.05     .12       0
Bank Sta=3870,4039.05
XS Rating Curve= 0 ,0
Exp/Cntr(USF)=0,0
Exp/Cntr=0.3,0.1

Type RM Length L Ch R = 1 ,72340   ,1313.4,1313.4,1313.4
XS GIS Cut Line= 6
2104641.45660154354877.0331971342101692.11568816353517.983834757
2100893.78222901353339.0597686792099760.68197156  353489.0289204
2098619.17759005 353758.006675212096722.45335365354443.507094647
#Sta/Elev= 30
       0   20.23     398   18.24   566.7   15.36   846.7   14.94  1161.5   10.63
    1449   12.43  1764.3    9.81  2491.9    9.13  2717.6   11.65  3068.8   12.11
  3240.8   11.33  3352.3    8.63  3883.7    7.62  4101.7   10.79  4171.3    8.19
    43307.960487 4368.31    1.61 4458.54    1.63 4485.35    7.91    5784     7.5
  5922.2    9.02  5972.8    7.53  6435.8   10.12  7063.4    9.32  7084.3   12.07
  7137.8    9.71  7540.5    8.97  7726.5    9.66  7985.9   15.38  8399.6      15
#Mann= 3 ,0,0
       0     .12       0    4330    .041       0 4485.35     .12       0
Bank Sta=4330,4485.35
XS Rating Curve= 0 ,0
Exp/Cntr(USF)=0,0
Exp/Cntr=0.3,0.1

Type RM Length L Ch R = 1 ,71026   ,932,932,932
XS GIS Cut Line= 6
2104500.83237574354502.2540987692102059.37782849353224.823799985
2100860.60817398352609.7235453542100308.18738998352348.740765757
2099630.38953622351822.9891955322098164.55244227350216.185473509
#Sta/Elev= 30
       0   19.48   632.4   18.27   947.2    13.9  1006.5   10.88  1258.3    9.94
  2033.5    9.06  2502.8   14.52  2699.1   11.66  3237.4    15.8  3399.9   10.39
  3650.8     8.4  4794.8     7.4 4813.52    1.17  4926.2    1.17  4958.17.728683
  6900.1    7.63  6925.6   10.19  6971.1     8.1  7085.2   10.27  7153.2   15.68
  7231.3   16.27  7259.9   18.94  7294.6   14.71  7374.6   13.88  7387.9   14.32
  7405.7   18.69  7423.5   16.76  7481.2   20.38  7639.7   22.06  7747.3   19.81
#Mann= 3 ,0,0
       0     .12       0  4794.8    .041       0  4958.1     .12       0
Bank Sta=4794.8,4958.1
XS Rating Curve= 0 ,0
Exp/Cntr(USF)=0,0
Exp/Cntr=0.3,0.1

Type RM Length L Ch R = 1 ,70094   ,659,659,659
XS GIS Cut Line= 4
2104436.01786635354160.1425241452102459.03756485352876.263836931
2100652.50396726351583.2095389232098728.33976301 349899.56586021
#Sta/Elev= 30
       0   21.16   602.7   19.06   879.8   14.49  1111.3   13.75  1440.2    9.69
  2351.7   11.27  2476.7   15.47  2908.5   18.53  3005.4   17.15  3099.1   10.94
  3203.1     9.6  3269.6    6.42  4333.2    7.16 4375.27     .87 4473.31     .88
    44957.172149  4718.3    7.01  4897.7    11.1  5011.1   17.19  5220.8   18.94
  5364.8   17.27  5455.9   10.72  5547.5    8.43  6293.2    7.68  6476.3   11.71
    6690   25.91  6764.2   28.39  6913.8   39.29  7038.9   39.15  7135.7   36.27
#Mann= 3 ,0,0
       0     .12       0  4333.2    .041       0    4495     .12       0
Bank Sta=4333.2,4495
XS Rating Curve= 0 ,0
Exp/Cntr(USF)=0,0
Exp/Cntr=0.3,0.1

Type RM Length L Ch R = 1 ,69435   ,1039,1039,1039
XS GIS Cut Line= 5
 2104668.4043109353865.4570101392103846.66691624353225.991559639
2102131.87292103351894.7699054612101242.87252992351244.294252948
 2099285.9100722349593.448827716
#Sta/Elev= 30
       0   29.01   343.8   27.99   814.2   14.66   879.3   16.53   925.7   14.34
  1099.2    15.1  1267.3   10.01  2274.1      11  2488.7   16.42  2812.8   18.72
  3045.5   17.87  3178.6   10.47  3329.6   10.34  3455.6       7    42156.777931
 4241.53     .65 4337.39     .65    43656.781381  4840.6    8.41  4953.4   13.54
    5151   17.22  5276.8   16.32  5500.4    8.96  6072.3   10.55  6177.1   15.66
  6284.4   14.96  6490.5   21.72  6632.2   43.97  6754.4   46.95  6873.9   45.49
#Mann= 3 ,0,0
       0     .12       0    4215    .041       0    4365     .12       0
Bank Sta=4215,4365
XS Rating Curve= 0 ,0
Exp/Cntr(USF)=0,0
Exp/Cntr=0.3,0.1

Type RM Length L Ch R = 1 ,68396   ,842,842,842
XS GIS Cut Line= 3
2104785.08390592353190.3239595122101855.10659491350457.136169394
2099777.88387442348926.551006928
#Sta/Elev= 30
       0   40.19   183.1   37.64   336.3   27.32   652.1   12.66   772.2   10.92
  1742.9   10.27  1760.9   10.82  1778.3   16.86    1797   10.74  1832.7   10.38
  1855.1   16.38  1883.6   12.38  2402.9   17.78    2663   15.66  2761.7    8.77
    38756.639429 3890.62    .372 4012.31    .372    40256.689871  4636.9     7.9
  4665.5   10.67  4678.7    7.02  5166.9    6.91  5179.1   10.92  5272.9    9.32
    5546   15.01  5835.4   15.84  6122.2    31.1  6430.6   32.17  6587.1   37.07
#Mann= 3 ,0,0
       0     .12       0    3875    .041       0    4025     .12       0
Bank Sta=3875,4025
XS Rating Curve= 0 ,0
Exp/Cntr(USF)=0,0
Exp/Cntr=0.3,0.1

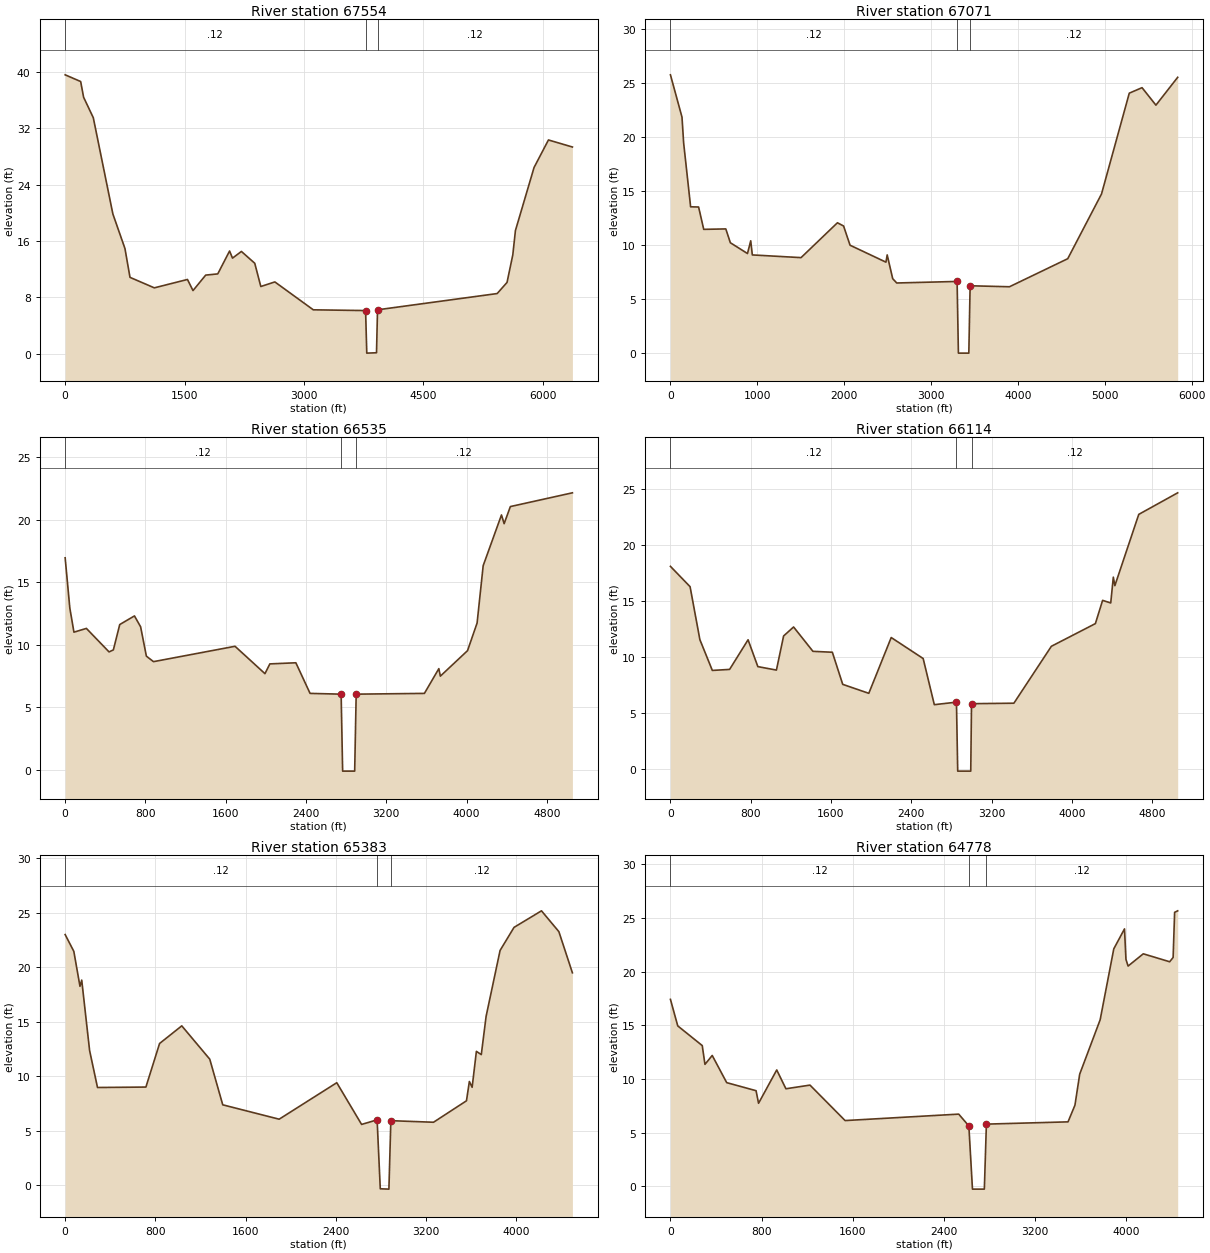
Type RM Length L Ch R = 1 ,67554   ,483.1,483.1,483.1
XS GIS Cut Line= 3
2105036.53718261352753.0139130932102423.60965525349877.700357889
2100444.78169521348368.980697743
#Sta/Elev= 30
       0   39.62     195   38.67   231.7   36.44   353.6   33.53   599.9   19.85
   751.3   14.96   814.7   10.86  1120.3    9.37    1537   10.56  1606.4    8.98
  1766.1   11.18  1917.6   11.35  2065.9    14.6    2103   13.59  2214.6   14.54
  2382.4   12.86  2458.5    9.56  2635.1   10.21    3118    6.25    37756.143803
 3789.86      .1 3912.11     .15    39256.251347  5428.5    8.56  5552.2   10.14
  5624.8   14.06  5657.6    17.5  5891.7   26.46  6072.6   30.37  6373.6   29.37
#Mann= 3 ,0,0
       0     .12       0    3775    .041       0    3925     .12       0
Bank Sta=3775,3925
XS Rating Curve= 0 ,0
Exp/Cntr(USF)=0,0
Exp/Cntr=0.3,0.1

Type RM Length L Ch R = 1 ,67071   ,535.9,535.9,535.9
XS GIS Cut Line= 3
2105016.33473616351978.5532578462102532.84558371349346.594645189
2100845.69262688347902.391714141
#Sta/Elev= 30
       0   25.76     133   21.84   152.1   19.44   232.3   13.53   324.3   13.51
   383.2   11.44   637.4   11.48   689.7    10.2     887     9.2   924.2   10.38
   942.7    9.07  1503.8    8.82  1922.4   12.05  1993.2   11.75  2067.8    9.97
  2480.9     8.4  2495.3    9.07  2558.6    6.87  2605.2    6.47    33006.612388
    3315    -.03    3435    -.03    34506.212595  3902.8    6.12  4573.7    8.72
  4962.6   14.72  5282.2   24.06  5429.1   24.57  5588.9   22.95  5839.5   25.53
#Mann= 3 ,0,0
       0     .12       0    3300    .041       0    3450     .12       0
Bank Sta=3300,3450
XS Rating Curve= 0 ,0
Exp/Cntr(USF)=0,0
Exp/Cntr=0.3,0.1

Type RM Length L Ch R = 1 ,66535   ,421.1,421.1,421.1
XS GIS Cut Line= 5
2104919.42897314351202.4621204592102931.07946149349007.530841367
2101969.18310683348174.7480913592101762.60133939347955.733161985
2101408.81412269347575.326226796
#Sta/Elev= 30
       0   16.96    46.6   12.94    87.6   11.01   211.6   11.31   437.4    9.43
   480.4    9.59     544   11.62   690.6   12.31   751.9   11.44   809.4    9.09
   880.3    8.65  1692.7    9.88  1990.9    7.69  2039.8    8.47  2298.9    8.56
  2440.6    6.11    27506.049471    2765    -.11    2885    -.11    29006.049471
  3579.8    6.11  3723.6    8.09  3738.7    7.49  4009.5    9.53  4104.7   11.74
  4165.4   16.33  4347.7   20.39  4374.2   19.69  4436.3   21.06  5054.5   22.16
#Mann= 3 ,0,0
       0     .12       0    2750    .041       0    2900     .12       0
Bank Sta=2750,2900
XS Rating Curve= 0 ,0
Exp/Cntr(USF)=0,0
Exp/Cntr=0.3,0.1

Type RM Length L Ch R = 1 ,66114   ,730.7,730.7,730.7
XS GIS Cut Line= 5
2105200.84078447350906.7282358382103212.49127282348711.796956746
2102250.59491816347879.0142067382102044.01315072347659.999277365
2101690.22593402347279.592342175
#Sta/Elev= 30
       0   18.07   195.7   16.26   293.4   11.54   417.5     8.8   589.5    8.89
   773.5   11.53   870.9    9.14    1056    8.83  1127.7   11.87  1227.1   12.67
    1420    10.5  1613.3   10.42  1716.7    7.56  1976.6    6.76  2199.9   11.73
  2518.2    9.86  2629.4    5.75    28505.973382 2862.49    -.17  2992.5    -.17
    30005.837326  3422.2    5.88  3795.8   10.95  4234.3   12.97  4306.3   15.04
  4387.3   14.81  4413.1   17.11  4428.4   16.35  4666.6    22.7  5054.5   24.62
#Mann= 3 ,0,0
       0     .12       0    2850    .041       0    3000     .12       0
Bank Sta=2850,3000
XS Rating Curve= 0 ,0
Exp/Cntr(USF)=0,0
Exp/Cntr=0.3,0.1

Type RM Length L Ch R = 1 ,65383   ,605.7,605.7,605.7
XS GIS Cut Line= 6
2105451.07381229350530.1259079532105264.97539394350287.841441331
2105110.69420985 350033.553074562103802.92056539348320.054379324
2103460.76951306347952.0806060652102508.91532765347158.908634768
#Sta/Elev= 30
       0   23.01    76.9   21.47   131.5   18.26     147   18.83     217   12.36
     287    8.97   716.3    9.01   837.7   13.01  1034.6   14.63  1282.9   11.57
  1398.1    7.38  1898.5    6.06  2409.6    9.41  2629.9    5.58  2767.5       6
 2795.61    -.33 2872.13    -.362889.3975.924609    3268    5.78  3560.2    7.75
  3585.9    9.52  3610.5    8.99  3648.2   12.29  3691.7   11.99  3734.4    15.5
  3858.3   21.55  3982.1   23.67  4225.6   25.19  4379.9   23.28    4500    19.5
#Mann= 3 ,0,0
       0     .12       0  2767.5    .041       02889.397     .12       0
Bank Sta=2767.5,2889.397
XS Rating Curve= 0 ,0
Exp/Cntr(USF)=0,0
Exp/Cntr=0.3,0.1

Type RM Length L Ch R = 1 ,64778   ,579.5,579.5,579.5
XS GIS Cut Line= 6
2105909.72849235350087.8721371012105579.00780553 349605.21654921
2105023.86638157348925.1271643062104262.09611412347937.408088715
2103919.94506179347569.4343154562102968.09087638346776.262344159
#Sta/Elev= 30
       0   17.41    64.2   14.94   279.1   13.11     303   11.36   366.7   12.19
   493.7    9.66   751.5    8.91   773.3    7.74   932.9   10.84  1013.4    9.09
  1224.8    9.43  1532.9    6.13  2529.9    6.73  2618.9    5.63  2650.7    -.25
 2754.93    -.25 2772.91     5.8  3489.3    6.01    3550    7.56  3591.8   10.45
  3771.3   15.51  3890.9   22.11  3984.9   23.97  3997.7   21.13  4016.5   20.51
  4149.8   21.65  4381.4   20.91  4411.7   21.31  4424.9   25.51  4451.8   25.65
#Mann= 3 ,0,0
       0     .12       0  2618.9    .041       0 2772.91     .12       0
Bank Sta=2618.9,2772.91
XS Rating Curve= 0 ,0
Exp/Cntr(USF)=0,0
Exp/Cntr=0.3,0.1

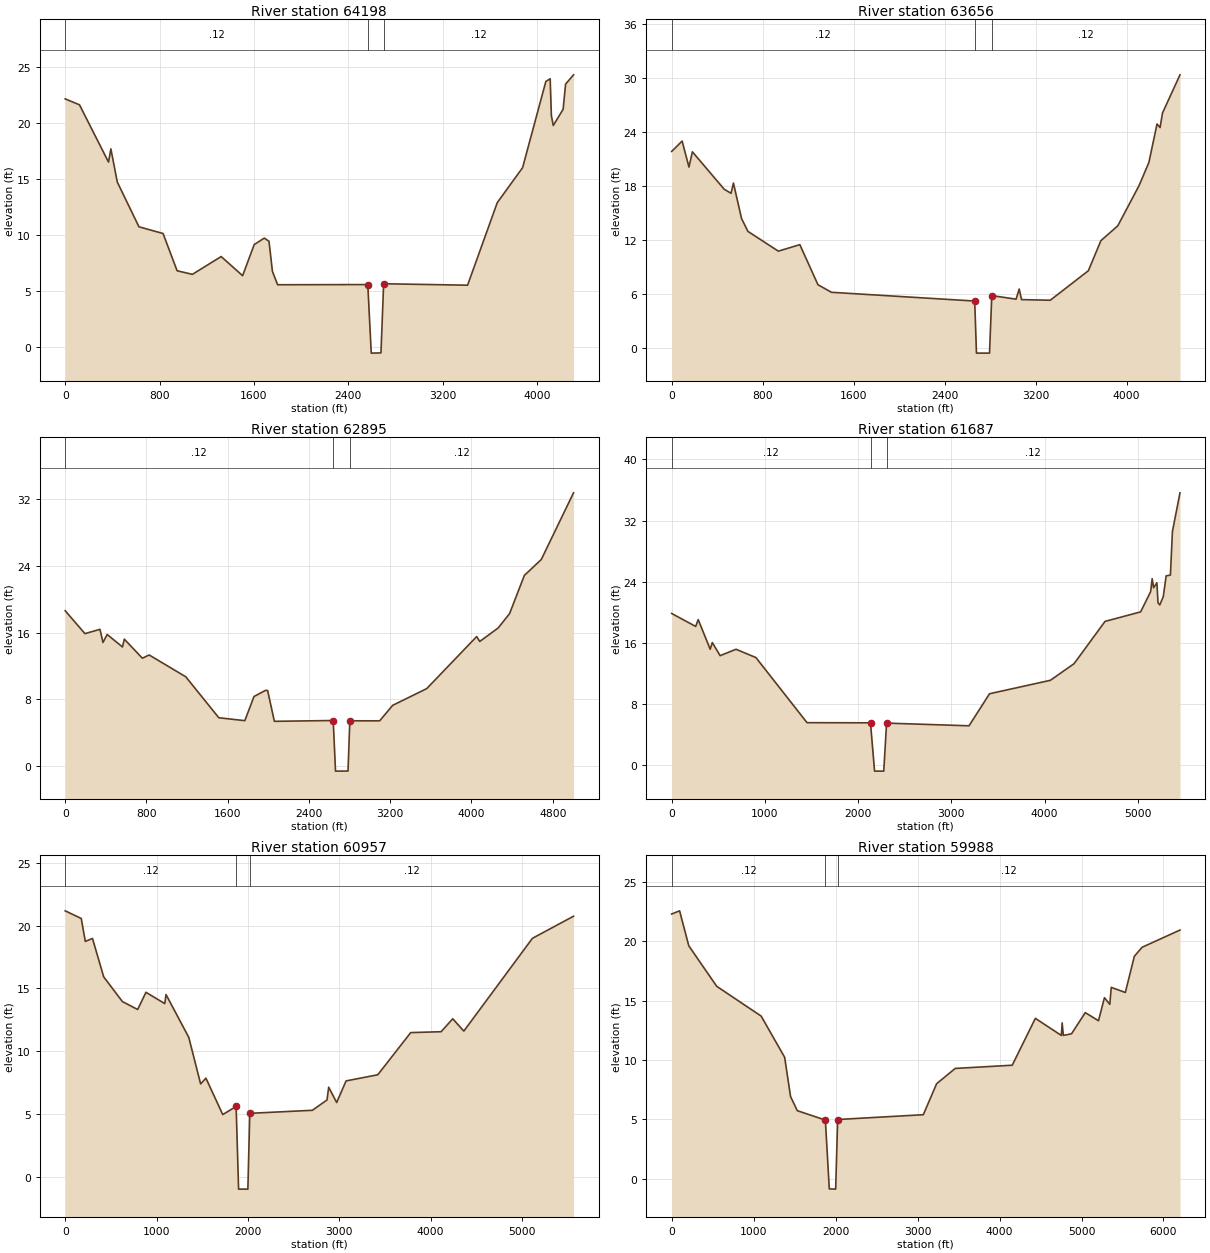
Type RM Length L Ch R = 1 ,64198   ,541.8,541.8,541.8
XS GIS Cut Line= 6
2106260.49878914349680.3857755222106014.05120195 349298.24870406
2105472.10917914348564.3463760172104710.33891169347576.627300427
2104368.18785936347208.6535271672103548.32768542346344.407857385
#Sta/Elev= 30
       0   22.18   121.1   21.65   367.1   16.53     387   17.71   441.4   14.75
     625   10.75   829.4   10.15   948.4    6.82    1078     6.5  1321.9    8.09
  1503.5    6.38  1601.8    9.16  1687.8    9.74  1727.3    9.45  1756.3    6.76
  1800.6    5.572564.3975.587436 2593.82    -.54 2676.09    -.52 2698.72    5.66
  3410.2    5.53  3661.9   12.91  3876.3   16.03  4073.6   23.74  4110.2   23.98
  4120.4   20.68  4136.3    19.8  4219.9   21.25  4240.8    23.5  4308.1   24.33
#Mann= 3 ,0,0
       0     .12       02564.397    .041       0 2698.72     .12       0
Bank Sta=2564.397,2698.72
XS Rating Curve= 0 ,0
Exp/Cntr(USF)=0,0
Exp/Cntr=0.3,0.1

Type RM Length L Ch R = 1 ,63656   ,761.5,761.5,761.5
XS GIS Cut Line= 6
2106639.91538697349455.4434211342106352.85425779348941.312338199
2105861.67916247348197.2566246582105099.90889502347209.537549068
2104757.75784269346841.5637758082103805.90365728346048.391804512
#Sta/Elev= 30
       0   21.83    91.9   22.98   152.1    20.1   182.1   21.79   461.3   17.65
   521.9   17.19     543   18.33   614.5   14.39   670.6   12.97     938   10.78
  1126.8    11.5  1286.1    7.06  1405.3    6.222664.3975.251529 2679.74    -.52
 2794.45    -.522814.3975.853982  3027.9    5.46  3055.4    6.58  3076.1    5.41
  3328.5    5.34  3663.6    8.61  3773.6   11.94  3922.3   13.59  4110.3   18.07
  4195.7   20.61  4267.2   24.87    4294   24.48  4315.4   26.09  4469.2   30.32
#Mann= 3 ,0,0
       0     .12       02664.397    .041       02814.397     .12       0
Bank Sta=2664.397,2814.397
XS Rating Curve= 0 ,0
Exp/Cntr(USF)=0,0
Exp/Cntr=0.3,0.1

Type RM Length L Ch R = 1 ,62895   ,1208.3,1208.3,1208.3
XS GIS Cut Line= 6
2106971.16762549349118.6353251632105668.00875549346744.728572319
2105552.85570614346446.1605709182105408.38327427346199.065693092
2105106.05692631345783.8167286512104341.20857382344889.364607303
#Sta/Elev= 30
       0   18.63   194.5   15.88   342.3    16.4   372.1   14.82   413.1   15.78
     564   14.28   582.2   15.22   759.7   12.93   826.8   13.32  1187.1    10.7
  1512.5    5.78  1768.7    5.43  1858.7    8.33  1972.9    9.07  1993.4    9.05
  2059.5    5.352639.0085.448291 2661.63    -.63 2784.71    -.62  2802.45.411972
  3096.3    5.41  3224.5    7.27    3560    9.28  4051.4   15.53  4081.6   14.94
  4263.1   16.56  4375.4   18.28  4520.9   22.87  4687.6   24.78  5005.2   32.79
#Mann= 3 ,0,0
       0     .12       02639.008    .041       0  2802.4     .12       0
Bank Sta=2639.008,2802.4
XS Rating Curve= 0 ,0
Exp/Cntr(USF)=0,0
Exp/Cntr=0.3,0.1

Type RM Length L Ch R = 1 ,61687   ,729.3,729.3,729.3
XS GIS Cut Line= 6
2107631.10497338348767.652928333 2107046.5754343347156.298112087
2106523.02960873346185.5518378322105958.50709774345530.207926267
2105621.25247013345218.5302854072104507.20787529  344528.6153287
#Sta/Elev= 30
       0   19.82   257.9   18.12   284.4   19.02   413.5   15.13     436   16.01
   519.8   14.29   690.2   15.13   903.8   14.04  1451.9    5.51 2132.67    5.49
 2176.17    -.84 2274.74    -.84    23055.451851  3189.2     5.1  3409.3     9.3
  4061.6   11.06  4315.9   13.24  4647.9   18.78  5030.1   20.03  5137.1   22.68
  5153.6   24.38    5169   23.19  5204.1   23.84  5216.6   21.22  5235.3   20.94
  5272.7   22.02  5303.8   24.75  5349.3   24.85  5370.8   30.56  5452.1   35.63
#Mann= 3 ,0,0
       0     .12       0 2132.67    .041       0    2305     .12       0
Bank Sta=2132.67,2305
XS Rating Curve= 0 ,0
Exp/Cntr(USF)=0,0
Exp/Cntr=0.3,0.1

Type RM Length L Ch R = 1 ,60957   ,969.4,969.4,969.4
XS GIS Cut Line= 6
2107974.03011954348566.1976154132107411.41057779 346511.09306813
2107043.38284408345745.963747439 2106676.2036752345220.885833417
2106224.69277549 344798.982205822105057.85128235344174.523806138
#Sta/Elev= 30
       0   21.17   175.7   20.56     220   18.73   298.5   18.97   421.4   15.91
   625.9   13.94   793.1   13.31   883.8   14.68  1089.8   13.78  1103.5    14.5
  1352.5   11.09  1482.1    7.38  1540.1    7.84  1724.3    4.94 1870.875.583691
 1897.71      -1 1999.23      -1    20205.037807    2705    5.28  2865.4     6.1
  2883.6    7.12    2971     5.9  3074.1    7.62  3421.2    8.11  3781.5   11.47
  4114.3   11.54  4241.5   12.57  4362.9   11.59  5113.6   18.98  5563.5   20.74
#Mann= 3 ,0,0
       0     .12       0 1870.87    .041       0    2020     .12       0
Bank Sta=1870.87,2020
XS Rating Curve= 0 ,0
Exp/Cntr(USF)=0,0
Exp/Cntr=0.3,0.1

Type RM Length L Ch R = 1 ,59988   ,995.7,995.7,995.7
XS GIS Cut Line= 6
2108565.32228052348371.6293052752108376.18519788346366.723367857
2108166.34421596345931.3629740592107645.84183687345368.922193977
2106910.35740571344764.4410710632105062.22230429344046.441724679
#Sta/Elev= 30
       0   22.29    96.6   22.56     209   19.61   549.5    16.2  1091.8   13.69
  1378.2   10.22  1450.5    6.91  1532.7    5.72    1875  4.9276 1923.02    -.87
 2000.65    -.89    2025 4.97617    3070    5.38  3232.1    7.99  3459.3    9.28
  4154.7    9.55  4436.8    13.5  4753.6   12.06  4763.9   13.12  4778.2   12.06
    4878    12.2  5045.8   13.98  5207.2    13.3  5279.7   15.24  5345.1   14.68
  5362.7   16.11  5534.7   15.68  5644.4   18.73  5739.4   19.49  6201.4   20.94
#Mann= 3 ,0,0
       0     .12       0    1875    .041       0    2025     .12       0
Bank Sta=1875,2025
XS Rating Curve= 0 ,0
Exp/Cntr(USF)=0,0
Exp/Cntr=0.5,0.3

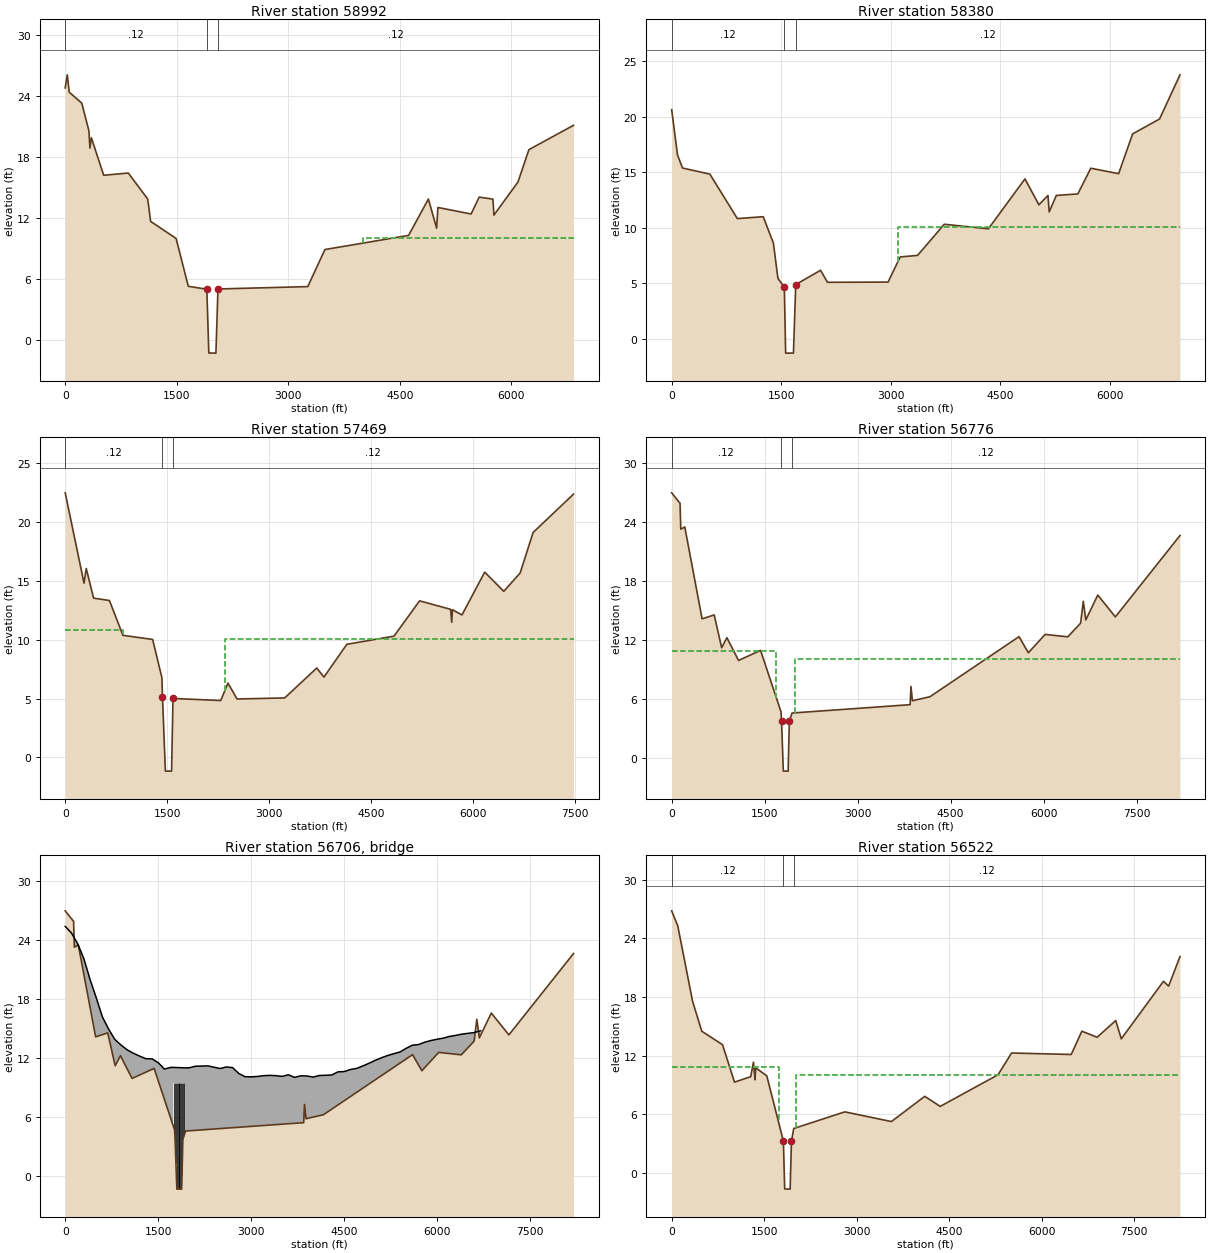
Type RM Length L Ch R = 1 ,58992   ,612.6,612.6,612.6
XS GIS Cut Line= 6
2109643.36416889348136.061039782 2109419.2208664346405.377529302
2108901.83713806345764.4344459052108097.35273658345035.840382716
2107248.48796725344541.4190195852105134.72207127343946.508637072
#Sta/Elev= 30
       0   24.82    27.9   26.11    54.4    24.4   223.1   23.32   319.1   20.59
   332.4   18.91   352.2   19.91   517.7   16.22   848.6   16.44    1110   13.88
  1148.9   11.68  1491.6      10  1655.7    5.29    19055.002243 1931.73   -1.28
 2027.04   -1.29    20555.025343  3262.9    5.26  3493.7    8.91  4618.7    10.3
  4885.3   13.88  4996.1   11.01  5013.1   13.05  5459.7   12.41  5568.8   14.07
  5752.9   13.87  5766.6    12.3  6090.5   15.56  6237.1   18.74  6837.5   21.14
#Mann= 3 ,0,0
       0     .12       0    1905    .041       0    2055     .12       0
#XS Ineff= 2 , 0
                            4000           10.03
Permanent Ineff=
       F       F
Bank Sta=1905,2055
XS Rating Curve= 0 ,0
Exp/Cntr(USF)=0,0
Exp/Cntr=0.5,0.3

Type RM Length L Ch R = 1 ,58380   ,910.6,910.6,910.6
XS GIS Cut Line= 5
2110712.77288746347311.8579898082109773.11276474345805.532602232
2108460.91386474344677.8068074582107503.50920049344364.812564901
2105104.22212249343861.947563075
#Sta/Elev= 30
       0   20.62    80.6   16.54   148.1   15.38   523.3   14.83   900.1   10.83
  1254.4      11  1393.6    8.63  1455.5    5.46 1543.58    4.65 1561.55   -1.27
 1668.17   -1.27    17004.898249  2040.4    6.18  2134.4     5.1  2965.2    5.12
  3130.8    7.38  3368.8    7.52  3734.8   10.32  4339.1    9.91  4840.4    14.4
  5031.2   12.07  5155.6   12.91  5172.3   11.43  5269.6   12.91  5564.6   13.05
  5742.4   15.36  6123.4   14.87  6315.7   18.45  6684.6   19.79  6964.3   23.76
#Mann= 3 ,0,0
       0     .12       0 1543.58    .041       0    1700     .12       0
#XS Ineff= 2 , 0
                            3100           10.03
Permanent Ineff=
       F       F
Bank Sta=1543.58,1700
XS Rating Curve= 0 ,0
Exp/Cntr(USF)=0,0
Exp/Cntr=0.5,0.3

Type RM Length L Ch R = 1 ,57469   ,692.5,692.5,692.5
XS GIS Cut Line= 6
 2111543.9979528346799.4654006252110720.29886494345621.270508605
2110432.87640412345334.4647799842109800.23240003344896.283538183
2108623.27742312  344521.24242642105070.32233361343764.748045568
#Sta/Elev= 30
       0   22.49   277.2   14.81   309.7   16.06   418.2   13.54   651.1   13.34
   849.8   10.38  1287.4   10.03  1423.1    6.79 1432.21    5.13  1474.9   -1.16
 1566.09   -1.16  1586.85.015964  2289.7    4.84  2396.2    6.32  2530.4    4.97
  3231.5    5.06  3703.4     7.6  3808.9    6.83  4147.1    9.62  4840.5   10.31
  5217.1   13.31  5673.7   12.59  5690.5   11.49  5700.5   12.56  5841.1   12.11
  6175.8   15.75  6456.9   14.12  6697.9   15.68  6888.7   19.12  7483.6   22.38
#Mann= 3 ,0,0
       0     .12       0 1432.21    .041       0  1586.8     .12       0
#XS Ineff= 2 , 0
             850   10.87    2350           10.03
Permanent Ineff=
       F       F
Bank Sta=1432.21,1586.8
XS Rating Curve= 0 ,0
Exp/Cntr(USF)=0,0
Exp/Cntr=0.5,0.3

Type RM Length L Ch R = 1 ,56776   ,254.1,254.1,254.1
BEGIN DESCRIPTION:
HEC-2 RS: 218448
END DESCRIPTION:
XS GIS Cut Line= 6
2112282.70593525346571.0636307492111510.76004851345480.860592143
2111131.56207502345054.5707431452110853.32104535344810.025185703
2110729.34134793344740.5849727232105051.66105604343662.589639585
#Sta/Elev= 30
       0   26.96   135.3   25.89     147   23.26   211.4   23.49   490.8   14.14
   685.9   14.54     806    11.2   891.1   12.22  1078.6    9.91  1434.1   10.93
  1763.5    4.68 1772.133.742357  1800.8   -1.35 1878.42   -1.35 1897.79    3.75
    1942    4.56  3846.3    5.41  3859.6    7.26  3882.9    5.81  4166.1    6.22
  5602.5   12.33    5753   10.69  6023.8   12.56  6388.3   12.31  6595.6    13.7
    6639   15.93  6679.2   14.03  6872.8   16.56  7156.3   14.34  8198.7   22.62
#Mann= 3 ,-1,0
       0     .12       0  1763.5    .041       0    1942     .12       0
#XS Ineff= 2 , 0
            1687   10.87    1983           10.03
Permanent Ineff=
       F       F
Bank Sta=1772.13,1897.79
XS Rating Curve= 0 ,0
Exp/Cntr(USF)=0,0
Exp/Cntr=0.5,0.3

Type RM Length L Ch R = 3 ,56706   ,,,
BEGIN DESCRIPTION:
S-15-41 over Ashepoo River
END DESCRIPTION:
Bridge Culvert--1,0,-1,-1, 0
Deck Dist Width WeirC Skew NumUp NumDn MinLoCord MaxHiCord MaxSubmerge Is_Ogee
53.74202,100,2.6,0, 68, 68, , , 0.98, 0, 2,2,,
       0     100     200     300     400     500     600     700     800     900
    1000    1100    1200    1300    1400    1500    1600    1700    1744    1926
    2000    2100    2200    2300    2400    2500    2600    2700    2800    2900
    3000    3100    3200    3300    3400    3500    3600    3700    3800    3900
    4000    4100    4200    4300    4400    4500    4600    4700    4800    4900
    5000    5100    5200    5300    5400    5500    5600    5700    5800    5900
    6000    6100    6200    6300    6400    6500    6600    6700
   25.38   24.71   23.63   22.11   19.99   18.13   16.17   14.93   13.88   13.31
   12.82   12.47   12.18   11.92    11.9   11.52   10.86   11.03   11.03   10.99
   10.99   11.15   11.17   11.19   11.05   10.92   11.08   11.01   10.41   10.09
   10.07   10.11   10.19   10.22   10.19   10.12   10.28   10.02   10.18   10.16
   10.05   10.21   10.23   10.26   10.58   10.61   10.82   10.93   11.18   11.45
   11.75   12.01   12.24   12.43    12.6   12.98   13.29   13.36    13.6   13.77
    13.9   14.01   14.19   14.29   14.42    14.5   14.58   14.76
                                                                                
                                                                    9.43    9.43
                                                                                
                                                                                
                                                                                
                                                                                
                                                                
      41     141     241     341     441     541     641     741     841     941
    1041    1141    1241    1341    1441    1541    1641    1741    1785    1967
    2041    2141    2241    2341    2441    2541    2641    2741    2841    2941
    3041    3141    3241    3341    3441    3541    3641    3741    3841    3941
    4041    4141    4241    4341    4441    4541    4641    4741    4841    4941
    5041    5141    5241    5341    5441    5541    5641    5741    5841    5941
    6041    6141    6241    6341    6441    6541    6641    6741
   25.38   24.71   23.63   22.11   19.99   18.13   16.17   14.93   13.88   13.31
   12.82   12.47   12.18   11.92    11.9   11.52   10.86   11.03   11.03   10.99
   10.99   11.15   11.17   11.19   11.05   10.92   11.08   11.01   10.41   10.09
   10.07   10.11   10.19   10.22   10.19   10.12   10.28   10.02   10.18   10.16
   10.05   10.21   10.23   10.26   10.58   10.61   10.82   10.93   11.18   11.45
   11.75   12.01   12.24   12.43    12.6   12.98   13.29   13.36    13.6   13.77
    13.9   14.01   14.19   14.29   14.42    14.5   14.58   14.76
                                                                                
                                                                    9.43    9.43
                                                                                
                                                                                
                                                                                
                                                                                
                                                                
Pier Skew, UpSta & Num, DnSta & Num=  ,1758, 2 ,1799, 2 , 0 , 0 , 0 ,,
       1       1
   -1.65    9.69
       1       1
   -1.65    9.69
Pier Skew, UpSta & Num, DnSta & Num=  ,1772, 2 ,1813, 2 , 0 , 0 , 0 ,,
       1       1
   -1.65    9.69
       1       1
   -1.65    9.69
Pier Skew, UpSta & Num, DnSta & Num=  ,1786, 2 ,1827, 2 , 0 , 0 , 0 ,,
       1       1
   -1.65    9.69
       1       1
   -1.65    9.69
Pier Skew, UpSta & Num, DnSta & Num=  ,1800, 2 ,1841, 2 , 0 , 0 , 0 ,,
       1       1
   -1.65    9.69
       1       1
   -1.65    9.69
Pier Skew, UpSta & Num, DnSta & Num=  ,1814, 2 ,1855, 2 , 0 , 0 , 0 ,,
       1       1
   -1.65    9.69
       1       1
   -1.65    9.69
Pier Skew, UpSta & Num, DnSta & Num=  ,1828, 2 ,1869, 2 , 0 , 0 , 0 ,,
       1       1
   -1.65    9.69
       1       1
   -1.65    9.69
Pier Skew, UpSta & Num, DnSta & Num=  ,1842, 2 ,1883, 2 , 0 , 0 , 0 ,,
       1       1
   -1.65    9.69
       1       1
   -1.65    9.69
Pier Skew, UpSta & Num, DnSta & Num=  ,1856, 2 ,1897, 2 , 0 , 0 , 0 ,,
       1       1
   -1.65    9.69
       1       1
   -1.65    9.69
Pier Skew, UpSta & Num, DnSta & Num=  ,1870, 2 ,1911, 2 , 0 , 0 , 0 ,,
       1       1
   -1.65    9.69
       1       1
   -1.65    9.69
Pier Skew, UpSta & Num, DnSta & Num=  ,1884, 2 ,1925, 2 , 0 , 0 , 0 ,,
       1       1
   -1.65    9.69
       1       1
   -1.65    9.69
Pier Skew, UpSta & Num, DnSta & Num=  ,1898, 2 ,1939, 2 , 0 , 0 , 0 ,,
       1       1
   -1.65    9.69
       1       1
   -1.65    9.69
Pier Skew, UpSta & Num, DnSta & Num=  ,1912, 2 ,1953, 2 , 0 , 0 , 0 ,,
       1       1
   -1.65    9.69
       1       1
   -1.65    9.69
Abutment Skew #Up #Dn= , 3 , 3
    1744    1746 1752.46
    7.43    7.43     4.2
    1785    1787 1793.46
    7.43    7.43     4.2
Abutment Skew #Up #Dn= , 3 , 3
  1916.6    1924    1926
    3.73    7.43    7.43
  1957.6    1965    1967
    3.73    7.43    7.43
BR Coef=-1 ,-1 ,-1 ,0.9, 0 ,,,0.8,0,1.2,0,
WSPro=,,,, 1 ,,,, 0 ,,,, 0 ,,,,-1 ,-1 ,-1 , 0 , 0 , 0 , 0 , 0
BC Design=,, 0 ,, 0 ,,,,,,
BC Use User HTab Curves=0
BC User HTab FreeFlow(D)= 0

Type RM Length L Ch R = 1 ,56522   ,616.6,616.6,616.6
BEGIN DESCRIPTION:
HEC-2 RS: 218419
END DESCRIPTION:
XS GIS Cut Line= 6
2112465.11983619 346422.549297062111363.13655015344933.468875854
2111165.40341921344740.6376676242110893.85305968344560.725925455
2110725.69108737 344502.288003772105210.34691174343461.561526106
#Sta/Elev= 30
       0   26.81    98.7   25.28   338.2   17.59     488    14.5   825.3   13.12
  1019.1    9.29  1282.2    9.85  1326.9   11.33  1352.7    9.53  1362.2   10.76
  1543.5    9.93 1812.413.262738 1833.62   -1.63 1922.08   -1.65  1943.2    3.23
  1980.2    4.55  2808.6    6.25  3565.2    5.26  4106.1    7.84  4356.5    6.81
  5294.1   10.04    5515   12.27  6482.5   12.12  6655.3    14.5  6902.9   13.88
  7204.5   15.59  7294.5   13.72  7978.7    19.6  8062.5   19.11    8247   22.13
#Mann= 3 ,-1,0
       0     .12       0 1812.41    .041       0  1980.2     .12       0
#XS Ineff= 2 , 0
            1735   10.87    2017           10.03
Permanent Ineff=
       F       F
Bank Sta=1812.41,1943.2
XS Rating Curve= 0 ,0
Exp/Cntr(USF)=0,0
Exp/Cntr=0.5,0.3