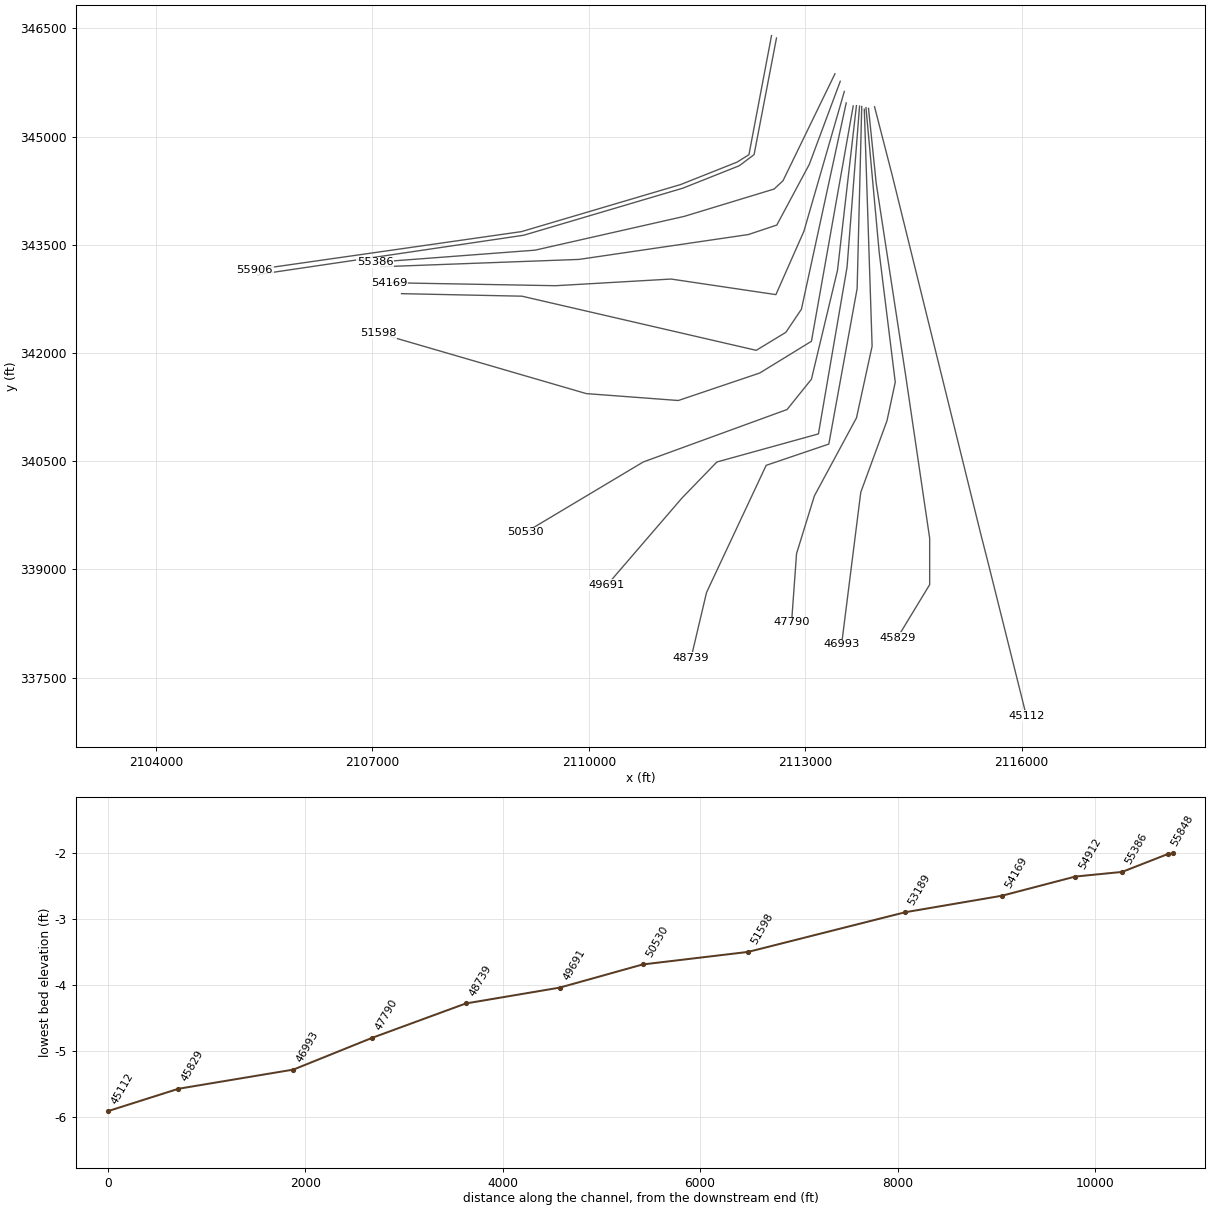
HEC-RAS study AshepooRiver.prj: S-15-41 over Ashepoo River

--- AshepooRiver.g12 (geometry) --- (continued)

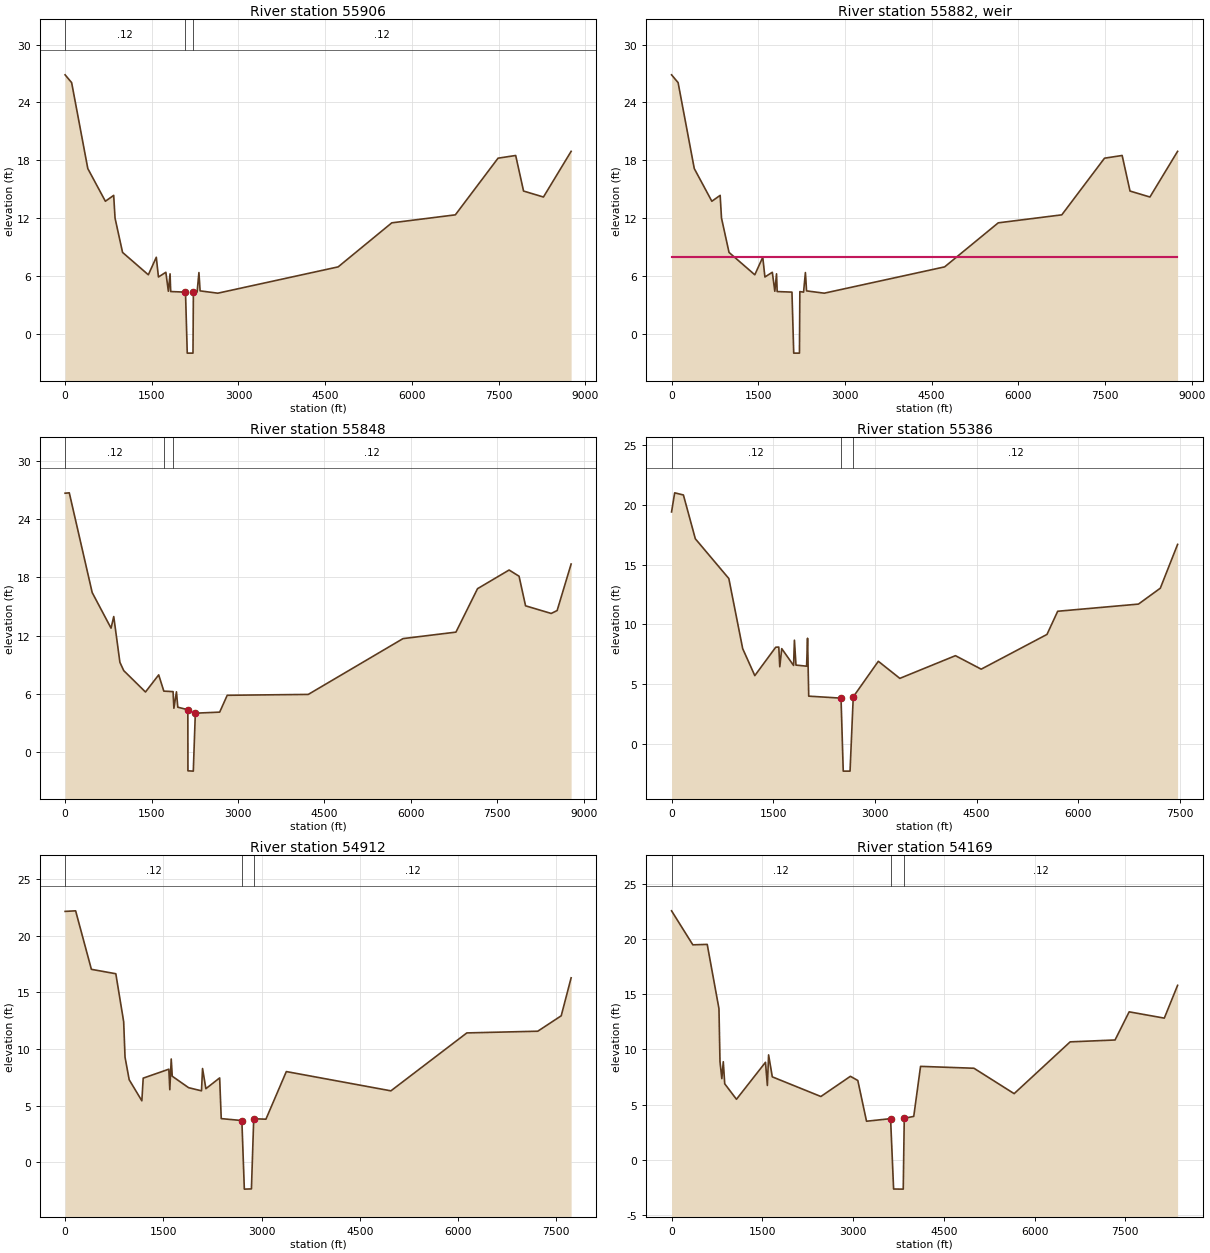
Type RM Length L Ch R = 1 ,55906   ,57.8,57.8,57.8
BEGIN DESCRIPTION:
HEC-2 RS: 217655 (LTR N)
END DESCRIPTION:
Node Name=N
XS GIS Cut Line= 6
2112533.15905625346400.8927124982112220.07912493344749.760027028
2112055.98129461344647.4896658622111273.13088891 344336.30716421
2109066.92062286343683.8963280072105367.39154218343155.008802025
#Sta/Elev= 30
       0   26.87   113.3   26.06   393.2   17.14   697.2   13.75   840.9   14.36
   864.4      12   994.6    8.44  1440.4    6.12  1578.2    7.94  1615.4    5.89
  1743.6    6.38  1786.9    4.41  1816.3    6.22  1827.4    4.38 2083.48    4.32
 2113.92   -2.01 2213.14   -2.01    22204.374556  2284.3    4.32  2315.9    6.35
  2336.1    4.45  2642.3    4.21    4725    6.94  5652.9   11.51  6752.9   12.34
  7491.9   18.22  7797.1    18.5  7933.1   14.81  8277.4   14.19  8756.4   18.93
#Mann= 3 ,-1,0
       0     .12       0 2083.48    .041       0    2220     .12       0
Bank Sta=2083.48,2220
XS Rating Curve= 0 ,0
Exp/Cntr(USF)=0,0
Exp/Cntr=0.3,0.1

Type RM Length L Ch R = 5 ,55882   ,,,
IW Pilot Flow=0
#Inline Weir SE= 2
       0       88751.605       8
IW Dist,WD,Coef,Skew,MaxSub,Min_El,Is_Ogee,SpillHt,DesHd
14,16,2.6,0,0.98,, 0 ,,,2,2,
Inline Weir Flap Gates= 0
IW Outlet Rating Curve= 0 ,False,,

Type RM Length L Ch R = 1 ,55848   ,461.9,461.9,461.9
XS GIS Cut Line= 6
2112602.22771004346368.3947165712112291.51670559344751.338327519
 2112086.1399642 344597.12224529 2111303.2895585344285.939743638
2109097.07929245343633.5289074342105413.49016296343088.701430261
#Sta/Elev= 30
       0   26.71    72.8   26.75   470.2   16.44   797.5   12.76   844.3   13.96
   951.1    9.23  1017.9    8.37    1395    6.16  1624.2    7.93  1713.3    6.25
  1873.8     6.2    1888    4.48  1932.5    6.18  1955.7    4.59    2130    4.33
 2131.85   -1.99 2224.95   -2.02    2260    3.97  2682.7    4.08  2813.6    5.82
  4220.1    5.91  5864.6   11.68  6782.7   12.35  7157.2   16.84  7705.1   18.77
  7877.8   18.13  7990.7   15.07  8435.6   14.28  8538.5   14.58  8781.5   19.39
#Mann= 3 ,-1,0
       0     .12       0  1713.3    .041       0  1873.8     .12       0
Bank Sta=2130,2260
XS Rating Curve= 0 ,0
Exp/Cntr(USF)=0,0
Exp/Cntr=0.3,0.1

Type RM Length L Ch R = 1 ,55386   ,473.7,473.7,473.7
XS GIS Cut Line= 6
2113412.80357095345872.1360190542112692.51382011344389.192395445
2112568.93658486344274.0096954432111325.14543062343895.675353461
2109255.17654151343426.6027141322107037.10774411343258.632919787
#Sta/Elev= 30
       0   19.42      46   21.02   174.8   20.84   350.9   17.17     845   13.84
  1049.3    7.97  1228.1    5.71    1537    8.09    1582     8.1  1596.6    6.45
  1625.4    7.97  1800.2    6.56  1812.4    8.68  1835.5    6.59  1992.1     6.5
  2006.1    8.84  2023.5    3.99    2500 3.82269 2532.68   -2.29 2633.02   -2.29
 2680.38    3.93  3050.2    6.91  3367.6    5.48  4188.1    7.38    4568    6.25
  5538.3    9.16  5696.3    11.1  6887.7    11.7  7209.9   13.03  7465.1    16.7
#Mann= 3 ,-1,0
       0     .12       0    2500    .041       0 2680.38     .12       0
Bank Sta=2500,2680.38
XS Rating Curve= 0 ,0
Exp/Cntr(USF)=0,0
Exp/Cntr=0.3,0.1

Type RM Length L Ch R = 1 ,54912   ,742.9,742.9,742.9
BEGIN DESCRIPTION:
HEC-2 RS: 216847
END DESCRIPTION:
XS GIS Cut Line= 6
2113486.58521938345768.4686934842113057.02499013344616.224982676
2112606.63455243343774.9088022842112213.00337047343643.294728209
2109864.08764517343298.3666103682107113.53128844343196.340419961
#Sta/Elev= 30
       0   22.14   160.9   22.19   401.6   17.03   774.8   16.64   894.7   12.41
   915.5    9.28     979    7.29  1172.3    5.43    1193    7.43  1584.5    8.22
  1599.4    6.41    1621    9.12  1636.7     7.6  1886.1    6.59  2083.4    6.31
  2099.5    8.28  2150.4     6.5  2360.7    7.45  2384.9    3.86    2700    3.69
 2737.58   -2.36 2846.02   -2.34 2881.093.846987  3067.5    3.81    3379    8.01
  4976.3    6.31  6136.1   11.42  7219.6   11.57  7577.5   12.93    7729   16.28
#Mann= 3 ,-1,0
       0     .12       0    2700    .041       0 2881.09     .12       0
Bank Sta=2700,2881.09
XS Rating Curve= 0 ,0
Exp/Cntr(USF)=0,0
Exp/Cntr=0.3,0.1

Type RM Length L Ch R = 1 ,54169   ,980.8,980.8,980.8
BEGIN DESCRIPTION:
HEC-2 RS: 215997
END DESCRIPTION:
XS GIS Cut Line= 6
 2113542.7384924345627.2632154992112982.60128618343689.622050567
2112594.04871233342810.1317107832111140.64623269343026.164538765
2109541.92443561342933.8618398392107232.32289834342975.171662578
#Sta/Elev= 30
       0   22.56   351.7   19.48   589.4   19.52   783.5    13.7   800.5    8.91
   831.1    7.36     855    8.89   878.8    6.89  1072.8    5.49  1552.4    8.84
  1583.5    6.74  1603.9    9.51  1665.2    7.52  2467.9    5.74  2955.8    7.57
  3078.6    7.19  3222.5     3.5    3620 3.73413 3669.99   -2.64 3829.28   -2.65
 3846.123.762544  4003.1    3.94  4115.4    8.47    4998     8.3  5662.3       6
  6588.3   10.69  7330.1   10.86  7563.1   13.41  8144.1   12.84  8363.9   15.81
#Mann= 3 ,-1,0
       0     .12       0    3620    .041       0 3846.12     .12       0
Bank Sta=3620,3846.12
XS Rating Curve= 0 ,0
Exp/Cntr(USF)=0,0
Exp/Cntr=0.3,0.1

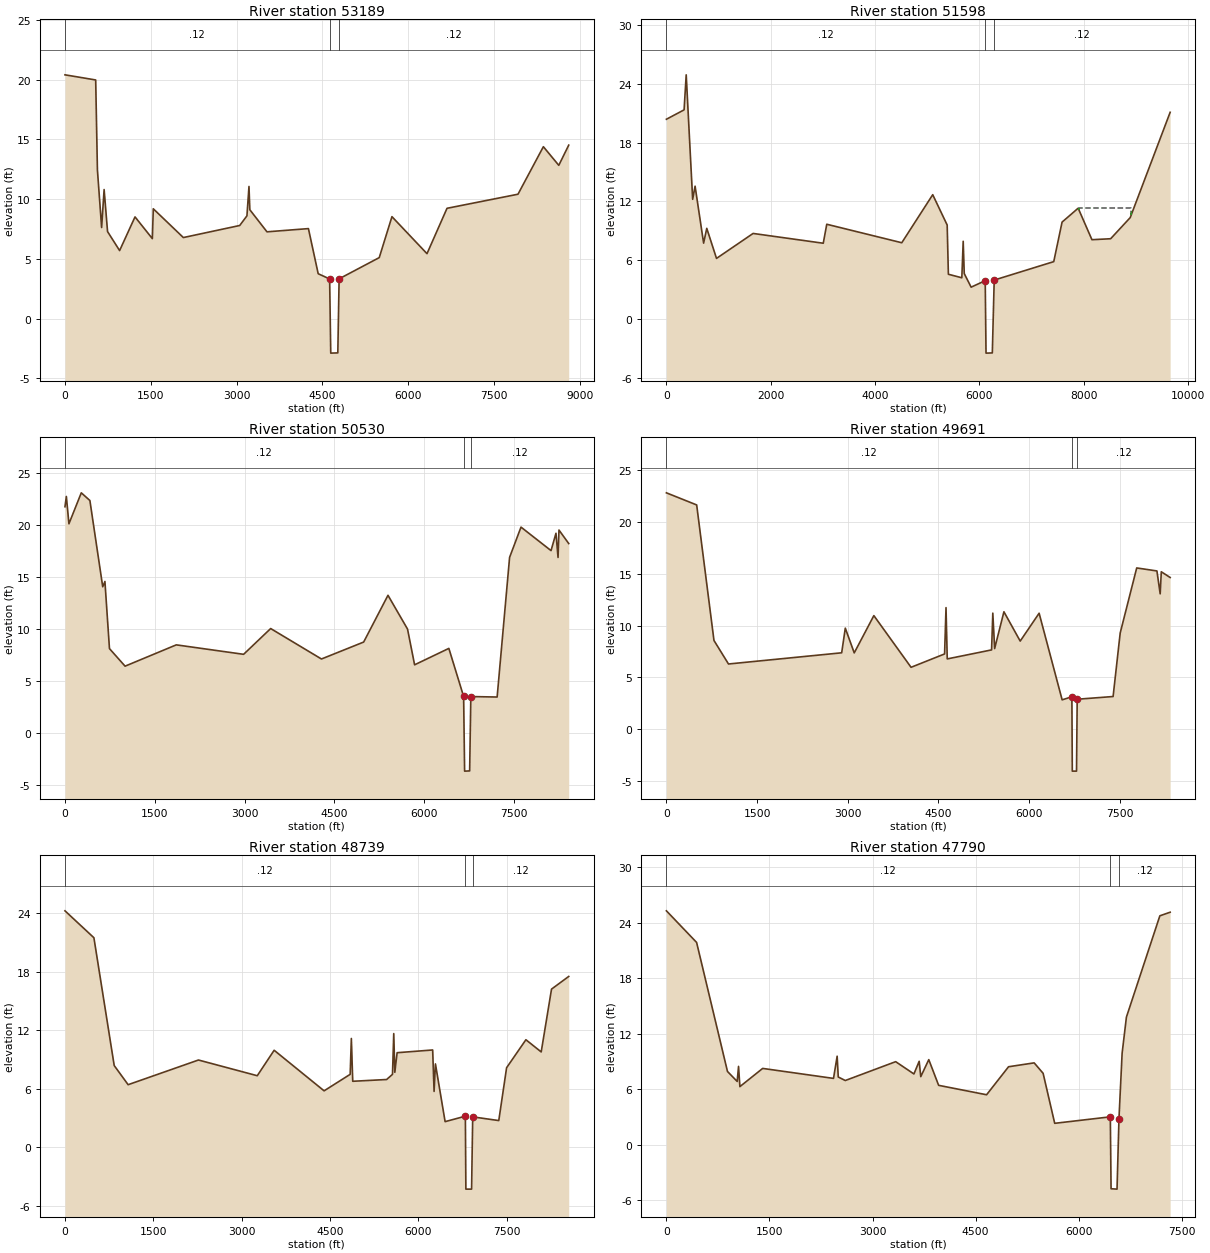
Type RM Length L Ch R = 1 ,53189   ,1590.3,1590.3,1590.3
BEGIN DESCRIPTION:
HEC-2 RS: 215090 (LTR M)
END DESCRIPTION:
Node Name=M
XS GIS Cut Line= 6
2113568.81423419345468.007339637 2112947.9376938342607.997925717
2112732.08088266342287.2343462792112321.38115258342037.902023321
2109072.61770797342788.5819753352107403.45554704  342823.5553852
#Sta/Elev= 30
       0   20.41   536.7   19.98   566.8   12.46   640.4    7.62   683.9    10.8
   744.1    7.28   954.8    5.69    1224    8.51  1526.9    6.69  1543.5    9.19
  2068.7    6.78  3053.7    7.79    3180     8.6  3215.6   11.06  3230.4    9.11
  3530.1    7.26  4254.4    7.53  4425.2    3.75    46253.314335 4644.54    -2.9
 4768.05   -2.88 4790.713.322143    5492     5.1  5714.1    8.53  6326.5    5.43
  6676.4    9.23  7916.8   10.41  8360.3   14.39  8629.8   12.83  8803.3   14.52
#Mann= 3 ,-1,0
       0     .12       0    4625    .041       0 4790.71     .12       0
Bank Sta=4625,4790.71
XS Rating Curve= 0 ,0
Exp/Cntr(USF)=0,0
Exp/Cntr=0.3,0.1

Type RM Length L Ch R = 1 ,51598   ,1068.4,1068.4,1068.4
BEGIN DESCRIPTION:
HEC-2 RS: 214067
END DESCRIPTION:
XS GIS Cut Line= 6
2113665.95705568 345426.336509692113086.88115373342163.439416852
2112369.53776723341723.0682256752111241.00129154341342.111761542
2109965.28864871341437.8266651632107086.50153097342275.881131254
#Sta/Elev= 30
       0    20.4   338.9   21.36   379.5   24.94     503   12.22   549.7   13.56
   713.2    7.74   773.5    9.25   960.1    6.18  1661.4    8.73  3006.1    7.73
  3073.2    9.67  4510.9    7.78  5103.9   12.69  5380.9    9.59    5404    4.56
  5661.7     4.2  5687.9    7.93    5708    4.63  5840.1    3.24    61103.904998
 6125.35    -3.5 6246.04   -3.48 6282.263.966102  7423.3    5.85  7582.9    9.89
  7891.5   11.31  8155.4    8.09  8513.9    8.19    8889   10.35  9654.2   21.11
#Mann= 3 ,-1,0
       0     .12       0    6110    .041       0 6282.26     .12       0
#XS Ineff= 1 ,-1
 7904.23 8907.04   11.37
Permanent Ineff=
       T
Bank Sta=6110,6282.26
XS Rating Curve= 0 ,0
Exp/Cntr(USF)=0,0
Exp/Cntr=0.3,0.1

Type RM Length L Ch R = 1 ,50530   ,839.1,839.1,839.1
BEGIN DESCRIPTION:
HEC-2 RS: 213236
END DESCRIPTION:
XS GIS Cut Line= 6
2113710.59355572345430.4006670612113448.33330875343148.228105745
2113086.53357444341637.1573886812112748.97970278 341217.20142283
2110755.64770619340490.302856961 2109124.3484468339515.562594273
#Sta/Elev= 30
       0   21.75    23.1   22.74    66.1   20.11   272.6   23.09   416.2   22.35
   630.7   14.05   667.3   14.56   743.3     8.1  1004.2    6.41  1859.8    8.46
  2984.3    7.55  3436.5   10.03    4285     7.1  4990.1    8.73  5396.3   13.23
  5722.9    9.98  5840.9    6.54  6413.2    8.12    66603.492058 6676.48   -3.69
 6760.69   -3.67 6780.463.485386  7219.8    3.44    7428   16.88  7618.6   19.79
  8120.2   17.53  8202.9    19.2  8237.4   16.87  8252.8   19.51  8415.8   18.21
#Mann= 3 ,-1,0
       0     .12       0    6660    .041       0 6780.46     .12       0
Bank Sta=6660,6780.46
XS Rating Curve= 0 ,0
Exp/Cntr(USF)=0,0
Exp/Cntr=0.3,0.1

Type RM Length L Ch R = 1 ,49691   ,952,952,952
BEGIN DESCRIPTION:
HEC-2 RS: 212304
END DESCRIPTION:
XS GIS Cut Line= 6
2113753.67471267345423.5593204752113580.43345627 343190.64241309
2113183.51759426340879.1236672472111775.48857235340489.480415901
2111290.56987558 339988.659403132110252.98432053338783.358492686
#Sta/Elev= 30
       0   22.82   500.9   21.65   787.2    8.57  1027.4     6.3  2900.5    7.38
  2960.4    9.76  3108.2    7.37    3433   10.97  4048.6    5.98  4603.5    7.27
  4627.1   11.74  4647.4    6.79  5381.2    7.66  5401.5   11.21  5431.7    7.79
  5585.5   11.34  5854.9    8.51  6167.8    11.2  6548.8    2.84    6710 3.13754
 6716.82   -4.04 6786.62   -4.04 6797.952.897896  7392.1    3.16  7509.4    9.29
  7782.9   15.57  8117.3   15.28  8171.1   13.07  8189.7    15.2  8336.2   14.65
#Mann= 3 ,-1,0
       0     .12       0    6710    .041       0 6797.95     .12       0
Bank Sta=6710,6797.95
XS Rating Curve= 0 ,0
Exp/Cntr(USF)=0,0
Exp/Cntr=0.3,0.1

Type RM Length L Ch R = 1 ,48739   ,948.3,948.3,948.3
BEGIN DESCRIPTION:
HEC-2 RS: 211308
END DESCRIPTION:
XS GIS Cut Line= 6
2113784.01759306345418.4051467052113720.27176802342893.723116748
2113327.76276237340738.0580405182112459.28196653340443.410629815
2111632.31338533338680.5684926832111419.26402097337778.426294558
#Sta/Elev= 30
       0   24.26   491.3    21.5   836.3    8.39  1072.6    6.43  2267.3    8.96
  3265.6    7.35  3552.6    9.96  4400.8     5.8  4843.4    7.49  4863.7   11.17
  4887.2    6.78  5462.6    6.96  5562.3    7.49  5583.7   11.67  5601.8     7.7
  5640.9    9.71  6244.7    9.99  6268.6    5.74  6291.6    8.56    6456    2.64
    68003.201209 6808.59   -4.28 6905.56   -4.28 6924.723.132063  7367.3    2.75
  7500.2    8.17  7828.2   11.04  8087.9    9.79  8263.2   16.23  8555.3   17.53
#Mann= 3 ,-1,0
       0     .12       0    6800    .041       0 6924.72     .12       0
Bank Sta=6800,6924.72
XS Rating Curve= 0 ,0
Exp/Cntr(USF)=0,0
Exp/Cntr=0.3,0.1

Type RM Length L Ch R = 1 ,47790   ,797,797,797
BEGIN DESCRIPTION:
HEC-2 RS: 210260
END DESCRIPTION:
XS GIS Cut Line= 6
2113819.67999959345380.3975931412113927.97080106342095.905734601
2113711.50232809341102.1186541492113127.51502048340019.569395021
2112880.30446054339219.3152655542112811.38049324338267.623629299
#Sta/Elev= 30
       0   25.31   439.5   21.89   888.8    7.93    1030    6.85  1049.7    8.48
  1069.4    6.29  1401.1    8.26  2431.8    7.18  2484.6    9.58    2501    7.33
  2602.9    6.95  3336.4    8.99    3602    7.66  3678.4    9.03  3701.6    7.37
  3818.2    9.21  3961.6    6.43  4659.4    5.41    4979    8.44  5351.9    8.86
  5482.1    7.73  5650.7    2.32    64603.021096 6470.79   -4.76 6557.69    -4.8
 6585.91    2.83  6631.7     9.9  6694.2   13.81  7180.9   24.77  7330.7   25.16
#Mann= 3 ,-1,0
       0     .12       0    6460    .041       0 6585.91     .12       0
Bank Sta=6460,6585.91
XS Rating Curve= 0 ,0
Exp/Cntr(USF)=0,0
Exp/Cntr=0.3,0.1

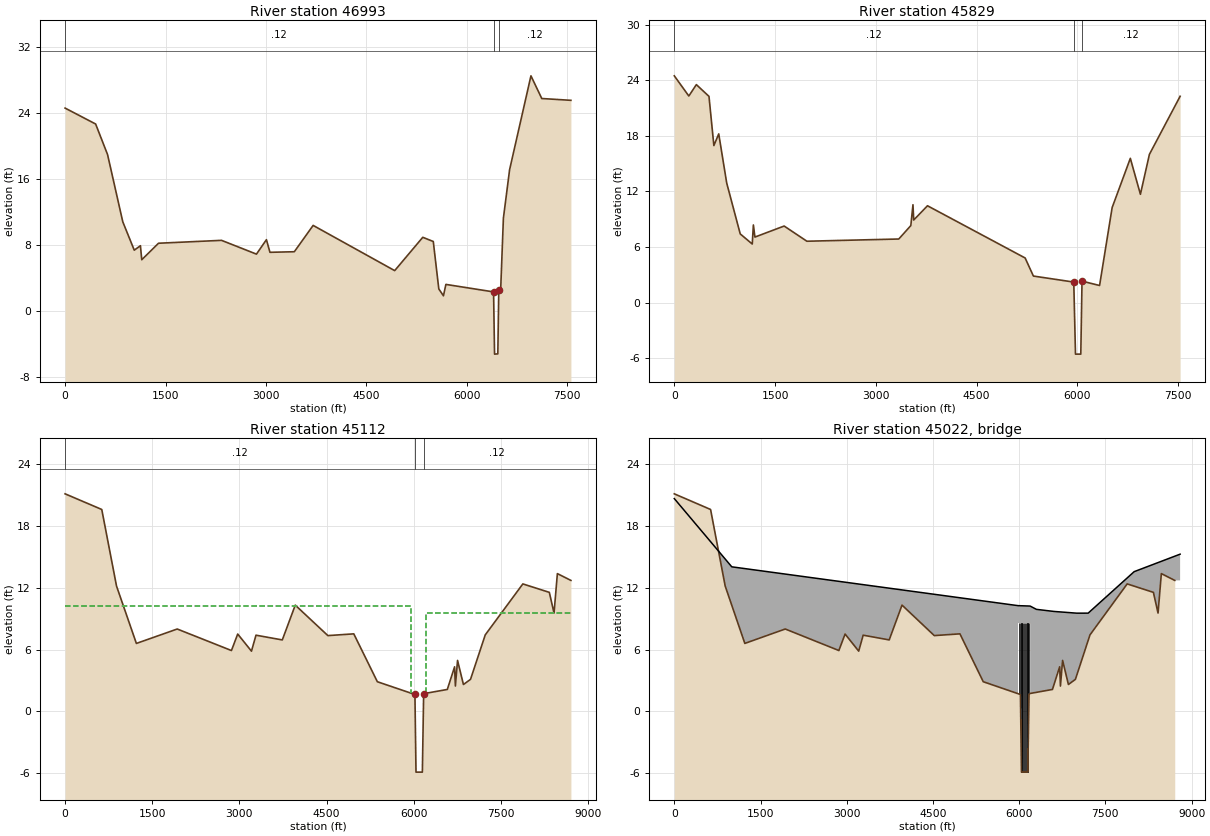
Type RM Length L Ch R = 1 ,46993   ,1164.1,1164.1,1164.1
BEGIN DESCRIPTION:
HEC-2 RS: 209434
END DESCRIPTION:
XS GIS Cut Line= 6
2113842.64379361  345402.5263264 2114026.3655615343394.716572421
2114248.95082345341596.1784298422114134.59979798341062.760749973
2113770.53918435 340068.973669522113505.26959665337962.936515315
#Sta/Elev= 30
       0   24.54   456.4   22.61   634.4   18.91   861.8   10.76  1033.3    7.32
  1125.4    7.86  1145.2    6.16  1395.7    8.16  2336.8    8.51  2858.5    6.84
  3007.3    8.59  3060.2    7.06    3424    7.13    3705   10.32  4923.2    4.84
  5342.6    8.88  5499.5    8.37  5582.1    2.62  5651.4    1.79  5687.8    3.17
    64002.261818 6414.62   -5.28 6463.46   -5.25 6477.612.433743  6507.1    2.75
  6546.8    11.2  6639.6   17.08  6958.3   28.45  7119.9    25.7  7555.2   25.48
#Mann= 3 ,-1,0
       0     .12       0    6400    .041       0 6477.61     .12       0
Bank Sta=6400,6477.61
XS Rating Curve= 0 ,0
Exp/Cntr(USF)=0,0
Exp/Cntr=0.3,0.1

Type RM Length L Ch R = 1 ,45829   ,717.4,717.4,717.4
BEGIN DESCRIPTION:
HEC-2 RS: 208274 (LTR L)
END DESCRIPTION:
Node Name=L
XS GIS Cut Line= 6
2113877.86478229345392.9455559052113984.30492154344357.593753259
2114390.07680005 341709.099288592114726.00750383339431.354087047
 2114725.9193221338789.0864046892114276.75018094338049.327786138
#Sta/Elev= 30
       0   24.48   216.4    22.3   328.5   23.53   516.6   22.26   589.2   16.95
   661.7   18.21   780.5    12.9   981.8    7.41  1160.7    6.32  1177.3    8.38
  1200.5    7.07  1635.5    8.26  1974.1    6.62    3342    6.86  3521.3    8.31
  3553.3   10.56  3564.4    8.91  3769.4   10.45  5223.3    4.81  5346.1    2.86
 5947.11    2.21  5972.7   -5.57 6051.68   -5.57 6069.96    2.31  6331.3    1.84
  6518.3   10.25  6789.1   15.57  6939.3   11.69  7073.2      16  7530.4   22.27
#Mann= 3 ,-1,0
       0     .12       0 5947.11    .041       0 6069.96     .12       0
Bank Sta=5947.11,6069.96
XS Rating Curve= 0 ,0
Exp/Cntr(USF)=0,0
Exp/Cntr=0.5,0.3

Type RM Length L Ch R = 1 ,45112   ,148.2,148.2,148.2
BEGIN DESCRIPTION:
HEC-2 RS: 207385
END DESCRIPTION:
XS GIS Cut Line= 5
2113961.77074045345415.0293650792114204.83077183344471.731700322
2115437.79764054339477.5591892312115543.63379055339062.969763302
2116067.18892544336966.980577882
#Sta/Elev= 30
       0   21.12   631.4    19.6   885.6   12.16  1227.2    6.59  1930.4    7.99
  2863.3     5.9  2971.5     7.5  3208.1    5.84  3285.9    7.39  3738.9    6.93
    3962   10.31  4523.1    7.35  4969.3    7.52  5374.9    2.87  6021.8    1.63
 6040.13   -5.91 6149.65   -5.91 6171.84    1.71  6579.2    2.12  6704.4    4.32
  6717.9    2.45  6755.2    4.94  6856.6     2.6  6978.4     3.1  7232.1    7.42
  7879.2   12.37  8334.8   11.55    8416    9.54  8473.5   13.37  8706.5   12.71
#Mann= 3 ,-1,0
       0     .12       0  6021.8    .041       0 6171.84     .12       0
#XS Ineff= 2 , 0
            5955   10.27    6215            9.53
Permanent Ineff=
       F       F
Bank Sta=6021.8,6171.84
XS Rating Curve= 0 ,0
Exp/Cntr(USF)=0,0
Exp/Cntr=0.5,0.3

Type RM Length L Ch R = 3 ,45022   ,,,
BEGIN DESCRIPTION:
SC-303 over Ashepoo River
END DESCRIPTION:
Bridge Culvert--1,0,-1,-1, 0
Deck Dist Width WeirC Skew NumUp NumDn MinLoCord MaxHiCord MaxSubmerge Is_Ogee
25,90,2.6,0, 14, 14, , , 0.98, 0, 2,2,,
       0    1000 5979.99    5980    5980    6190    6190 6190.01    6300    6600
    7000    7200    8000    8800
  20.657  14.031   10.26   10.26   10.26   10.22   10.22   10.22     9.9     9.7
    9.53   9.531   13.56   15.26
                                    8.57    8.53
                                
       0    1000 5979.99    5980    5980    6190    6190 6190.01    6300    6900
    7000    7200    8000    8800
  20.657  14.031   10.26   10.26   10.26   10.22   10.22   10.22     9.9     9.7
    9.53   9.531   13.56   15.26
                                    8.57    8.53
                                
Pier Skew, UpSta & Num, DnSta & Num=  ,5995, 2 ,5995, 2 , 0 , 0 , 0 ,,
     1.5     1.5
      -6    9.95
     1.5     1.5
      -6    9.95
Pier Skew, UpSta & Num, DnSta & Num=  ,6010, 2 ,6010, 2 , 0 , 0 , 0 ,,
     1.5     1.5
   -5.91    9.95
     1.5     1.5
   -5.91    9.95
Pier Skew, UpSta & Num, DnSta & Num=  ,6025, 2 ,6025, 2 , 0 , 0 , 0 ,,
     1.5     1.5
      -6    9.95
     1.5     1.5
      -6    9.95
Pier Skew, UpSta & Num, DnSta & Num=  ,6040, 2 ,6040, 2 , 0 , 0 , 0 ,,
     1.5     1.5
   -5.91    9.95
     1.5     1.5
   -5.91    9.95
Pier Skew, UpSta & Num, DnSta & Num=  ,6055, 2 ,6055, 2 , 0 , 0 , 0 ,,
     1.5     1.5
      -6    9.95
     1.5     1.5
      -6    9.95
Pier Skew, UpSta & Num, DnSta & Num=  ,6070, 2 ,6070, 2 , 0 , 0 , 0 ,,
     1.5     1.5
   -5.91    9.95
     1.5     1.5
   -5.91    9.95
Pier Skew, UpSta & Num, DnSta & Num=  ,6085, 2 ,6085, 2 , 0 , 0 , 0 ,,
     1.5     1.5
      -6    9.95
     1.5     1.5
      -6    9.95
Pier Skew, UpSta & Num, DnSta & Num=  ,6100, 2 ,6100, 2 , 0 , 0 , 0 ,,
     1.5     1.5
   -5.91    9.95
     1.5     1.5
   -5.91    9.95
Pier Skew, UpSta & Num, DnSta & Num=  ,6115, 2 ,6115, 2 , 0 , 0 , 0 ,,
     1.5     1.5
      -6    9.95
     1.5     1.5
      -6    9.95
Pier Skew, UpSta & Num, DnSta & Num=  ,6130, 2 ,6130, 2 , 0 , 0 , 0 ,,
     1.5     1.5
   -5.91    9.95
     1.5     1.5
   -5.91    9.95
Pier Skew, UpSta & Num, DnSta & Num=  ,6145, 2 ,6145, 2 , 0 , 0 , 0 ,,
     1.5     1.5
      -6    9.95
     1.5     1.5
      -6    9.95
Pier Skew, UpSta & Num, DnSta & Num=  ,6160, 2 ,6160, 2 , 0 , 0 , 0 ,,
     1.5     1.5
   -5.91    9.95
     1.5     1.5
   -5.91    9.95
Pier Skew, UpSta & Num, DnSta & Num=  ,6175, 2 ,6175, 2 , 0 , 0 , 0 ,,
     1.5     1.5
      -6    9.95
     1.5     1.5
      -6    9.95
Abutment Skew #Up #Dn= , 3 , 3
    5980    5982  5990.7
    6.57    6.57    2.22
    5980    5982  5990.7
    6.57    6.57    2.22
Abutment Skew #Up #Dn= , 3 , 3
 6178.38    6188    6190
    1.72    6.53    6.53
 6178.38    6188    6190
    1.72    6.53    6.53
BR Coef=-1 ,-1 ,-1 ,0.9, 0 ,,,0.8,0,1.2,0,
WSPro=,,,, 1 ,,,, 0 ,,,, 0 ,,,,-1 ,-1 ,-1 , 0 , 0 , 0 , 0 , 0
BC Design=,, 0 ,, 0 ,,,,,,
BC Use User HTab Curves=0
BC User HTab FreeFlow(D)= 0