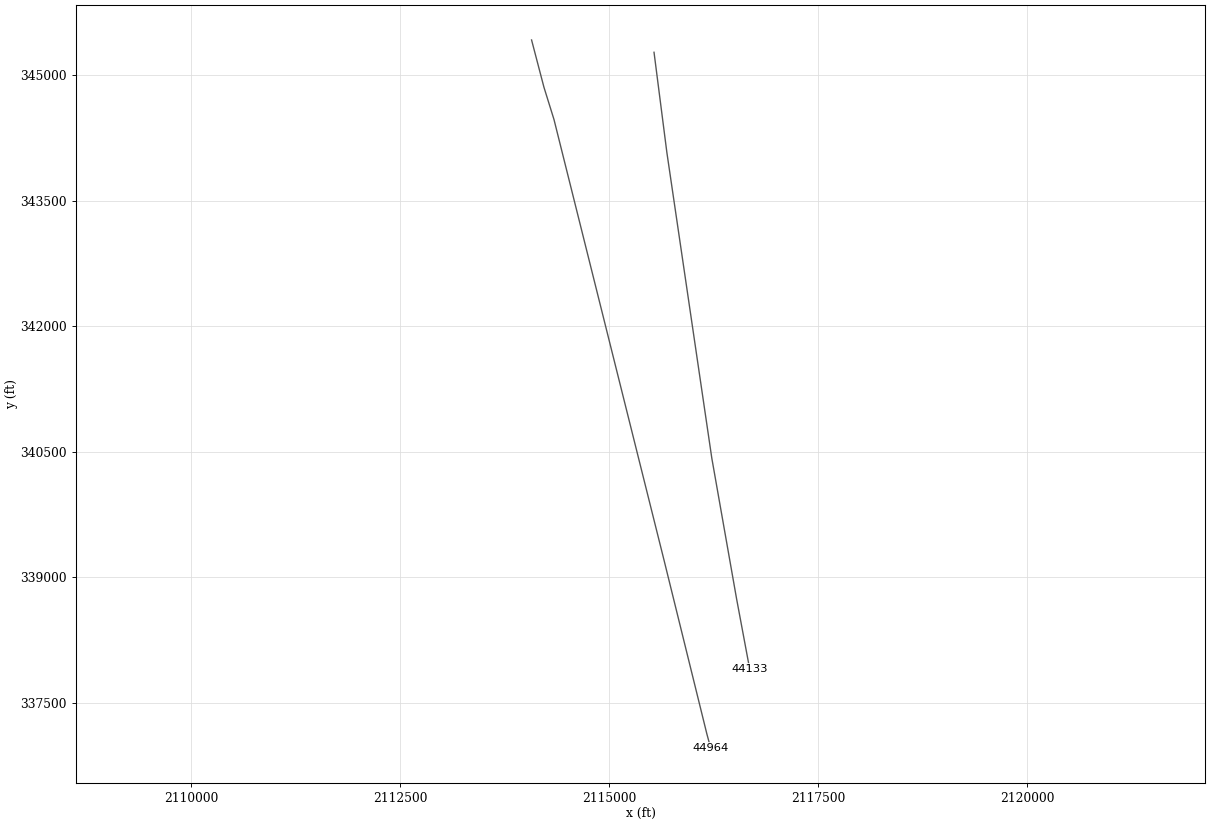
HEC-RAS study AshepooRiver.prj: S-15-41 over Ashepoo River

--- AshepooRiver.g12 (geometry) --- (continued)

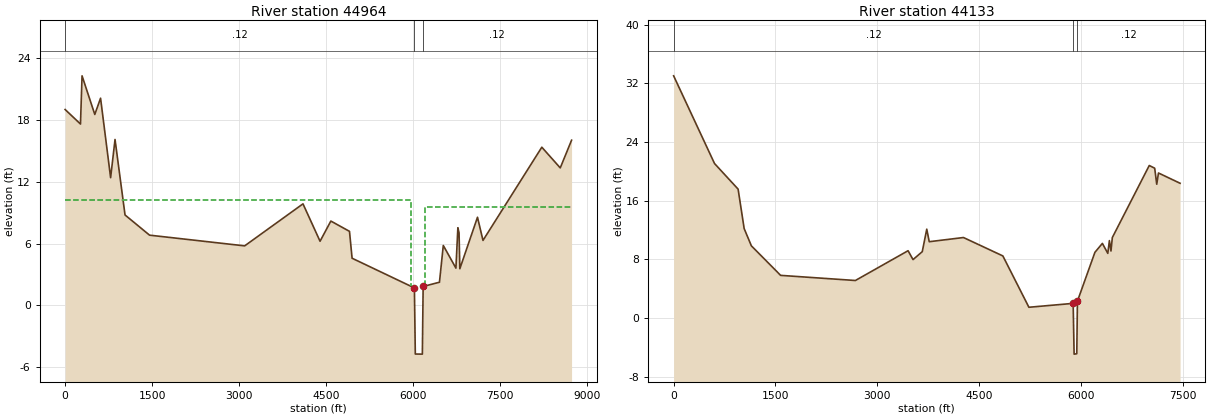
Type RM Length L Ch R = 1 ,44964   ,831.2,831.2,831.2
BEGIN DESCRIPTION:
HEC-2 RS: 207243
END DESCRIPTION:
XS GIS Cut Line= 6
2114073.47904332  345423.60386612114221.42584184344858.595689091
2114341.76739176344471.5221031752115658.66614636339198.105657315
2116169.30860132337126.505086102 2116213.6270204336961.916215067
#Sta/Elev= 30
       0   19.02   264.9   17.61     292   22.29   511.5   18.54     611   20.12
   784.4    12.4   860.3   16.11  1032.8    8.78  1455.5    6.82  3094.8    5.78
  4099.9    9.86  4394.1    6.23  4580.1    8.19  4901.3    7.19  4946.1    4.58
    60201.697643 6035.72   -4.72 6157.21   -4.73  6170.8    1.84  6451.8    2.25
  6518.1    5.82  6735.6    3.62  6769.4    7.54  6789.7    7.04  6803.2    3.56
  7107.5    8.56  7202.2    6.31  8216.2   15.36  8533.9   13.35  8728.9   16.04
#Mann= 3 ,-1,0
       0     .12       0    6020    .041       0  6170.8     .12       0
#XS Ineff= 2 , 0
            5963   10.27    6207            9.53
Permanent Ineff=
       F       F
Bank Sta=6020,6170.8
XS Rating Curve= 0 ,0
Exp/Cntr(USF)=0,0
Exp/Cntr=0.5,0.3

Type RM Length L Ch R = 1 ,44133   ,,,
BEGIN DESCRIPTION:
HEC-2 RS: 206515 (LTR K)
END DESCRIPTION:
Node Name=K
XS GIS Cut Line= 5
2115537.78628686345276.3727564262115691.65318385344076.177599645
2116229.20633682340420.1299743212116525.06356667338740.926794892
2116681.20054587337905.065912506
#Sta/Elev= 30
       0   33.03   602.4   21.07   949.8   17.58    1039    12.2    1145    9.85
  1576.1    5.82  2677.4    5.12  3453.6    9.18  3526.5    7.97  3662.5    9.05
  3728.9   12.12  3765.6   10.41  4269.6   10.98  4850.1    8.47  5233.7    1.47
 5885.54       2 5899.47   -4.92 5938.86   -4.87 5948.39     2.3  6206.1    8.96
  6316.1   10.18    6396    8.82  6419.4   10.56  6442.7    9.14  6462.7   10.98
  7006.6    20.8  7086.7   20.43  7116.8   18.25  7142.3   19.78  7460.8   18.38
#Mann= 3 ,-1,0
       0     .12       0 5885.54    .041       0 5948.39     .12       0
Bank Sta=5885.54,5948.39
XS Rating Curve= 0 ,0
Exp/Cntr(USF)=0,0
Exp/Cntr=0.3,0.1
LCMann Table=0