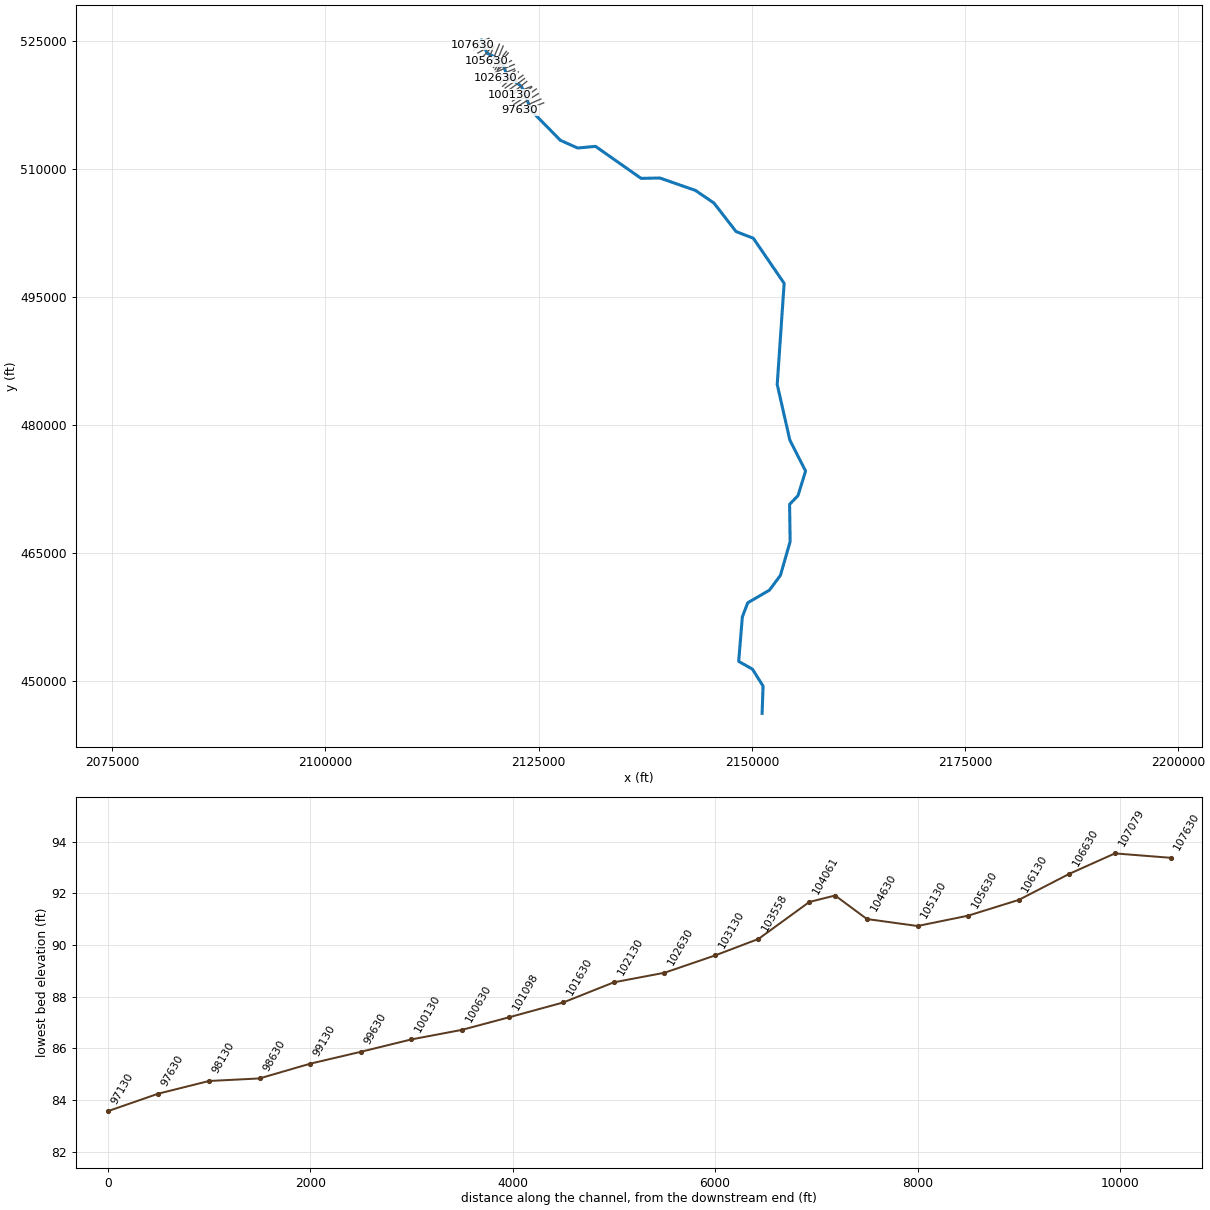
--- IndianFieldsSwamp.prj (project) ---

Proj Title=S-18-19 over Indian Fields Swamp
Current Plan=p15
Default Exp/Contr=0.3,0.1
English Units
Geom File=g02
Geom File=g07
Geom File=g14
Geom File=g01
Flow File=f01
Flow File=f02
Flow File=f03
Plan File=p03
Plan File=p14
Plan File=p15
Plan File=p01
Plan File=p02
Y Axis Title=Elevation
X Axis Title(PF)=Main Channel Distance
X Axis Title(XS)=Station
BEGIN DESCRIPTION:
END DESCRIPTION:
DSS File=dss
DSS Export Rating Curves= 0
DSS Export Rating Curve Sorted= 0
DSS Export Volume Flow Curves= 0
DXF OffsetX= 0
DXF OffsetY= 0
DXF ScaleX= 1
DXF ScaleY= 10

--- IndianFieldsSwamp.p15 (plan) ---

Plan Title=Proposed
Program Version=6.60
Short Identifier=PROP
Geom File=g14
Flow File=f01
Subcritical Flow
K Sum by GR= 0
Std Step Tol= 0.01
Critical Tol= 0.01
Num of Std Step Trials= 20
Max Error Tol= 0.3
Flow Tol Ratio= 0.001
Split Flow NTrial= 30
Split Flow Tol= 0.02
Split Flow Ratio= 0.02
Log Output Level= 0
Friction Slope Method= 1
Unsteady Friction Slope Method= 2
Unsteady Bridges Friction Slope Method= 1
Calc Critical at every XS
Parabolic Critical Depth
Global Vel Dist= 0 , 0 , 0
Global Log Level= 0
CheckData=True
Encroach Param=-1 ,0,0, 0
Flow Ratio Tolerance=0.1
Flow Ratio Min Ratio=0.5
Flow Ratio Max Ratio=4
Flow Ratio Max Iterations= 10
Computation Interval=1MIN
Output Interval=1HOUR
Instantaneous Interval=1HOUR
Mapping Interval=1HOUR
Computation Time Step Use Courant=        0
Computation Time Step Use Time Series=    0
Computation Time Step Count To Double=0
Computation Time Step Max Doubling=0
Computation Time Step Max Halving=0
Computation Time Step Residence Courant=0
Run HTab= 0
Run UNet= 0
Run Sediment= 0
Run PostProcess= 0
Run WQNet= 0
Run RASMapper= 0
UNET Theta= 1
UNET Theta Warmup= 1
UNET ZTol= 0.02
UNET ZSATol= 0.02
UNET MxIter= 20
UNET Max Iter WO Improvement= 0
UNET MaxInSteps= 0
UNET DtIC= 0
UNET DtMin= 0
UNET MaxCRTS= 20
UNET WFStab= 2
UNET SFStab= 1
UNET WFX= 1
UNET SFX= 1
UNET Gravity=32.17405
UNET 1D Methodology=Finite Difference
UNET DSS MLevel= 4
UNET Pardiso=0
UNET DZMax Abort= 100
UNET Use Existing IB Tables=-1
UNET Froude Reduction=False
UNET Froude Limit= 0.8
UNET Froude Power= 4
UNET D1 Cores= 0
UNET WindReference=Eulerian
UNET WindDragFormulation=Hsu (1988)
UNET D2 Coriolis=0
UNET D2 Cores= 0
UNET D2 Theta= 1
UNET D2 Theta Warmup= 1
UNET D2 Z Tol= 0.01
UNET D2 Volume Tol= 0.01
UNET D2 Max Iterations= 20
UNET D2 Advanced Convergence=0
UNET D2 WS Max Tol=0.15
UNET D2 WS RMS Tol=0.002
UNET D2 WS Stall Tol=1
UNET D2 Equation= 0
UNET D2 RampUpFraction=0.1
UNET D2 TimeSlices= 1
UNET D2 Turbulence Formulation=None
UNET D2 Eddy Viscosity=0.3
UNET D2 Transverse Eddy Viscosity=0.1
UNET D2 Smagorinsky Mixing=0.05
UNET D2 BCVolumeCheck=0
UNET D2 Cores=0
UNET D2 SolverType=PARDISO (Direct)
UNET D2 Minimum Iterations= 3
UNET D2 Maximum Iterations= 30
UNET D2 Restart Number= 10
UNET D2 Relaxation Coeff=1.3
UNET D2 SOR Precondition Iterations= 10
UNET D2 ILUT Maximum Fill= 8
UNET D2 ILUT Tolerance=1E-08
UNET D2 Convergence Tolerance=0.00001
PS Theta= 1
PS WS Tol= 0.01
PS Volume Tol= 0.01
PS Max Iterations= 20
PS Equation= 0
PS Advance Time Step=-1
PS Target Courant=0.9
PS Time Slices= 1
PS Iterate With 2D=0
PS Project Initial WSE from DS=-1
PS Ramp Up Initial WSE from US=-1
PS Cores=0
UNET D1D2 MaxIter= 0
UNET D1D2 ZTol=0.01
UNET D1D2 QTol=0.1
UNET D1D2 MinQTol=1
DSS File=dss
Write IC File= 0
Write IC File at Fixed DateTime=0
Write IC File at Sim End=0
Echo Input=False
Echo Parameters=False
Echo Output=False
Write Detailed= 0
HDF Write Warmup=0
HDF Write Time Slices=0
HDF Flush=0
HDF Compression= 1
HDF Chunk Size= 1
HDF Spatial Parts= 1
HDF Use Max Rows=0
HDF Fixed Rows= 1
Calibration Method= 0
Calibration Iterations= 20
Calibration Max Change=0.05
Calibration Tolerance=0.2
Calibration Maximum=1.5
Calibration Minimum=0.5
Calibration Optimization Method= 1
WQ AD Non Conservative
WQ ULTIMATE=-1
WQ Max Comp Step=1HOUR
WQ Output Interval=15MIN
WQ Output Selected Increments= 0
WQ Create Restart=0
WQ Fixed Restart=0
WQ System Summary=0
WQ Write To DSS=0
Sorting and Armoring Iterations= 10
XS Update Threshold= 0.02
Bed Roughness Predictor= 0
Processes Affected by Predictor=Sediment Only
Hydraulics Update Threshold= 0.02
Energy Slope Method= 1
Volume Change Method= 1
Sediment Retention Method= 0
Sediment TS Multiplier= 1
Warm Up Method= 0
XS Weighting Method= 0
Number of US Weighted Cross Sections= 1
Number of DS Weighted Cross Sections= 1
Upstream XS Weight=0
Main XS Weight=1
Downstream XS Weight=0
Number of DS XS's Weighted with US Boundary= 1
Upstream Boundary Weight= 1
Weight of XSs Associated with US Boundary= 0
Number of US XS's Weighted with DS Boundary= 1
Downstream Boundary Weight= 0.5
Weight of XSs Associated with DS Boundary= 0.5
Percentile Method= 0
Sediment Output Level= 3
Mass or Volume Output= 0
Output Increment Type= 1
Profile and TS Output Increment= 1
Transport Output Increment 1
XS Output Flag= 0
XS Output Increment= 10
Read HDF5 Sediment Hotstart= 0
Sediment Hotstart Type= 0
Write Gradation File= 0
Read Gradation Hotstart= 0
Write HDF5 File= 1
Write Binary Output= 1
Write DSS Sediment File= 0
DSS Sediment Output Type= 1
SV Curve= 0
Specific Gage Flag= 0
Subcell Erosion Methods= 0
Subcell Deposition Methods= 0
Advection Scheme= 1
Matrix Solver= 0
Implicit Weighting Factor= 1
Maximum Outer Loop Convergence Iterations= 5
Convergence Maximum Absolute= 0.001
Convergence RMSE= 0.0001
Grain Fractions Max Abs Error= 0.001
Max Subgrid Regions= 1
Max Subgrid Length Scale= 3.402823E+38
Initial Layer Thickness= 3
Min Layer Thickness= 0.1
Max Layer Thickness= 6
Number of Layers= 5

--- IndianFieldsSwamp.p01 (plan) ---

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Plan Title=Natural
Short Identifier=NAT
Geom File=g01
Flow File=f01

--- IndianFieldsSwamp.p02 (plan) ---

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Plan Title=Duplicate Effective
Short Identifier=DE
Geom File=g02
Flow File=f02

--- IndianFieldsSwamp.p03 (plan) ---

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Plan Title=Sensitivity
Short Identifier=Sensitivity
Geom File=g07
Flow File=f03

--- IndianFieldsSwamp.p14 (plan) ---

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Plan Title=Existing
Short Identifier=EX
Geom File=g07
Flow File=f01

--- IndianFieldsSwamp.f01 (steady flow) ---

Flow Title=USGS_RegressionQ
Program Version=6.60
BEGIN FILE DESCRIPTION:
END FILE DESCRIPTION:
Number of Profiles= 6
Profile Names=2Y,10Y,25Y,50Y,100Y,500Y
River Rch & RM=Indian Field Swa,Reach-1         ,107630
    1260    3280    4570    5750    6920    9870
River Rch & RM=Indian Field Swa,Reach-1         ,9417
    1740    4460    6200    7780    9340   13300
Boundary for River Rch & Prof#=Indian Field Swa,Reach-1         , 1
Up Type= 0
Dn Type= 3
Dn Slope=0.002
Boundary for River Rch & Prof#=Indian Field Swa,Reach-1         , 2
Up Type= 0
Dn Type= 3
Dn Slope=0.002
Boundary for River Rch & Prof#=Indian Field Swa,Reach-1         , 3
Up Type= 0
Dn Type= 3
Dn Slope=0.002
Boundary for River Rch & Prof#=Indian Field Swa,Reach-1         , 4
Up Type= 0
Dn Type= 3
Dn Slope=0.002
Boundary for River Rch & Prof#=Indian Field Swa,Reach-1         , 5
Up Type= 0
Dn Type= 3
Dn Slope=0.002
Boundary for River Rch & Prof#=Indian Field Swa,Reach-1         , 6
Up Type= 0
Dn Type= 3
Dn Slope=0.002
DSS Import GetInterval= 0
DSS Import GetPeak= 0
DSS Import FillOption= 0

--- IndianFieldsSwamp.f02 (steady flow) ---

Flow Title=100-year Single
Number of Profiles=1
Profile Names=100-year
River Rch & RM= Indian Field Swa,Reach-1,107461
    1690
River Rch & RM= Indian Field Swa,Reach-1,104461
    1750
River Rch & RM= Indian Field Swa,Reach-1,101961
    1818
River Rch & RM= Indian Field Swa,Reach-1,99461
    1850
River Rch & RM= Indian Field Swa,Reach-1,97461
    2069
River Rch & RM= Indian Field Swa,Reach-1,92961
    2174
River Rch & RM= Indian Field Swa,Reach-1,91188
    2531
River Rch & RM= Indian Field Swa,Reach-1,85528
    2644
River Rch & RM= Indian Field Swa,Reach-1,83323
    3020
River Rch & RM= Indian Field Swa,Reach-1,80461
    3102
River Rch & RM= Indian Field Swa,Reach-1,75733
    3227
River Rch & RM= Indian Field Swa,Reach-1,71987
    3339
River Rch & RM= Indian Field Swa,Reach-1,68309
    3390
River Rch & RM= Indian Field Swa,Reach-1,67461
    3508
River Rch & RM= Indian Field Swa,Reach-1,60144
    3801
River Rch & RM= Indian Field Swa,Reach-1,58378
    3943
River Rch & RM= Indian Field Swa,Reach-1,54961
    3979
River Rch & RM= Indian Field Swa,Reach-1,51461
    4047
River Rch & RM= Indian Field Swa,Reach-1,46232
    4569
River Rch & RM= Indian Field Swa,Reach-1,43460
    4663
River Rch & RM= Indian Field Swa,Reach-1,37844
    4701
River Rch & RM= Indian Field Swa,Reach-1,36461
    4729
River Rch & RM= Indian Field Swa,Reach-1,33870
    4912
River Rch & RM= Indian Field Swa,Reach-1,29461
    5507
River Rch & RM= Indian Field Swa,Reach-1,23371
    5540
River Rch & RM= Indian Field Swa,Reach-1,21395
    5571
River Rch & RM= Indian Field Swa,Reach-1,20961
    5682
River Rch & RM= Indian Field Swa,Reach-1,16961
    5714
River Rch & RM= Indian Field Swa,Reach-1,15961
    5725
River Rch & RM= Indian Field Swa,Reach-1,12461
    5755
River Rch & RM= Indian Field Swa,Reach-1,8205
    7400
River Rch & RM= Indian Field Swa,Reach-1,5500
    7430
River Rch & RM= Indian Field Swa,Reach-1,4000
    7441
Boundary for River Rch & Prof#=Indian Field Swa,Reach-1,1
Up Type=0
Dn Type=3
Dn Slope=0.002

--- IndianFieldsSwamp.f03 (steady flow) ---

Flow Title=Sensitivity
Program Version=6.60
Number of Profiles= 3
Profile Names=100Y-3,100Y,100Y+3
River Rch & RM=Indian Field Swa,Reach-1         ,107630
    6920    6920    6920
River Rch & RM=Indian Field Swa,Reach-1         ,9417
    9340    9340    9340
Boundary for River Rch & Prof#=Indian Field Swa,Reach-1         , 1
Up Type= 0
Dn Type= 1
Dn Known WS=40.49
Boundary for River Rch & Prof#=Indian Field Swa,Reach-1         , 2
Up Type= 0
Dn Type= 1
Dn Known WS=43.49
Boundary for River Rch & Prof#=Indian Field Swa,Reach-1         , 3
Up Type= 0
Dn Type= 1
Dn Known WS=46.49
DSS Import GetInterval= 0
DSS Import GetPeak= 0
DSS Import FillOption= 0

--- IndianFieldsSwamp.g14 (geometry) ---

Geom Title=Proposed
Program Version=6.60

River Reach=Indian Field Swa,Reach-1
Reach XY= 30
      2118288.29       525062.16      2118955.39       523528.35
      2120648.43        522700.4      2121312.48       520888.04
      2122993.51       519640.97       2124181.2       516753.99
      2127559.91       513322.44      2129580.58       512423.52
      2131677.85       512616.52      2137019.28       508872.32
      2139219.53       508913.64      2143396.56       507457.83
       2145551.5       505991.65      2148152.32       502646.04
      2150180.25       501860.21      2153790.57       496582.04
        2152978.       484744.12      2154459.86       478228.84
      2156305.04       474611.96      2155415.89       471733.58
      2154429.18        470712.2       2154493.3       466356.19
      2153350.16       462390.05       2152062.9       460666.57
      2149526.09       459190.342148889.67189297457537.557636352
      2148459.05       452334.88      2150079.38       451415.63
       2151320.1       449436.34      2151206.67       446243.51

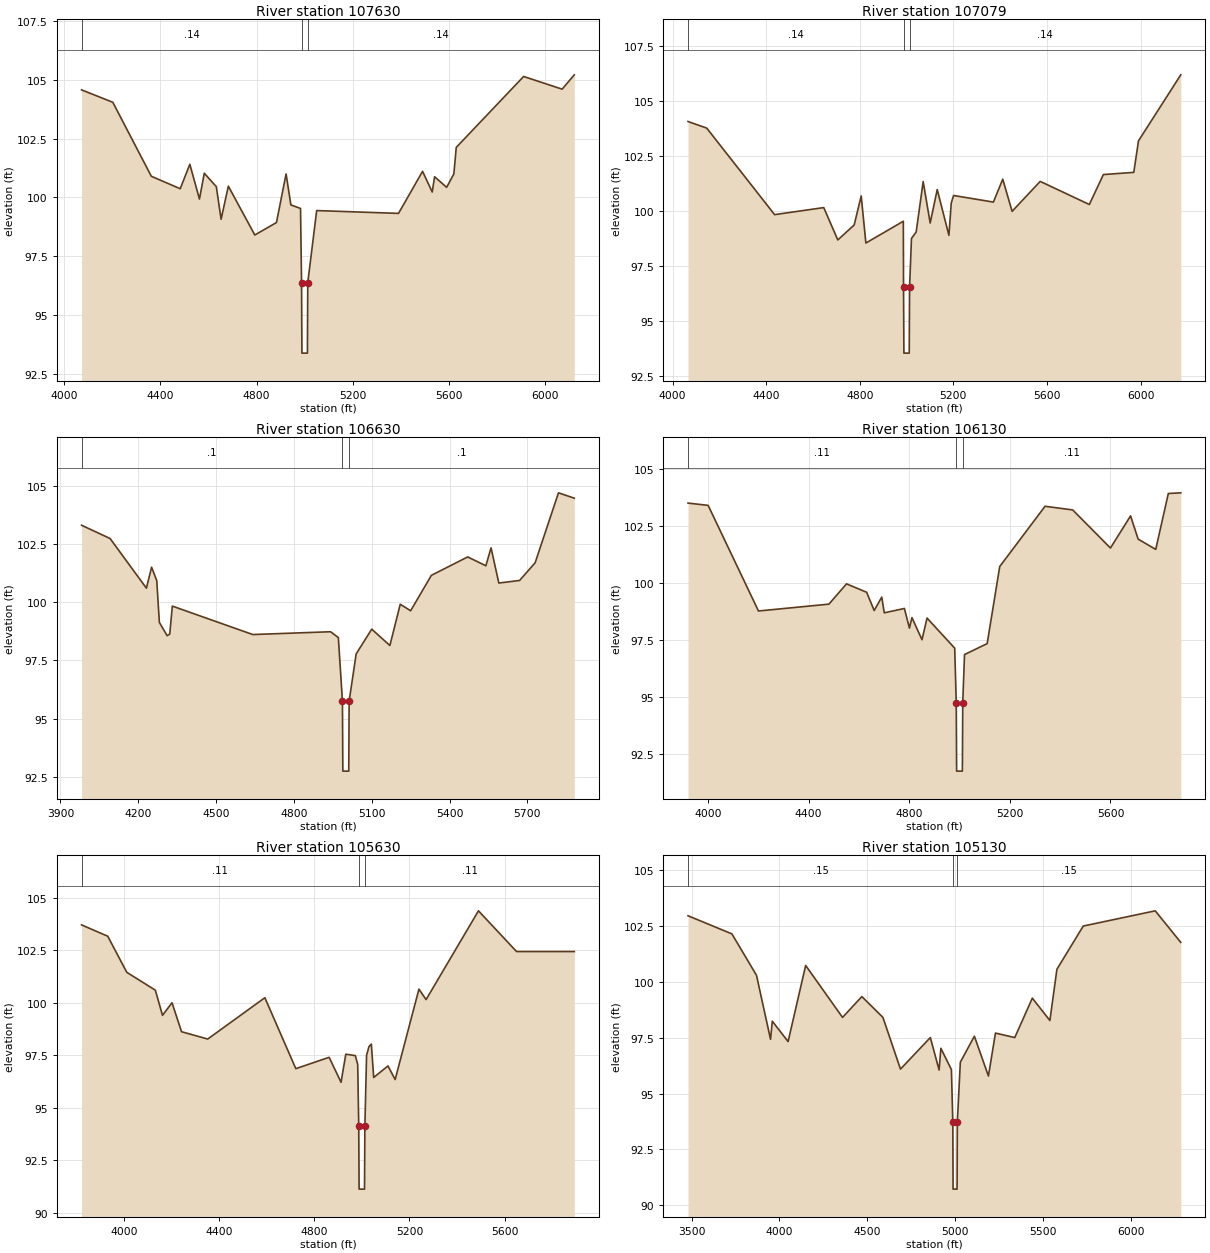
Type RM Length L Ch R = 1 ,107630  ,550,550,550
BEGIN DESCRIPTION:
Indian Field Swamp 215.0
END DESCRIPTION:
XS GIS Cut Line= 3
      2119186.83       525263.58      2118322.11       524928.98
      2117275.07       524529.67
#Sta/Elev= 30
  4072.8  104.58  4202.8  104.05  4362.8   100.9  4482.8  100.37  4522.8  101.41
  4562.8   99.93  4582.8  101.03  4632.8  100.46  4652.8   99.07  4682.8  100.48
  4792.8    98.4  4882.8   98.93  4922.8     101  4942.8   99.68  4982.8   99.53
  4987.1   96.37  4988.6   93.37  5011.4   93.37  5012.9   96.37    5050   99.44
    5390   99.32    5490  101.11    5530  100.23    5540  100.88    5590  100.43
    5620     101    5630  102.13    5910  105.15    6070  104.61  6120.6  105.22
#Mann= 3 ,-1,0
  4072.8     .14       0  4987.1    .045       0  5012.9     .14       0
Bank Sta=4987.1,5012.9
XS Rating Curve= 0 ,0
Exp/Cntr=0.3,0.1

Type RM Length L Ch R = 1 ,107079  ,450,450,450
BEGIN DESCRIPTION:
Indian Field Swamp 214.0
END DESCRIPTION:
XS GIS Cut Line= 3
      2119342.15       524828.18      2118506.08       524410.15
      2117424.59        523961.8
#Sta/Elev= 30
  4066.2  104.06  4146.2  103.76  4436.2   99.83  4646.2  100.15  4706.2   98.68
  4776.2   99.36  4806.2  100.68  4826.2   98.54  4986.2   99.53  4987.1   96.54
  4988.6   93.54  5011.4   93.54  5012.9   96.54    5021   98.75    5041   99.04
    5071  101.33    5101   99.45    5131  100.97    5181   98.89    5191  100.36
    5201   100.7    5371   100.4    5411  101.44    5451   99.98    5571  101.34
    5781  100.29    5841  101.65    5971  101.75    5991  103.18  6171.7  106.18
#Mann= 3 ,-1,0
  4066.2     .14       0  4987.1    .045       0  5012.9     .14       0
Bank Sta=4987.1,5012.9
XS Rating Curve= 0 ,0
Exp/Cntr=0.3,0.1

Type RM Length L Ch R = 1 ,106630  ,500,500,500
BEGIN DESCRIPTION:
Indian Field Swamp 213.0
END DESCRIPTION:
XS GIS Cut Line= 3
      2119537.68       524483.11      2118649.48       523984.26
      2117883.68        523548.7
#Sta/Elev= 30
  3981.3   103.3  4091.3  102.73  4231.3   100.6  4251.3   101.5  4271.3  100.92
  4281.3   99.13  4311.3   98.56  4321.3   98.63  4331.3   99.83  4641.3   98.61
  4941.3   98.73  4971.3   98.48  4987.1   95.75  4988.6   92.75  5011.4   92.75
  5012.9   95.75    5040   97.78    5100   98.84    5170   98.14    5210   99.91
    5250   99.63    5330  101.15    5470  101.94    5540  101.56    5560  102.33
    5590  100.82    5670  100.93    5730  101.69    5820  104.69    5881  104.46
#Mann= 3 ,-1,0
  3981.3      .1       0  4987.1    .045       0  5012.9      .1       0
Bank Sta=4987.1,5012.9
XS Rating Curve= 0 ,0
Exp/Cntr=0.3,0.1

Type RM Length L Ch R = 1 ,106130  ,500,500,500
BEGIN DESCRIPTION:
Indian Field Swamp 212.0
END DESCRIPTION:
XS GIS Cut Line= 3
      2119630.77       524382.86       2118918.9       523572.01
      2118297.08       522950.03
#Sta/Elev= 30
    3921  103.49    4001  103.39    4201   98.76    4481   99.06    4551   99.95
    4631   99.58    4661   98.78    4691   99.37    4701   98.68    4781   98.87
    4801   98.01    4811   98.47    4851    97.5    4871   98.45    4981   97.13
  4987.1   94.74  4988.6   91.74  5011.4   91.74  5012.9   94.74    5020   96.85
    5110   97.33    5160  100.71    5340  103.35    5450  103.19    5600  101.52
    5680  102.93    5710  101.91    5780  101.46    5830  103.91  5879.5  103.94
#Mann= 3 ,-1,0
    3921     .11       0  4987.1    .045       0  5012.9     .11       0
Bank Sta=4987.1,5012.9
XS Rating Curve= 0 ,0
Exp/Cntr=0.3,0.1

Type RM Length L Ch R = 1 ,105630  ,500,500,500
BEGIN DESCRIPTION:
Indian Field Swamp 211.0
END DESCRIPTION:
XS GIS Cut Line= 3
      2119778.39       524410.12      2119338.92       523318.02
      2118854.46       522568.33
#Sta/Elev= 30
  3822.8  103.72  3932.8  103.18  4012.8  101.46  4132.8  100.61  4162.8   99.41
  4202.8  100.01  4242.8   98.63  4352.8   98.28  4592.8  100.25  4722.8   96.87
  4862.8   97.41  4912.8   96.22  4932.8   97.56  4972.8   97.49  4982.8   97.07
  4987.1   94.13  4988.6   91.13  5011.4   91.13  5012.9   94.13    5020    97.5
    5030   97.92    5040   98.04    5050   96.45    5110      97    5140   96.35
    5240  100.66    5270  100.16    5490  104.39    5650  102.45  5892.6  102.45
#Mann= 3 ,-1,0
  3822.8     .11       0  4987.1    .045       0  5012.9     .11       0
Bank Sta=4987.1,5012.9
XS Rating Curve= 0 ,0
Exp/Cntr=0.3,0.1

Type RM Length L Ch R = 1 ,105130  ,500,500,500
BEGIN DESCRIPTION:
Indian Field Swamp 210.0
END DESCRIPTION:
XS GIS Cut Line= 3
      2120407.78       524576.23      2119817.64       523174.49
      2119302.35       521996.89
#Sta/Elev= 30
  3479.1  102.94  3729.1  102.13  3869.1  100.28  3949.1   97.42  3959.1   98.23
  4049.1   97.32  4149.1  100.72  4359.1    98.4  4469.1   99.33  4589.1    98.4
  4689.1   96.09  4859.1    97.5  4909.1   96.05  4919.1   97.02  4979.1   96.07
  4987.1   93.73  4988.6   90.73  5011.4   90.73  5012.9   93.73    5030    96.4
    5110   97.56    5190   95.78    5230    97.7    5340    97.5    5440   99.26
    5540   98.26    5580  100.55    5730  102.48    6140  103.16  6285.4  101.75
#Mann= 3 ,-1,0
  3479.1     .15       0  4987.1    .045       0  5012.9     .15       0
Bank Sta=4987.1,5012.9
XS Rating Curve= 0 ,0
Exp/Cntr=0.3,0.1

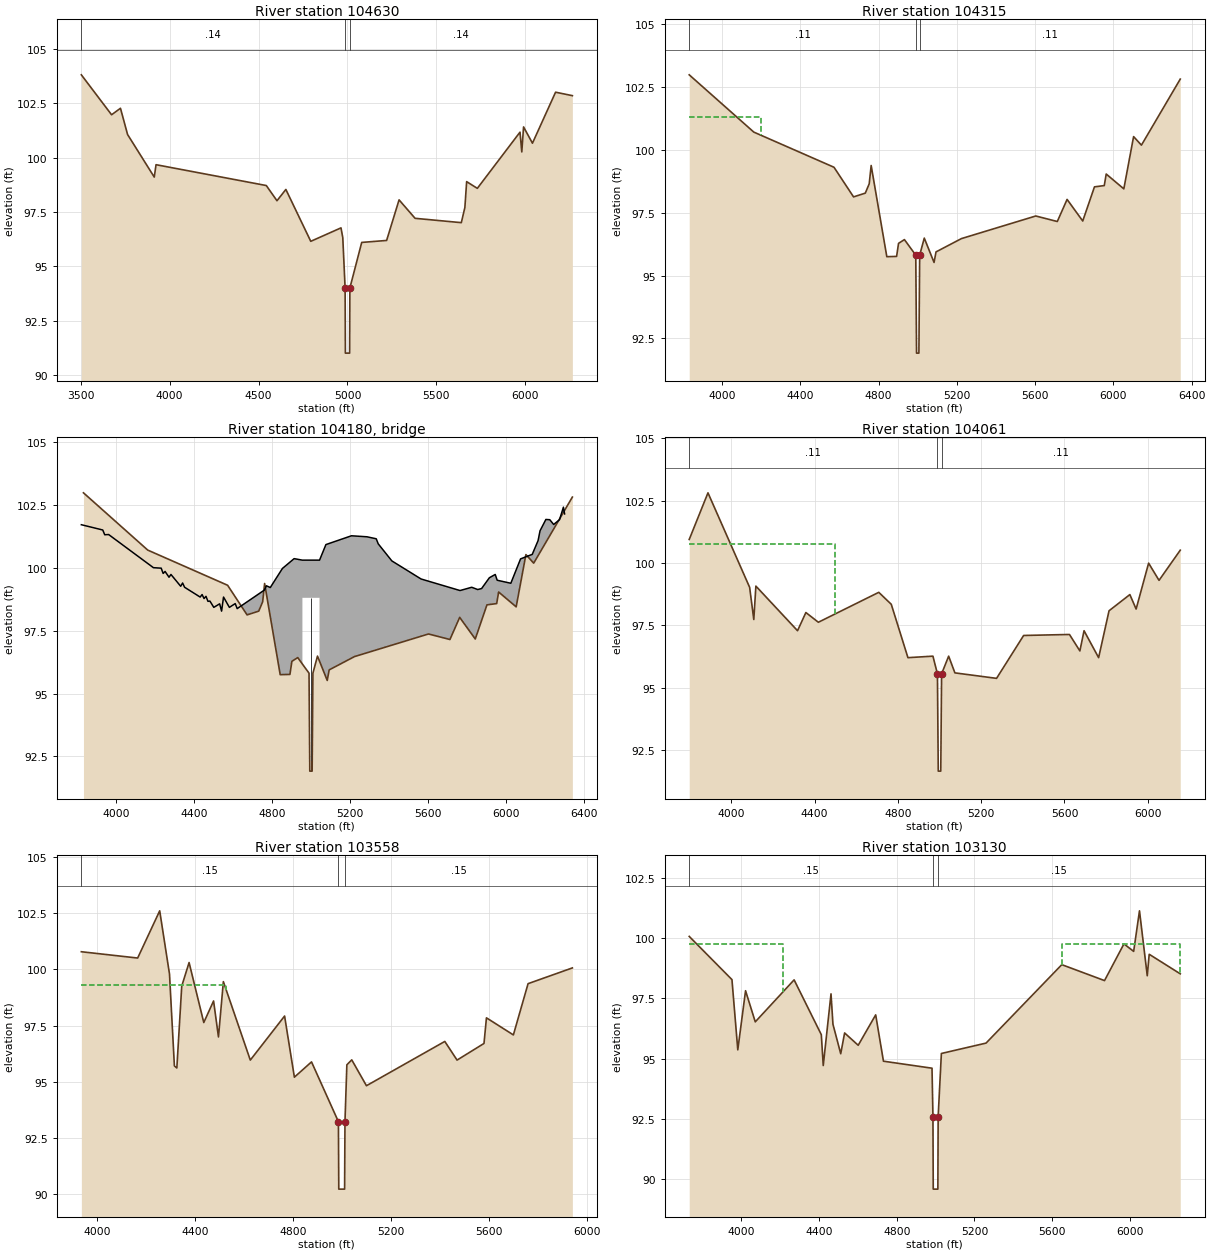
Type RM Length L Ch R = 1 ,104630  ,314,314,314
BEGIN DESCRIPTION:
Indian Field Swamp 209.0
END DESCRIPTION:
XS GIS Cut Line= 3
      2120848.52       524369.29       2120277.8       522985.89
       2119712.5        521854.9
#Sta/Elev= 30
  3503.5  103.82  3673.5  101.98  3723.5  102.28  3763.5  101.07  3913.5   99.11
  3923.5   99.68  4543.5   98.72  4603.5   98.02  4653.5   98.54  4793.5   96.15
  4963.5   96.77  4973.5   96.32  4986.6      94  4988.1      91  5011.9      91
  5013.4      94    5080    96.1    5220   96.19    5290   98.06    5380   97.21
    5640   97.01    5660   97.71    5670    98.9    5730   98.59    5970  101.18
    5980  100.27    5990  101.42    6040  100.67    6170  103.02  6264.4  102.86
#Mann= 3 ,-1,0
  3503.5     .14       0  4986.6    .045       0  5013.4     .14       0
Bank Sta=4986.6,5013.4
XS Rating Curve= 0 ,0
Exp/Cntr=0.5,0.3

Type RM Length L Ch R = 1 ,104315  ,255,255,255
BEGIN DESCRIPTION:
Highway S-18-16 at Indian Field - US
END DESCRIPTION:
XS GIS Cut Line= 3
      2121219.57       523736.85      2120520.03       522784.71
      2119901.85       521608.79
#Sta/Elev= 30
    3832  102.99    4162  100.71    4572   99.31    4672   98.13    4732   98.28
    4752   98.65    4762   99.38    4842   95.75    4892   95.76    4902   96.28
    4932   96.43    4990   95.81    4994   91.91    5006   91.91    5010   95.81
  5033.5   96.49  5083.5   95.52  5093.5   95.94  5223.5   96.47  5603.5   97.37
  5713.5   97.15  5763.5   98.03  5843.5   97.17  5903.5   98.53  5953.5   98.58
  5963.5   99.04  6053.5   98.45  6103.5  100.53  6143.5  100.19    6342  102.82
#Mann= 3 ,-1,0
    3832     .11       0    4990    .045       0    5010     .11       0
#XS Ineff= 2 , 0
            4200   101.3
Permanent Ineff=
       F       F
Bank Sta=4990,5010
XS Rating Curve= 0 ,0
Exp/Cntr=0.5,0.3

Type RM Length L Ch R = 3 ,104180  ,,,
BEGIN DESCRIPTION:
Highway S-18-16 at Indian Field - TOR
Structure ID: LDS_IFS_09
Approximate Survey Structure
END DESCRIPTION:
Bridge Culvert--1,0,-1,-1, 0
Deck Dist Width WeirC Skew NumUp NumDn MinLoCord MaxHiCord MaxSubmerge Is_Ogee
117,36,3,0, 60, 60, , , 0.95, 0, 1,1,,
  3821.1  3931.1  3941.1  3961.1  4191.1  4231.1  4241.1  4251.1  4271.1  4281.1
  4331.1  4341.1  4351.1  4431.1  4441.1  4451.1  4461.1  4471.1  4481.1  4501.1
  4531.1  4541.1  4551.1  4581.1  4611.1  4621.1  4761.1  4771.1  4791.1  4853.5
  4913.5    4956    4956    5044    5044  5076.7  5207.8  5287.8  5335.2  5345.2
  5415.2  5565.2  5765.2  5825.2    5856    5876    5916    5946    5956    6026
    6076    6136    6166    6176    6206    6226    6246    6276    6296  6302.1
  101.72  101.51  101.32  101.33  100.01   99.99   99.78   99.86   99.63   99.74
   99.27    99.4   99.23   98.84   98.94   98.78   98.87   98.67   98.68   98.43
   98.57   98.28   98.84   98.43   98.58   98.38   99.12   99.29   99.22   99.98
  100.37  100.31  100.31  100.31  100.31  100.93  101.28  101.24  101.16  100.96
  100.28   99.56    99.1   99.23   99.14   99.18   99.61   99.74   99.51   99.39
  100.36  100.54  101.09  101.48  101.93  101.92  101.73  101.92  102.42  102.15
   71.91   71.91   71.91   71.91   71.91   71.91   71.91   71.91   71.91   71.91
   71.91   71.91   71.91   71.91   71.91   71.91   71.91   71.91   71.91   71.91
   71.91   71.91   71.91   71.91   71.91   71.91   71.91   71.91   71.91   71.91
   71.91   71.91   98.81   98.81   71.91   71.91   71.91   71.91   71.91   71.91
   71.91   71.91   71.91   71.91   71.91   71.91   71.91   71.91   71.91   71.91
   71.91   71.91   71.91   71.91   71.91   71.91   71.91   71.91   71.91   71.91
  3821.1  3931.1  3941.1  3961.1  4191.1  4231.1  4241.1  4251.1  4271.1  4281.1
  4331.1  4341.1  4351.1  4431.1  4441.1  4451.1  4461.1  4471.1  4481.1  4501.1
  4531.1  4541.1  4551.1  4581.1  4611.1  4621.1  4761.1  4771.1  4791.1  4853.5
  4913.5    4956    4956    5044    5044  5076.7  5207.8  5287.8  5335.2  5345.2
  5415.2  5565.2  5765.2  5825.2    5856    5876    5916    5946    5956    6026
    6076    6136    6166    6176    6206    6226    6246    6276    6296  6302.1
  101.72  101.51  101.32  101.33  100.01   99.99   99.78   99.86   99.63   99.74
   99.27    99.4   99.23   98.84   98.94   98.78   98.87   98.67   98.68   98.43
   98.57   98.28   98.84   98.43   98.58   98.38   99.12   99.29   99.22   99.98
  100.37  100.31  100.31  100.31  100.31  100.93  101.28  101.24  101.16  100.96
  100.28   99.56    99.1   99.23   99.14   99.18   99.61   99.74   99.51   99.39
  100.36  100.54  101.09  101.48  101.93  101.92  101.73  101.92  102.42  102.15
   71.91   71.91   71.91   71.91   71.91   71.91   71.91   71.91   71.91   71.91
   71.91   71.91   71.91   71.91   71.91   71.91   71.91   71.91   71.91   71.91
   71.91   71.91   71.91   71.91   71.91   71.91   71.91   71.91   71.91   71.91
   71.91   71.91   98.81   98.81   71.91   71.91   71.91   71.91   71.91   71.91
   71.91   71.91   71.91   71.91   71.91   71.91   71.91   71.91   71.91   71.91
   71.91   71.91   71.91   71.91   71.91   71.91   71.91   71.91   71.91   71.91
Pier Skew, UpSta & Num, DnSta & Num=  ,5000, 2 ,5000, 2 , 0 , 0 , 0 ,0,0
     1.5     1.5
   91.91   98.81
     1.5     1.5
   91.66   98.81
Abutment Skew #Up #Dn= , 2 , 2
    4956    4965
   98.81      96
    4956    4965
   98.81   96.18
Abutment Skew #Up #Dn= , 2 , 2
    5035    5044
   96.48   98.81
    5035    5044
   95.81   98.81
BR Coef=-1 ,-1 , 0 ,1.25, 0 ,,,0.8,0,2,0,
WSPro=,,,, 1 ,,,, 0 ,,,, 0 ,,,,-1 ,-1 ,-1 , 0 , 0 , 0 , 0 , 0
BC Design=,, 0 ,, 0 ,,,,,,
BC HTab HWMax=102.99
BC Use User HTab Curves=0
BC User HTab FreeFlow(D)= 0

Type RM Length L Ch R = 1 ,104061  ,502,502,502
BEGIN DESCRIPTION:
Highway S-18-16 at Indian Field - DS
END DESCRIPTION:
XS GIS Cut Line= 3
      2121443.03       523555.15      2120705.39       522627.16
      2120179.32       521579.92
#Sta/Elev= 30
  3798.4  100.95  3888.4  102.82  4088.4   99.03  4108.4   97.74  4118.4   99.08
  4318.4   97.29  4358.4   98.02  4418.4   97.63  4708.4   98.83  4768.4   98.35
  4848.4   96.21  4968.4   96.27    4990   95.56    4994   91.66    5006   91.66
    5010   95.56  5043.9   96.27  5073.9    95.6  5273.9   95.38  5403.9    97.1
  5623.9   97.14  5673.9   96.48  5693.9   97.29  5763.9   96.21  5813.9   98.09
  5913.9   98.74  5943.9   98.16  6003.9     100  6053.9   99.31  6155.8  100.52
#Mann= 3 ,-1,0
  3798.4     .11       0    4990    .045       0    5010     .11       0
#XS Ineff= 2 , 0
            4500  100.76
Permanent Ineff=
       F       F
Bank Sta=4990,5010
XS Rating Curve= 0 ,0
Exp/Cntr=0.5,0.3

Type RM Length L Ch R = 1 ,103558  ,429,429,429
BEGIN DESCRIPTION:
Indian Field Swamp 207.0
END DESCRIPTION:
XS GIS Cut Line= 3
      2121813.39       522651.94      2120885.42       522151.57
      2120171.19       521523.77
#Sta/Elev= 30
  3936.8  100.79  4166.8  100.51  4256.8  102.61  4296.8    99.8  4316.8   95.71
  4326.8   95.62  4346.8   99.26  4376.8  100.31  4436.8   97.64  4476.8    98.6
  4496.8      97  4516.8   99.46  4626.8   95.97  4766.8   97.93  4806.8   95.21
  4876.8   95.89  4986.6   93.23  4988.1   90.23  5011.9   90.23  5013.4   93.23
  5021.1   95.76  5041.1   95.98  5101.1   94.83  5421.1    96.8  5471.1   95.97
  5581.1   96.71  5591.1   97.85  5701.1   97.09  5761.1   99.37    5942  100.07
#Mann= 3 ,-1,0
  3936.8     .15       0  4986.6    .045       0  5013.4     .15       0
#XS Ineff= 2 , 0
            4529   99.29
Permanent Ineff=
       F       F
Bank Sta=4986.6,5013.4
XS Rating Curve= 0 ,0
Exp/Cntr=0.3,0.1

Type RM Length L Ch R = 1 ,103130  ,500,500,500
BEGIN DESCRIPTION:
Indian Field Swamp 206.0
END DESCRIPTION:
XS GIS Cut Line= 3
      2122150.01       522206.14      2120974.78        521729.5
      2119820.93       521223.56
#Sta/Elev= 30
  3731.8  100.06  3951.8   98.27  3981.8   95.36  4021.8   97.81  4071.8   96.52
  4271.8   98.26  4411.8   95.99  4421.8   94.71  4461.8   97.68  4471.8   96.42
  4511.8    95.2  4531.8   96.06  4601.8   95.55  4691.8   96.81  4731.8   94.89
  4981.8    94.6  4986.6   92.59  4988.1   89.59  5011.9   89.59  5013.4   92.59
    5030   95.21    5260   95.64    5650   98.89    5870   98.23    5970   99.75
    6020   99.44    6050  101.12    6090   98.43    6100   99.32  6259.9   98.51
#Mann= 3 ,-1,0
  3731.8     .15       0  4986.6    .045       0  5013.4     .15       0
#XS Ineff= 2 , 0
          4215.7   99.74  5652.3           99.74
Permanent Ineff=
       F       F
Bank Sta=4986.6,5013.4
XS Rating Curve= 0 ,0
Exp/Cntr=0.3,0.1

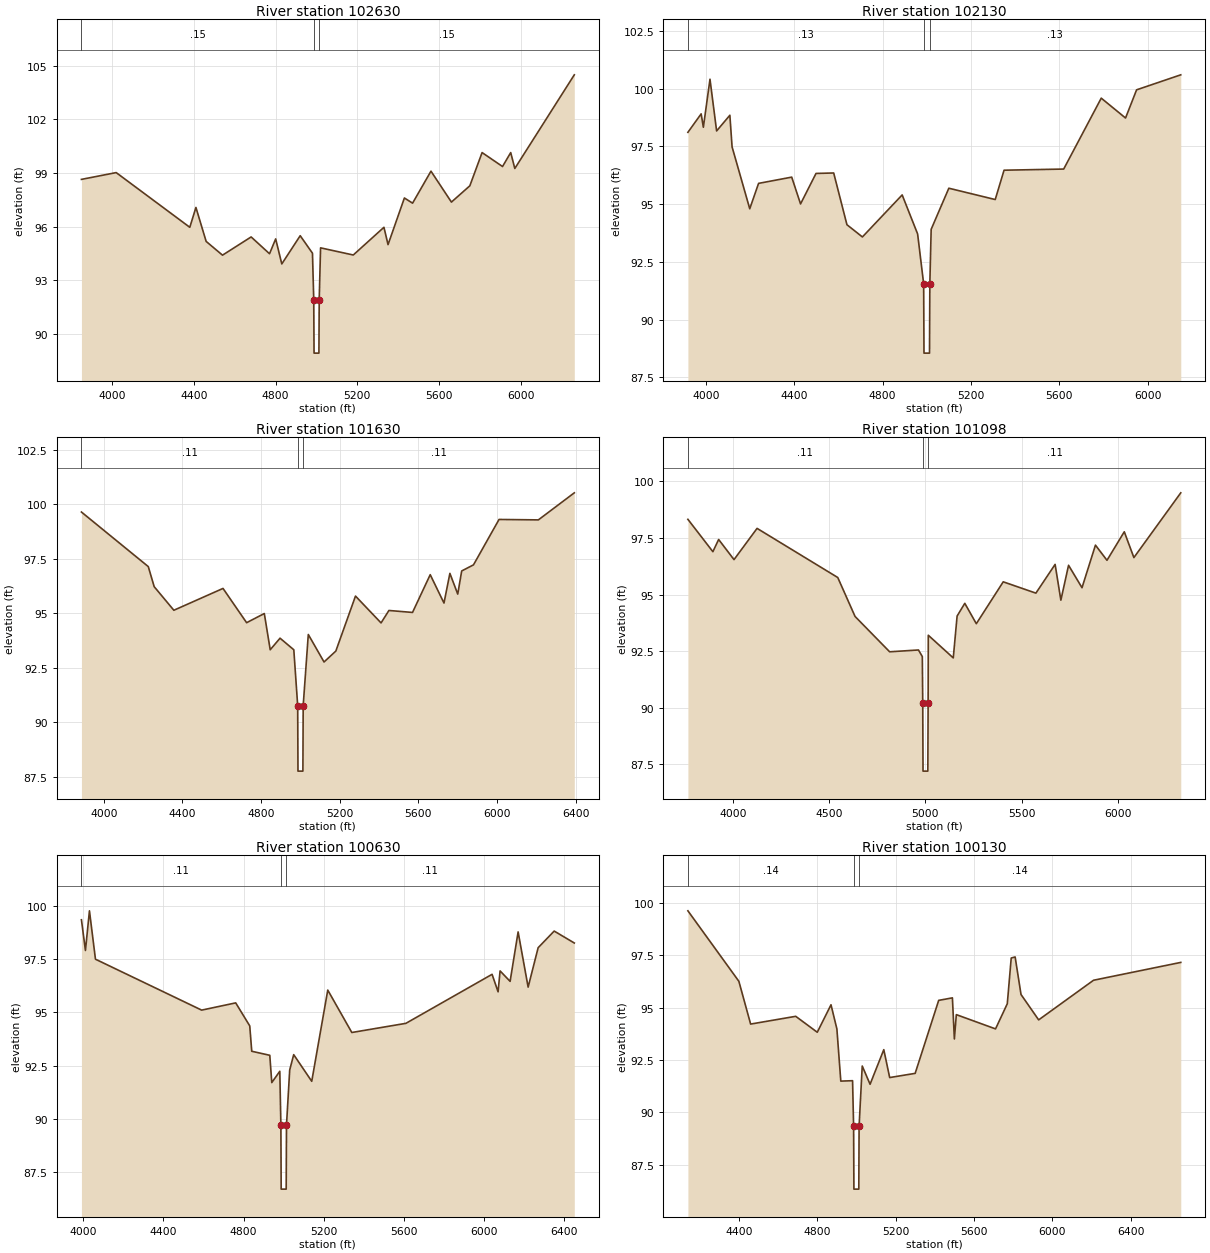
Type RM Length L Ch R = 1 ,102630  ,500,500,500
BEGIN DESCRIPTION:
Indian Field Swamp 205.0
END DESCRIPTION:
XS GIS Cut Line= 3
      2122186.47       521683.03      2121120.25        521253.2
      2120002.95        520668.6
#Sta/Elev= 30
  3850.4   98.64  4020.4   99.02  4380.4   95.96  4410.4   97.07  4460.4   95.17
  4540.4    94.4  4680.4   95.42  4770.4   94.48  4800.4   95.31  4830.4   93.91
  4920.4   95.49  4980.4   94.51  4986.6   91.92  4988.1   88.92  5011.9   88.92
  5013.4   91.92    5020   94.81    5180   94.41    5330   95.96    5350   94.99
    5430    97.6    5470   97.31    5560    99.1    5660   97.37    5750   98.28
    5810  100.14    5910   99.36    5950  100.14    5970   99.25    6261  104.49
#Mann= 3 ,-1,0
  3850.4     .15       0  4986.6    .045       0  5013.4     .15       0
Bank Sta=4986.6,5013.4
XS Rating Curve= 0 ,0
Exp/Cntr=0.3,0.1

Type RM Length L Ch R = 1 ,102130  ,500,500,500
BEGIN DESCRIPTION:
Indian Field Swamp 204.0
END DESCRIPTION:
XS GIS Cut Line= 3
      2122241.96       521480.01      2121375.98       520832.48
      2120503.94       520082.78
#Sta/Elev= 30
  3918.7   98.11  3978.7   98.91  3988.7   98.33  4018.7  100.41  4048.7   98.17
  4108.7   98.85  4118.7   97.48  4198.7    94.8  4238.7    95.9  4388.7   96.17
  4428.7   95.01  4498.7   96.33  4578.7   96.35  4638.7   94.11  4708.7   93.58
  4888.7    95.4  4958.7   93.71    4986   91.55  4987.5   88.55  5012.5   88.55
    5014   91.55    5020   93.91    5100   95.69    5310    95.2    5350   96.47
    5620   96.52    5790   99.59    5900   98.73    5950   99.95    6150   100.6
#Mann= 3 ,-1,0
  3918.7     .13       0    4986    .045       0    5014     .13       0
Bank Sta=4986,5014
XS Rating Curve= 0 ,0
Exp/Cntr=0.3,0.1

Type RM Length L Ch R = 1 ,101630  ,532,532,532
BEGIN DESCRIPTION:
Indian Field Swamp 203.0
END DESCRIPTION:
XS GIS Cut Line= 3
      2122632.03       521332.37      2121806.94       520584.34
      2120776.59       519647.32
#Sta/Elev= 30
  3886.3   99.64  4226.3   97.14  4256.3   96.22  4356.3   95.14  4606.3   96.14
  4726.3   94.57  4816.3   94.99  4846.3   93.33  4896.3   93.86  4966.3   93.33
    4986   90.77  4987.5   87.77  5012.5   87.77    5014   90.77    5040   94.03
    5120   92.77    5180   93.27    5280   95.79    5410   94.56    5450   95.13
    5570   95.04    5660   96.77    5730   95.47    5760   96.83    5800   95.88
    5820   96.94    5880   97.22    6010    99.3    6210   99.28  6392.7  100.52
#Mann= 3 ,-1,0
  3886.3     .11       0    4986    .045       0    5014     .11       0
Bank Sta=4986,5014
XS Rating Curve= 0 ,0
Exp/Cntr=0.3,0.1

Type RM Length L Ch R = 1 ,101098  ,468,468,468
BEGIN DESCRIPTION:
Indian Field Swamp 202.0
END DESCRIPTION:
XS GIS Cut Line= 3
      2123164.41       520942.36      2122158.37       520215.57
      2121083.28       519442.82
#Sta/Elev= 30
  3763.8   98.32  3893.8   96.89  3923.8   97.43  4003.8   96.54  4123.8   97.92
  4543.8   95.75  4633.8   94.03  4813.8   92.47  4963.8   92.55  4983.8   92.26
    4986    90.2  4987.5    87.2  5012.5    87.2    5014    90.2  5014.9    93.2
  5144.9    92.2  5164.9   94.05  5204.9   94.61  5264.9   93.71  5404.9   95.56
  5574.9   95.06  5674.9   96.33  5704.9   94.75  5744.9   96.29  5814.9    95.3
  5884.9   97.18  5944.9   96.51  6034.9   97.77  6084.9   96.63  6328.9   99.49
#Mann= 3 ,-1,0
  3763.8     .11       0    4986    .045       0    5014     .11       0
Bank Sta=4986,5014
XS Rating Curve= 0 ,0
Exp/Cntr=0.3,0.1

Type RM Length L Ch R = 1 ,100630  ,500,500,500
BEGIN DESCRIPTION:
Indian Field Swamp 201.0
END DESCRIPTION:
XS GIS Cut Line= 3
      2123350.55       520559.26      2122540.49       519957.01
       2121363.6       519109.32
#Sta/Elev= 30
  3990.6   99.35  4010.6   97.91  4030.6   99.77  4060.6    97.5  4590.6   95.11
  4760.6   95.45  4830.6   94.37  4840.6   93.18  4930.6   92.99  4940.6   91.71
  4980.6   92.24    4986   89.71  4987.5   86.71  5012.5   86.71    5014   89.71
    5030    92.3    5050   93.02    5140   91.77    5220   96.05    5340   94.06
    5610   94.49    6040   96.79    6070   95.97    6080   96.95    6130   96.46
    6170   98.78    6220   96.19    6270   98.04    6350   98.82  6450.4   98.26
#Mann= 3 ,-1,0
  3990.6     .11       0    4986    .045       0    5014     .11       0
Bank Sta=4986,5014
XS Rating Curve= 0 ,0
Exp/Cntr=0.3,0.1

Type RM Length L Ch R = 1 ,100130  ,500,500,500
BEGIN DESCRIPTION:
Indian Field Swamp 200.0
END DESCRIPTION:
XS GIS Cut Line= 3
      2123615.49       520219.15      2122950.91       519674.43
      2121639.24       518665.36
#Sta/Elev= 30
  4140.7   99.61  4400.7   96.25  4460.7   94.21  4690.7   94.58  4800.7   93.82
  4870.7   95.13  4900.7   93.98  4920.7   91.49  4980.7   91.51    4986   89.34
  4987.5   86.34  5012.5   86.34    5014   89.34    5030   92.21    5070   91.34
    5140   92.99    5170   91.66    5300   91.86    5420   95.34    5490   95.46
    5500    93.5    5510   94.66    5710   93.98    5770   95.18    5790   97.36
    5810   97.41    5840   95.62    5930   94.41    6210    96.3  6654.9   97.15
#Mann= 3 ,-1,0
  4140.7     .14       0    4986    .045       0    5014     .14       0
Bank Sta=4986,5014
XS Rating Curve= 0 ,0
Exp/Cntr=0.3,0.1

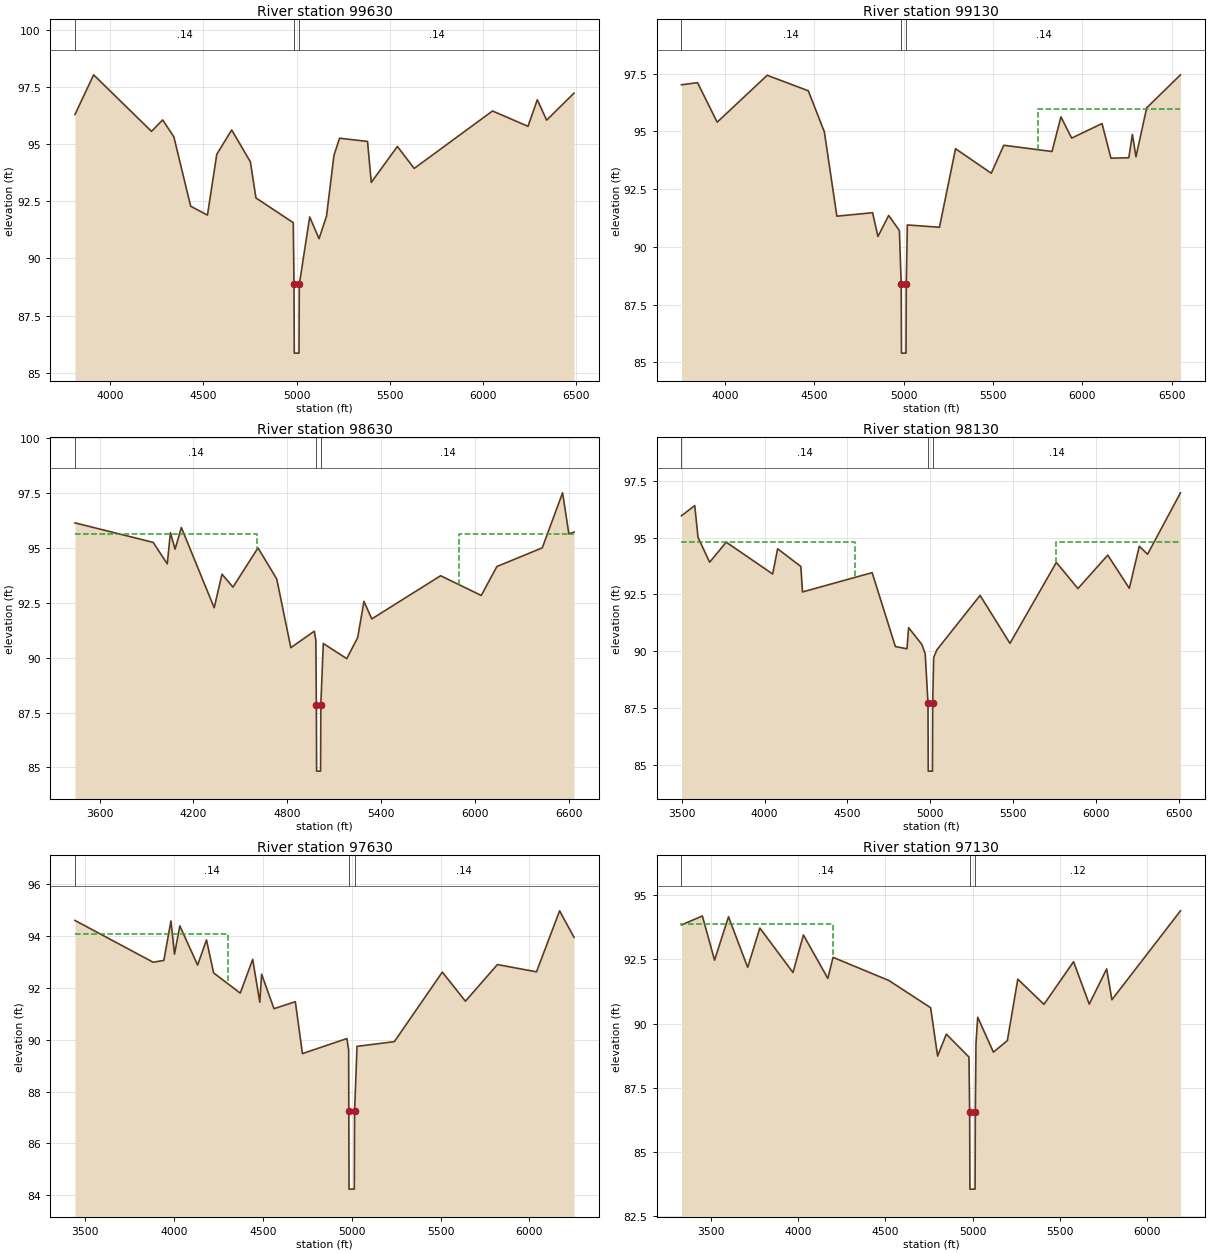
Type RM Length L Ch R = 1 ,99630   ,500,500,500
BEGIN DESCRIPTION:
Indian Field Swamp 199.0
END DESCRIPTION:
XS GIS Cut Line= 3
      2124148.94       519632.01       2123042.8       519198.38
      2121667.86       518633.13
#Sta/Elev= 30
  3811.9   96.29  3911.9   98.02  4221.9   95.55  4281.9   96.05  4341.9   95.31
  4431.9   92.28  4521.9   91.89  4571.9   94.55  4651.9   95.61  4751.9   94.22
  4781.9   92.64  4981.9   91.56  4985.8   88.86  4987.3   85.86  5012.7   85.86
  5014.2   88.86    5070   91.81    5120   90.86    5160   91.84    5200    94.5
    5230   95.25    5380   95.11    5400   93.32    5540   94.89    5630   93.93
    6050   96.44    6240   95.77    6290   96.93    6340   96.04  6486.6   97.22
#Mann= 3 ,-1,0
  3811.9     .14       0  4985.8    .045       0  5014.2     .14       0
Bank Sta=4985.8,5014.2
XS Rating Curve= 0 ,0
Exp/Cntr=0.3,0.1

Type RM Length L Ch R = 1 ,99130   ,500,500,500
BEGIN DESCRIPTION:
Indian Field Swamp 198.0
END DESCRIPTION:
XS GIS Cut Line= 3
      2124199.09       519549.69      2123215.47       518787.45
      2121936.41       517913.54
#Sta/Elev= 30
  3755.6   97.02  3845.6   97.11  3955.6    95.4  4235.6   97.43  4465.6   96.76
  4555.6   94.98  4625.6   91.33  4825.6   91.48  4855.6   90.45  4915.6   91.36
  4975.6   90.71  4985.8    88.4  4987.3    85.4  5012.7    85.4  5014.2    88.4
    5020   90.95    5200   90.85    5290   94.25    5490   93.19    5560    94.4
    5830   94.13    5880   95.63    5940   94.71    6110   95.34    6160   93.84
    6260   93.86    6280   94.87    6300    93.9    6360   96.02  6549.1   97.45
#Mann= 3 ,-1,0
  3755.6     .14       0  4985.8    .045       0  5014.2     .14       0
#XS Ineff= 2 , 0
                          5753.6           95.98
Permanent Ineff=
       F       F
Bank Sta=4985.8,5014.2
XS Rating Curve= 0 ,0
Exp/Cntr=0.3,0.1

Type RM Length L Ch R = 1 ,98630   ,500,500,500
BEGIN DESCRIPTION:
Indian Field Swamp 197.0
END DESCRIPTION:
XS GIS Cut Line= 3
      2124732.52       519338.45      2123466.98       518430.75
      2122104.68       517530.47
#Sta/Elev= 30
  3442.6   96.15  3942.6   95.26  4032.6   94.28  4052.6    95.7  4082.6   94.95
  4122.6   95.94  4332.6   92.28  4382.6   93.81  4452.6   93.22  4612.6   95.01
  4732.6   93.59  4822.6   90.46  4972.6   91.21  4982.6   90.79  4985.8   87.83
  4987.3   84.83  5012.7   84.83  5014.2   87.83    5030   90.65    5180   89.96
    5250   90.92    5290   92.57    5340   91.77    5780   93.74    6040   92.84
    6140   94.16    6430   95.01    6560   97.52    6600   95.65  6632.9   95.73
#Mann= 3 ,-1,0
  3442.6     .14       0  4985.8    .045       0  5014.2     .14       0
#XS Ineff= 2 , 0
          4605.4   95.62    5900           95.62
Permanent Ineff=
       F       F
Bank Sta=4985.8,5014.2
XS Rating Curve= 0 ,0
Exp/Cntr=0.3,0.1

Type RM Length L Ch R = 1 ,98130   ,500,500,500
BEGIN DESCRIPTION:
Indian Field Swamp 196.0
END DESCRIPTION:
XS GIS Cut Line= 3
      2124968.78       518790.66      2123692.18       518001.17
        2122409.       517208.25
#Sta/Elev= 30
    3499   95.96    3579   96.41    3599   95.01    3669   93.92    3769    94.8
    4049    93.4    4079   94.51    4219   93.73    4229   92.61    4649   93.46
    4789   90.21    4859   90.11    4869   91.04    4949    90.3    4969   89.89
  4985.8   87.73  4987.3   84.73  5012.7   84.73  5014.2   87.73    5020   89.73
    5040   90.07    5300   92.46    5480   90.35    5760   93.91    5890   92.76
    6070   94.23    6200   92.77    6260   94.62    6310   94.27  6508.4   96.97
#Mann= 3 ,-1,0
    3499     .14       0  4985.8    .045       0  5014.2     .14       0
#XS Ineff= 2 , 0
          4544.9   94.82  5759.3           94.82
Permanent Ineff=
       F       F
Bank Sta=4985.8,5014.2
XS Rating Curve= 0 ,0
Exp/Cntr=0.3,0.1

Type RM Length L Ch R = 1 ,97630   ,500,500,500
BEGIN DESCRIPTION:
Indian Field Swamp 195.0
END DESCRIPTION:
XS GIS Cut Line= 3
      2125262.39       518160.58      2123838.57       517530.24
      2122802.77       516828.73
#Sta/Elev= 30
  3442.9   94.59  3882.9   92.98  3942.9   93.05  3982.9   94.57  4002.9   93.29
  4032.9   94.38  4132.9   92.87  4182.9   93.84  4222.9   92.57  4372.9   91.79
  4442.9   93.09  4482.9   91.44  4492.9   92.52  4562.9   91.19  4682.9   91.46
  4722.9   89.46  4972.9   90.04  4982.9    89.6  4983.7   87.24  4985.2   84.24
  5014.8   84.24  5016.3   87.24    5030   89.74    5240   89.92    5510    92.6
    5640   91.48    5820   92.89    6040   92.61    6170   94.96    6251   93.94
#Mann= 3 ,-1,0
  3442.9     .14       0  4983.7    .045       0  5016.3     .14       0
#XS Ineff= 2 , 0
          4304.2   94.07
Permanent Ineff=
       F       F
Bank Sta=4983.7,5016.3
XS Rating Curve= 0 ,0
Exp/Cntr=0.3,0.1

Type RM Length L Ch R = 1 ,97130   ,500,500,500
BEGIN DESCRIPTION:
Indian Field Swamp 194.0
END DESCRIPTION:
XS GIS Cut Line= 3
      2125598.94       517713.06      2124053.59       517079.18
      2123024.73       516474.29
#Sta/Elev= 30
  3329.7   93.84  3449.7   94.19  3519.7   92.47  3599.7   94.16  3709.7   92.19
  3779.7   93.72  3969.7   91.99  4029.7   93.45  4169.7   91.76  4199.7   92.58
  4519.7   91.68  4759.7   90.62  4799.7   88.74  4849.7   89.59  4979.7    88.7
  4983.7   86.56  4985.2   83.56  5014.8   83.56  5016.3   86.56    5020   89.23
    5030   90.25    5120   88.89    5200   89.34    5260   91.73    5410   90.75
    5580   92.41    5670   90.76    5770   92.13    5800   90.93  6193.5   94.39
#Mann= 3 ,-1,0
  3329.7     .14       0  4983.7    .045       0  5016.3     .12       0
#XS Ineff= 2 , 0
            4200   93.87
Permanent Ineff=
       F       F
Bank Sta=4983.7,5016.3
XS Rating Curve= 0 ,0
Exp/Cntr=0.3,0.1