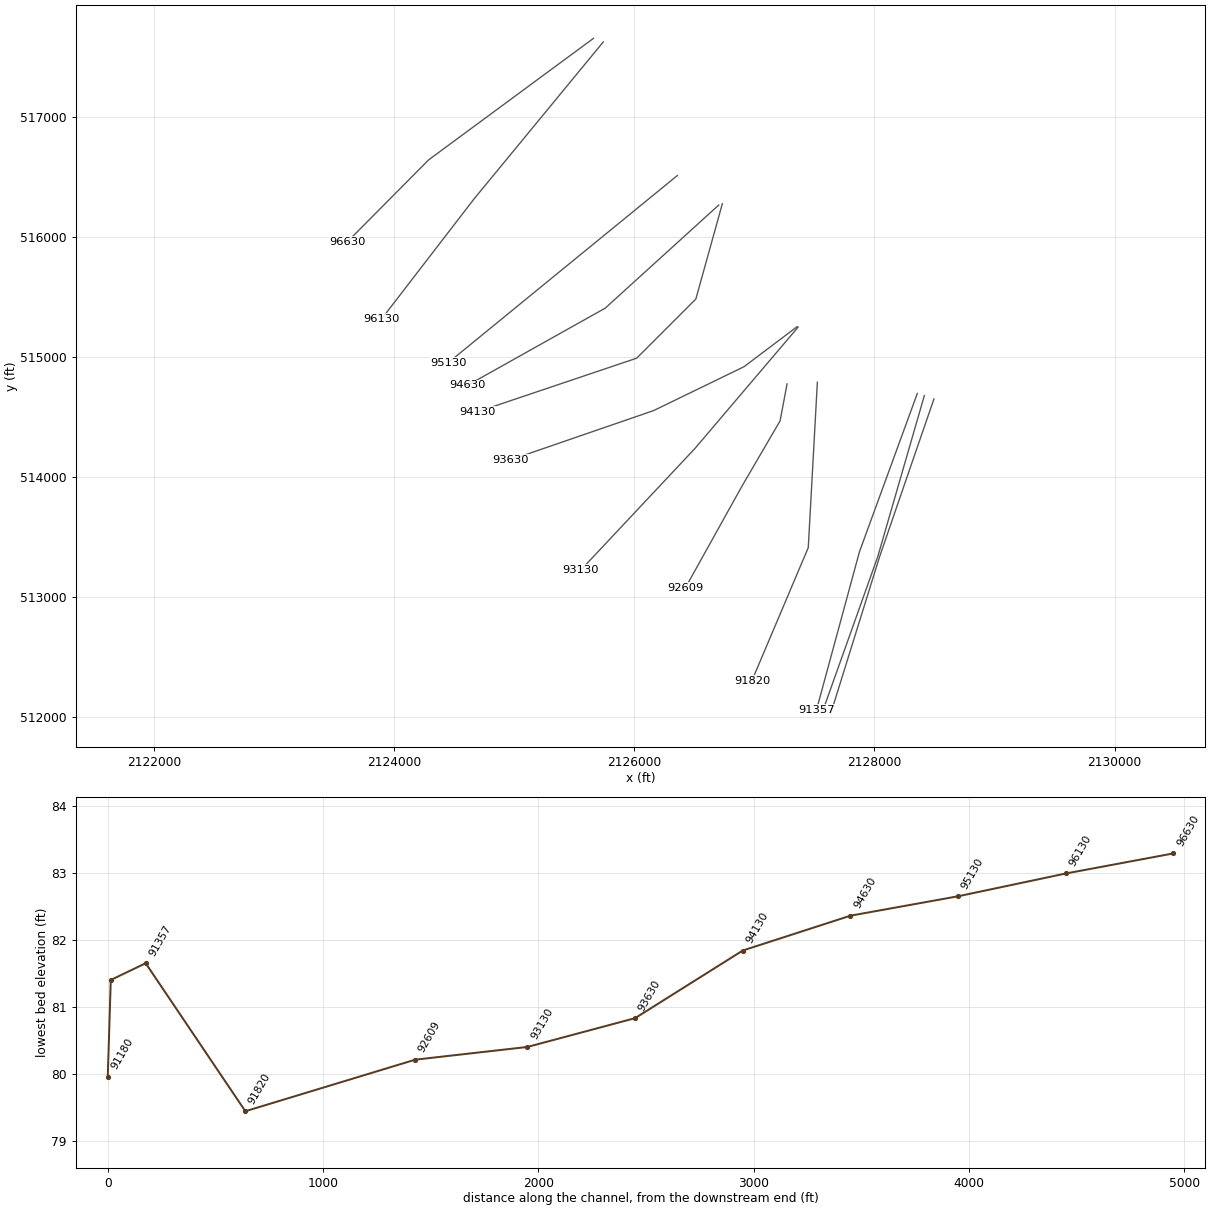
HEC-RAS study IndianFieldsSwamp.prj: S-18-19 over Indian Fields Swamp

--- IndianFieldsSwamp.g14 (geometry) --- (continued)

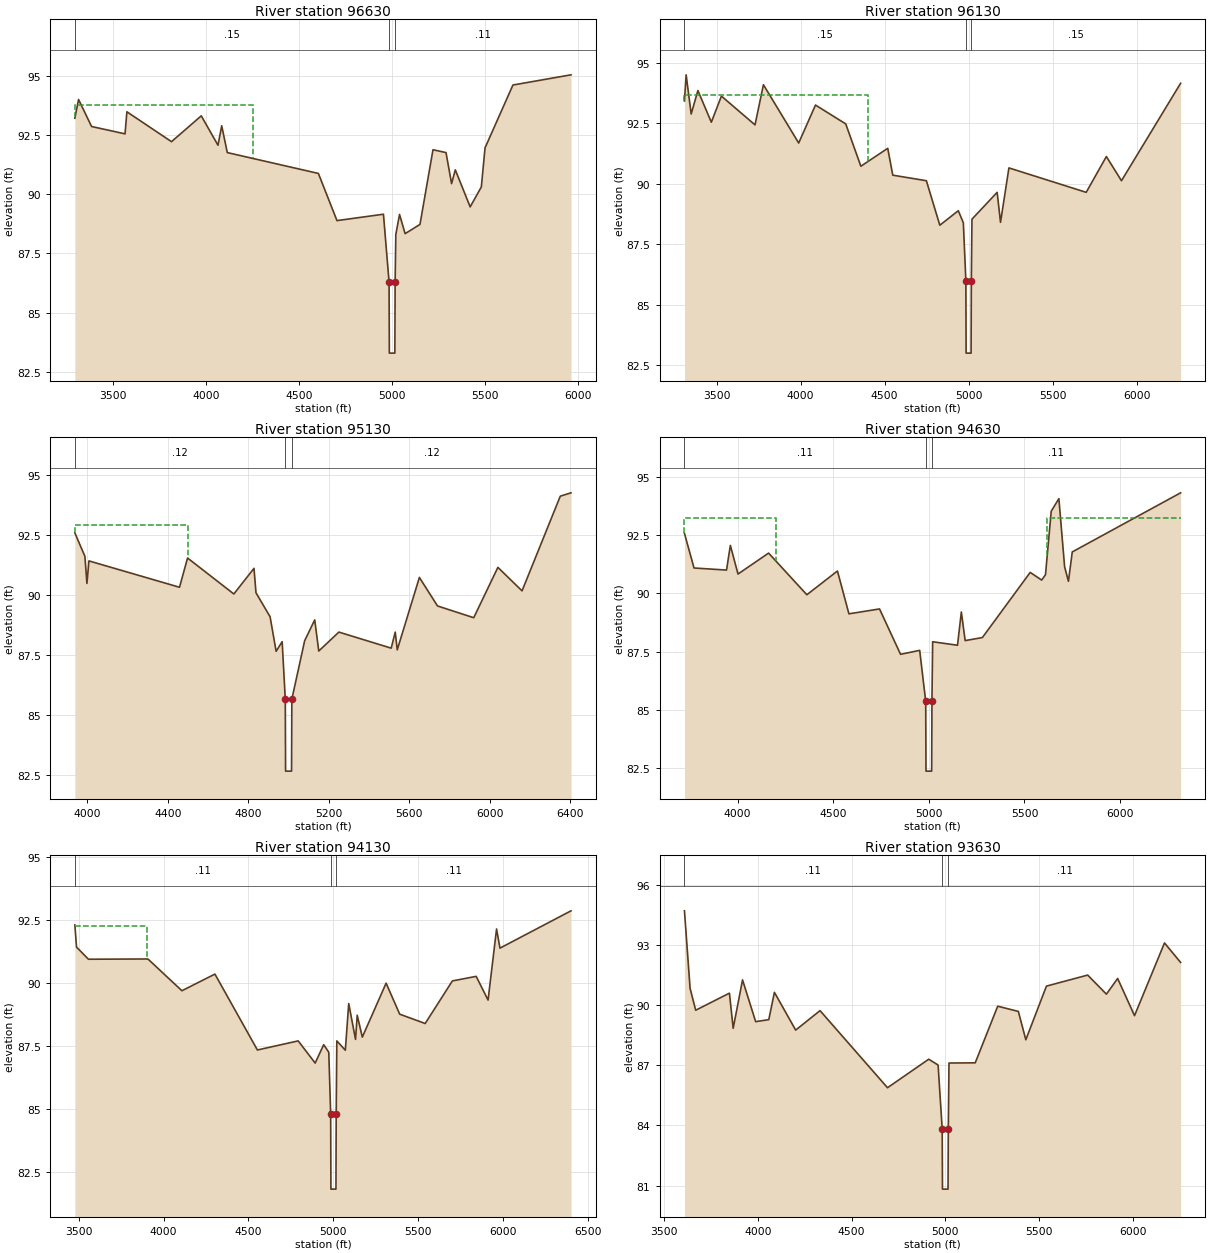
Type RM Length L Ch R = 1 ,96630   ,500,500,500
BEGIN DESCRIPTION:
Indian Field Swamp 193.0
END DESCRIPTION:
XS GIS Cut Line= 3
      2125659.76       517659.34      2124286.52       516646.25
      2123608.99       515962.89
#Sta/Elev= 30
  3293.5    93.2  3313.5   93.99  3383.5   92.85  3563.5   92.54  3573.5   93.47
  3813.5   92.21  3973.5    93.3  4063.5   92.06  4083.5   92.88  4113.5   91.75
  4603.5   90.87  4703.5   88.88  4953.5   89.15  4983.7   86.29  4985.2   83.29
  5014.8   83.29  5016.3   86.29    5020   88.29    5040   89.14    5070   88.33
    5150   88.72    5220   91.87    5290   91.75    5320   90.44    5340   91.02
    5420   89.46    5480    90.3    5500   91.95    5650    94.6  5962.3   95.03
#Mann= 3 ,-1,0
  3293.5     .15       0  4983.7    .045       0  5016.3     .11       0
#XS Ineff= 2 , 0
            4250   93.75    5763           93.75
Permanent Ineff=
       F       F
Bank Sta=4983.7,5016.3
XS Rating Curve= 0 ,0
Exp/Cntr=0.3,0.1

Type RM Length L Ch R = 1 ,96130   ,500,500,500
BEGIN DESCRIPTION:
Indian Field Swamp 192.0
END DESCRIPTION:
XS GIS Cut Line= 3
      2125740.89       517629.04      2124666.43       516322.88
      2123896.74        515322.9
#Sta/Elev= 30
  3308.7   93.42  3318.7    94.5  3348.7   92.88  3388.7   93.85  3468.7   92.54
  3528.7   93.62  3728.7   92.43  3778.7   94.09  3988.7   91.68  4088.7   93.25
  4268.7   92.47  4358.7   90.72  4518.7   91.46  4548.7   90.35  4748.7   90.12
  4828.7   88.28  4938.7   88.88  4968.7   88.38  4983.7   85.99  4985.2   82.99
  5014.8   82.99  5016.3   85.99    5020   88.53    5170   89.64    5190    88.4
    5240   90.65    5700   89.64    5820   91.12    5910   90.12  6261.9   94.15
#Mann= 3 ,-1,0
  3308.7     .15       0  4983.7    .045       0  5016.3     .15       0
#XS Ineff= 2 , 0
            4400   93.68
Permanent Ineff=
       F       F
Bank Sta=4983.7,5016.3
XS Rating Curve= 0 ,0
Exp/Cntr=0.3,0.1

Type RM Length L Ch R = 1 ,95130   ,500,500,500
BEGIN DESCRIPTION:
Indian Field Swamp 190.0
END DESCRIPTION:
XS GIS Cut Line= 3
      2126358.08       516515.73      2125535.89       515843.86
       2124449.6       514955.62
#Sta/Elev= 30
  3938.2   92.59  3988.2   91.61  3998.2   90.48  4008.2   91.42  4458.2   90.32
  4498.2   91.54  4728.2   90.04  4828.2   91.11  4838.2   90.09  4908.2   89.09
  4938.2   87.65  4968.2   88.05  4983.7   85.65  4985.2   82.65  5014.8   82.65
  5016.3   85.65    5080   88.09    5130   88.96    5150   87.66    5250   88.45
    5510   87.78    5530   88.45    5540   87.71    5650   90.73    5740   89.54
    5920   89.05    6040   91.15    6160   90.17    6350   94.12  6403.2   94.26
#Mann= 3 ,-1,0
  3938.2     .12       0  4983.7    .045       0  5016.3     .12       0
#XS Ineff= 2 , 0
          4498.4   92.93
Permanent Ineff=
       F       F
Bank Sta=4983.7,5016.3
XS Rating Curve= 0 ,0
Exp/Cntr=0.3,0.1

Type RM Length L Ch R = 1 ,94630   ,500,500,500
BEGIN DESCRIPTION:
Indian Field Swamp 189.0
END DESCRIPTION:
XS GIS Cut Line= 3
      2126702.64       516269.57      2125756.97       515410.22
      2124608.68       514766.32
#Sta/Elev= 30
  3722.2   92.58  3772.2   91.09  3942.2      91  3962.2   92.06  4002.2   90.83
  4162.2   91.73  4362.2   89.94  4522.2   90.96  4582.2   89.12  4742.2   89.33
  4852.2   87.38  4952.2   87.55  4983.7   85.36  4985.2   82.36  5014.8   82.36
  5016.3   85.36    5020   87.92    5150   87.77    5170    89.2    5190   87.97
    5280    88.1    5530    90.9    5590   90.57    5610    90.8    5640   93.53
    5680   94.07    5710   91.14    5730   90.52    5750   91.78  6316.5   94.32
#Mann= 3 ,-1,0
  3722.2     .11       0  4983.7    .045       0  5016.3     .11       0
#XS Ineff= 2 , 0
            4200   93.22    5619           93.22
Permanent Ineff=
       F       F
Bank Sta=4983.7,5016.3
XS Rating Curve= 0 ,0
Exp/Cntr=0.3,0.1

Type RM Length L Ch R = 1 ,94130   ,500,500,500
BEGIN DESCRIPTION:
Indian Field Swamp 188.0
END DESCRIPTION:
XS GIS Cut Line= 4
      2126732.97       516280.98       2126512.4        515486.7
      2126019.51       514993.38      2124694.77       514546.74
#Sta/Elev= 30
  3478.3   92.32  3488.3   91.44  3558.3   90.96  3908.3   90.97  4108.3   89.71
  4302.6   90.37  4552.6   87.36  4792.6   87.72  4892.6   86.84  4942.6   87.57
  4972.6   87.27  4983.7   84.84  4985.2   81.84  5014.8   81.84  5016.3   84.84
    5020   87.72    5070   87.35    5090    89.2    5130   87.78    5140   88.74
    5170   87.87    5310   90.01    5390   88.78    5540   88.41    5700    90.1
    5840   90.28    5910   89.34    5960   92.16    5980    91.4    6398   92.88
#Mann= 3 ,-1,0
  3478.3     .11       0  4983.7    .045       0  5016.3     .11       0
#XS Ineff= 2 , 0
          3905.4   92.29
Permanent Ineff=
       F       F
Bank Sta=4983.7,5016.3
XS Rating Curve= 0 ,0
Exp/Cntr=0.3,0.1

Type RM Length L Ch R = 1 ,93630   ,500,500,500
BEGIN DESCRIPTION:
Indian Field Swamp 187.0
END DESCRIPTION:
XS GIS Cut Line= 4
      2127355.53       515255.81      2126913.74       514922.41
       2126159.8        514556.3      2124972.39       514147.22
#Sta/Elev= 30
  3608.4   94.69  3638.4   90.83  3668.4   89.74  3848.4   90.59  3868.4   88.84
  3918.4   91.25  3988.4   89.17  4058.4   89.27  4088.4   90.63  4201.9   88.75
  4331.9   89.72  4691.9   85.88  4911.9    87.3  4961.9   87.01  4983.7   83.83
  4985.2   80.83  5014.8   80.83  5016.3   83.83    5020   87.11    5160   87.12
    5280   89.94    5390   89.68    5430   88.27    5540   90.94    5760   91.49
    5860   90.54    5920   91.32    6010   89.47    6170   93.09  6255.9   92.12
#Mann= 3 ,-1,0
  3608.4     .11       0  4983.7    .045       0  5016.3     .11       0
Bank Sta=4983.7,5016.3
XS Rating Curve= 0 ,0
Exp/Cntr=0.3,0.1

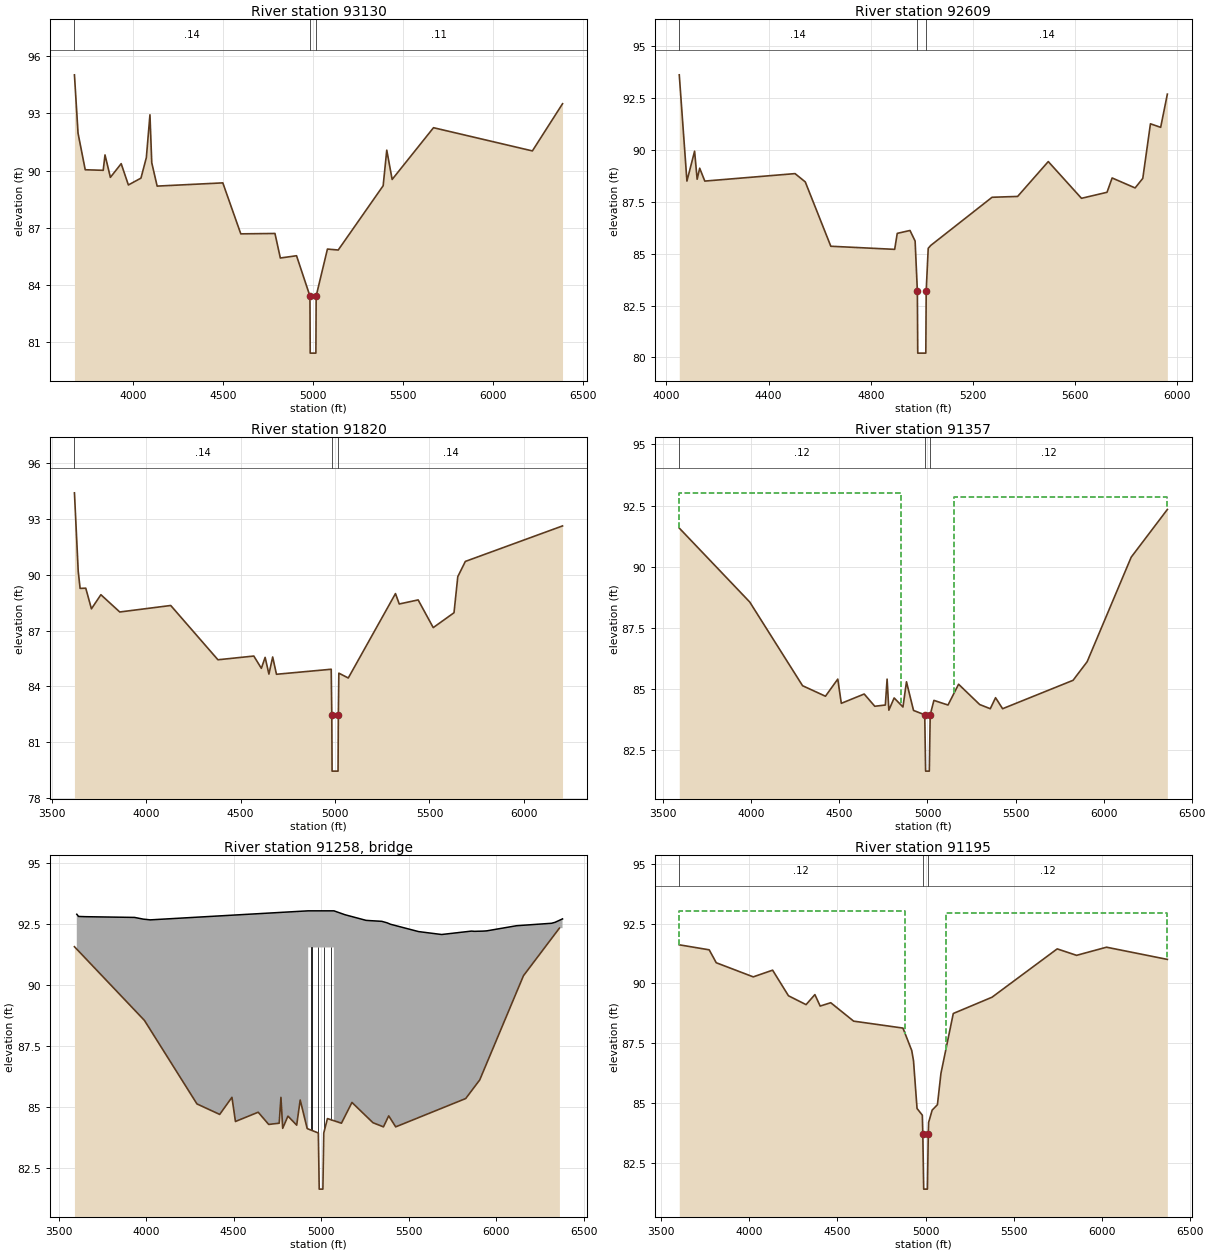
Type RM Length L Ch R = 1 ,93130   ,521,521,521
BEGIN DESCRIPTION:
Indian Field Swamp 186.0
END DESCRIPTION:
XS GIS Cut Line= 4
      2127364.24       515252.34      2126985.12       514806.44
      2126504.85       514240.95      2125555.35       513228.95
#Sta/Elev= 30
  3672.8   95.03  3692.8   91.96  3732.8   90.04  3832.8   90.01  3842.8   90.82
  3872.8   89.64  3932.8   90.36  3972.8   89.24  4042.8    89.6  4072.8   90.68
  4092.8   92.93  4102.8   90.41  4132.8   89.18  4498.1   89.35  4598.1   86.67
  4788.1   86.69  4818.1    85.4  4908.1   85.52  4982.7    83.4  4984.2    80.4
  5015.8    80.4  5017.3    83.4    5080   85.87    5140   85.82    5390    89.2
    5410   91.07    5440   89.53    5670   92.25    6220   91.03  6387.7   93.51
#Mann= 3 ,-1,0
  3672.8     .14       0  4982.7    .045       0  5017.3     .11       0
Bank Sta=4982.7,5017.3
XS Rating Curve= 0 ,0
Exp/Cntr=0.3,0.1

Type RM Length L Ch R = 1 ,92609   ,789,789,789
BEGIN DESCRIPTION:
Indian Field Swamp 185.0
END DESCRIPTION:
XS GIS Cut Line= 4
      2127271.98       514778.85      2127213.87       514470.94
      2126895.79       513925.66      2126426.25       513081.25
#Sta/Elev= 30
  4050.6   93.62  4080.6    88.5  4110.6   89.94  4120.6   88.59  4130.6   89.12
  4150.6    88.5  4503.9   88.86  4543.9   88.46  4643.9   85.36  4893.9   85.21
  4903.9   85.98  4953.9   86.12  4973.9   85.61  4982.7   83.21  4984.2   80.21
  5015.8   80.21  5017.3   83.21  5025.2   85.26  5035.2    85.4  5275.2   87.72
  5375.2   87.76  5495.2   89.44  5625.2   87.67  5725.2   87.96  5745.2   88.65
  5835.2   88.17  5865.2   88.63  5895.2   91.26  5935.2   91.09  5961.4   92.69
#Mann= 3 ,-1,0
  4050.6     .14       0  4982.7    .045       0  5017.3     .14       0
Bank Sta=4982.7,5017.3
XS Rating Curve= 0 ,0
Exp/Cntr=0.3,0.1

Type RM Length L Ch R = 1 ,91820   ,463,463,463
BEGIN DESCRIPTION:
Indian Field Swamp 184.0
END DESCRIPTION:
XS GIS Cut Line= 3
      2127524.38       514792.81      2127448.64       513414.46
      2126979.09       512304.96
#Sta/Elev= 30
  3619.6   94.41  3639.6   90.19  3649.6   89.27  3679.6   89.28  3709.6   88.17
  3759.6   88.93  3859.6      88  4129.6   88.35  4379.6   85.43  4569.6   85.63
  4609.6   84.97  4629.6   85.56  4649.6   84.66  4669.6   85.58  4689.6   84.65
  4979.6   84.92  4982.7   82.44  4984.2   79.44  5015.8   79.44  5017.3   82.44
    5020   84.71    5070   84.45    5320   88.99    5340   88.43    5440   88.65
    5520   87.16    5630   87.96    5650    89.9    5690   90.72  6204.8   92.63
#Mann= 3 ,-1,0
  3619.6     .14       0  4982.7    .045       0  5017.3     .14       0
Bank Sta=4982.7,5017.3
XS Rating Curve= 0 ,0
Exp/Cntr=0.5,0.3

Type RM Length L Ch R = 1 ,91357   ,162,162,162
BEGIN DESCRIPTION:
I-95 South at Indian Field - US
END DESCRIPTION:
XS GIS Cut Line= 3
      2128357.03       514699.91      2127874.89       513379.34
       2127517.2       512061.66
#Sta/Elev= 30
  3590.8   91.58  3990.8   88.56  4290.8   85.14  4420.8   84.71  4490.8   85.41
  4510.8   84.42  4640.8    84.8  4700.8    84.3  4760.8   84.35  4770.8   85.41
  4780.8   84.14  4810.8   84.64  4860.8   84.27  4880.8    85.3  4920.8   84.13
  4984.5   83.95  4989.5   81.65  5010.5   81.65  5015.5   83.95  5036.6   84.54
  5116.6   84.35  5176.6    85.2  5296.6   84.37  5356.6    84.2  5386.6   84.65
  5426.6    84.2  5826.6   85.36  5906.6   86.12  6156.6   90.39    6362   92.34
#Mann= 3 ,-1,0
  3590.8     .12       0  4984.5    .045       0  5015.5     .12       0
#XS Ineff= 2 , 0
            4849   93.02    5151           92.86
Permanent Ineff=
       F       F
Bank Sta=4984.5,5015.5
XS Rating Curve= 0 ,0
Exp/Cntr=0.5,0.3

Type RM Length L Ch R = 3 ,91258   ,,,
BEGIN DESCRIPTION:
I-95 South at Indian Field - TOR
Structure ID: LDS_IFS_08
Approximate Survey Structure
END DESCRIPTION:
Bridge Culvert--1,0,-1,-1, 0
Deck Dist Width WeirC Skew NumUp NumDn MinLoCord MaxHiCord MaxSubmerge Is_Ogee
77.5,43,3,0, 26, 26, , , 0.95, 0, 1,1,,
  3604.2  3614.2  3654.2  3934.2  3984.2  4024.2  4926.5  4926.5  5073.5  5073.5
  5136.9  5256.9  5276.9  5346.9  5376.9  5396.9  5556.9  5689.2  5859.2  5877.1
  5927.1  5947.1  6117.1  6317.1  6337.1  6379.9
   92.91   92.82   92.81   92.78   92.71   92.68   93.05   93.05   93.05   93.05
   92.89   92.66   92.65   92.62   92.56    92.5    92.2   92.08   92.22   92.21
   92.22   92.23   92.44   92.54   92.58   92.72
   61.65   61.65   61.65   61.65   61.65   61.65   61.65   91.55   91.55   61.65
   61.65   61.65   61.65   61.65   61.65   61.65   61.65   61.65   61.65   61.65
   61.65   61.65   61.65   61.65   61.65   61.65
  3604.2  3614.2  3654.2  3934.2  3984.2  4024.2  4926.5  4926.5  5073.5  5073.5
  5136.9  5256.9  5276.9  5346.9  5376.9  5396.9  5556.9  5689.2  5859.2  5877.1
  5927.1  5947.1  6117.1  6317.1  6337.1  6379.9
   92.91   92.82   92.81   92.78   92.71   92.68   93.05   93.05   93.05   93.05
   92.89   92.66   92.65   92.62   92.56    92.5    92.2   92.08   92.22   92.21
   92.22   92.23   92.44   92.54   92.58   92.72
   61.65   61.65   61.65   61.65   61.65   61.65   61.65   91.55   91.55   61.65
   61.65   61.65   61.65   61.65   61.65   61.65   61.65   61.65   61.65   61.65
   61.65   61.65   61.65   61.65   61.65   61.65
Pier Skew, UpSta & Num, DnSta & Num=  ,4944.9, 2 ,4944.9, 2 , 0 , 0 , 0 ,0,0
     1.5     1.5
   84.18   91.55
     1.5     1.5
   85.36   91.55
Pier Skew, UpSta & Num, DnSta & Num=  ,4981.6, 2 ,4981.6, 2 , 0 , 0 , 0 ,0,0
     1.5     1.5
   84.15   91.55
     1.5     1.5
   84.49   91.55
Pier Skew, UpSta & Num, DnSta & Num=  ,5018.4, 2 ,5018.4, 2 , 0 , 0 , 0 ,0,0
     1.5     1.5
   84.26   91.55
     1.5     1.5
   84.21   91.55
Pier Skew, UpSta & Num, DnSta & Num=  ,5055.1, 2 ,5055.1, 2 , 0 , 0 , 0 ,0,0
     1.5     1.5
   84.54   91.55
     1.5     1.5
   84.65   91.55
Abutment Skew #Up #Dn= , 2 , 2
  4926.5    4949
   91.55   84.19
  4926.5    4949
   91.55      85
Abutment Skew #Up #Dn= , 2 , 2
    5051  5073.5
   84.56   91.55
    5051  5073.5
   84.66   91.55
BR Coef=-1 ,-1 , 0 ,1.25, 0 ,,,0.8,0,2,0,
WSPro=,,,, 1 ,,,, 0 ,,,, 0 ,,,,-1 ,-1 ,-1 , 0 , 0 , 0 , 0 , 0
BC Design=,, 0 ,, 0 ,,,,,,
BC HTab HWMax=92.49
BC Use User HTab Curves=0
BC User HTab FreeFlow(D)= 0

Type RM Length L Ch R = 1 ,91195   ,14,14,14
BEGIN DESCRIPTION:
I-95 South at Indian Field - DS
END DESCRIPTION:
XS GIS Cut Line= 3
       2128415.6       514681.87        2128028.       513340.95
      2127566.56       512045.28
#Sta/Elev= 30
  3601.7   91.61  3771.7    91.4  3811.7   90.86  4021.7   90.27  4131.7   90.55
  4221.7   89.48  4321.7   89.11  4371.7   89.53  4401.7   89.05  4461.7   89.19
  4591.7   88.42  4871.7   88.13  4921.7   87.19  4931.7   86.76  4951.7   84.77
  4981.7   84.49  4984.5    83.7  4989.5    81.4  5010.5    81.4  5015.5    83.7
  5017.5   84.19  5037.5    84.7  5067.5   84.93  5087.5   86.24  5157.5   88.74
  5377.5   89.42  5747.5   91.44  5857.5   91.17  6027.5   91.51  6372.9      91
#Mann= 3 ,-1,0
  3601.7     .12       0  4984.5    .045       0  5015.5     .12       0
#XS Ineff= 2 , 0
            4885   93.03    5115           92.95
Permanent Ineff=
       F       F
Bank Sta=4984.5,5015.5
XS Rating Curve= 0 ,0
Exp/Cntr=0.5,0.3

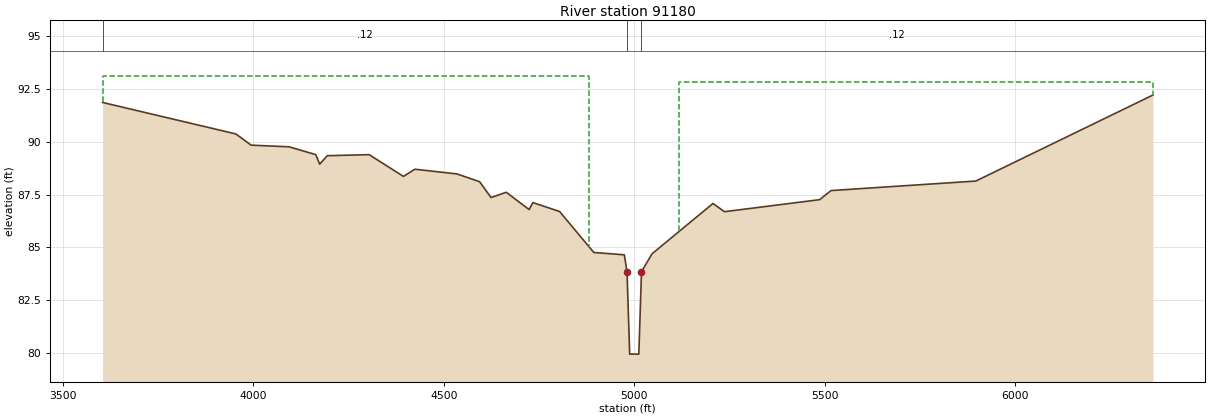
Type RM Length L Ch R = 1 ,91180   ,179,179,179
BEGIN DESCRIPTION:
I-95 North at Indian Field - US
END DESCRIPTION:
XS GIS Cut Line= 3
      2128495.22       514653.39       2128041.9       513336.32
      2127636.44       512032.93
#Sta/Elev= 30
  3603.9   91.86  3953.9   90.37  3993.9   89.84  4093.9   89.76  4163.9   89.39
  4173.9   88.94  4193.9   89.34  4303.9   89.39  4393.9   88.36  4423.9    88.7
  4533.9   88.48  4593.9   88.11  4623.9   87.36  4663.9   87.61  4723.9   86.79
  4733.9   87.12  4803.9    86.7  4893.9   84.76  4973.9   84.65    4981   83.85
    4988   79.95    5012   79.95    5019   83.85  5046.8    84.7  5206.8   87.08
  5236.8   86.69  5486.8   87.26  5516.8   87.69  5896.8   88.14  6361.8   92.21
#Mann= 3 ,-1,0
  3603.9     .12       0    4981    .045       0    5019     .12       0
#XS Ineff= 2 , 0
            4882   93.12    5118           92.83
Permanent Ineff=
       F       F
Bank Sta=4981,5019
XS Rating Curve= 0 ,0
Exp/Cntr=0.5,0.3