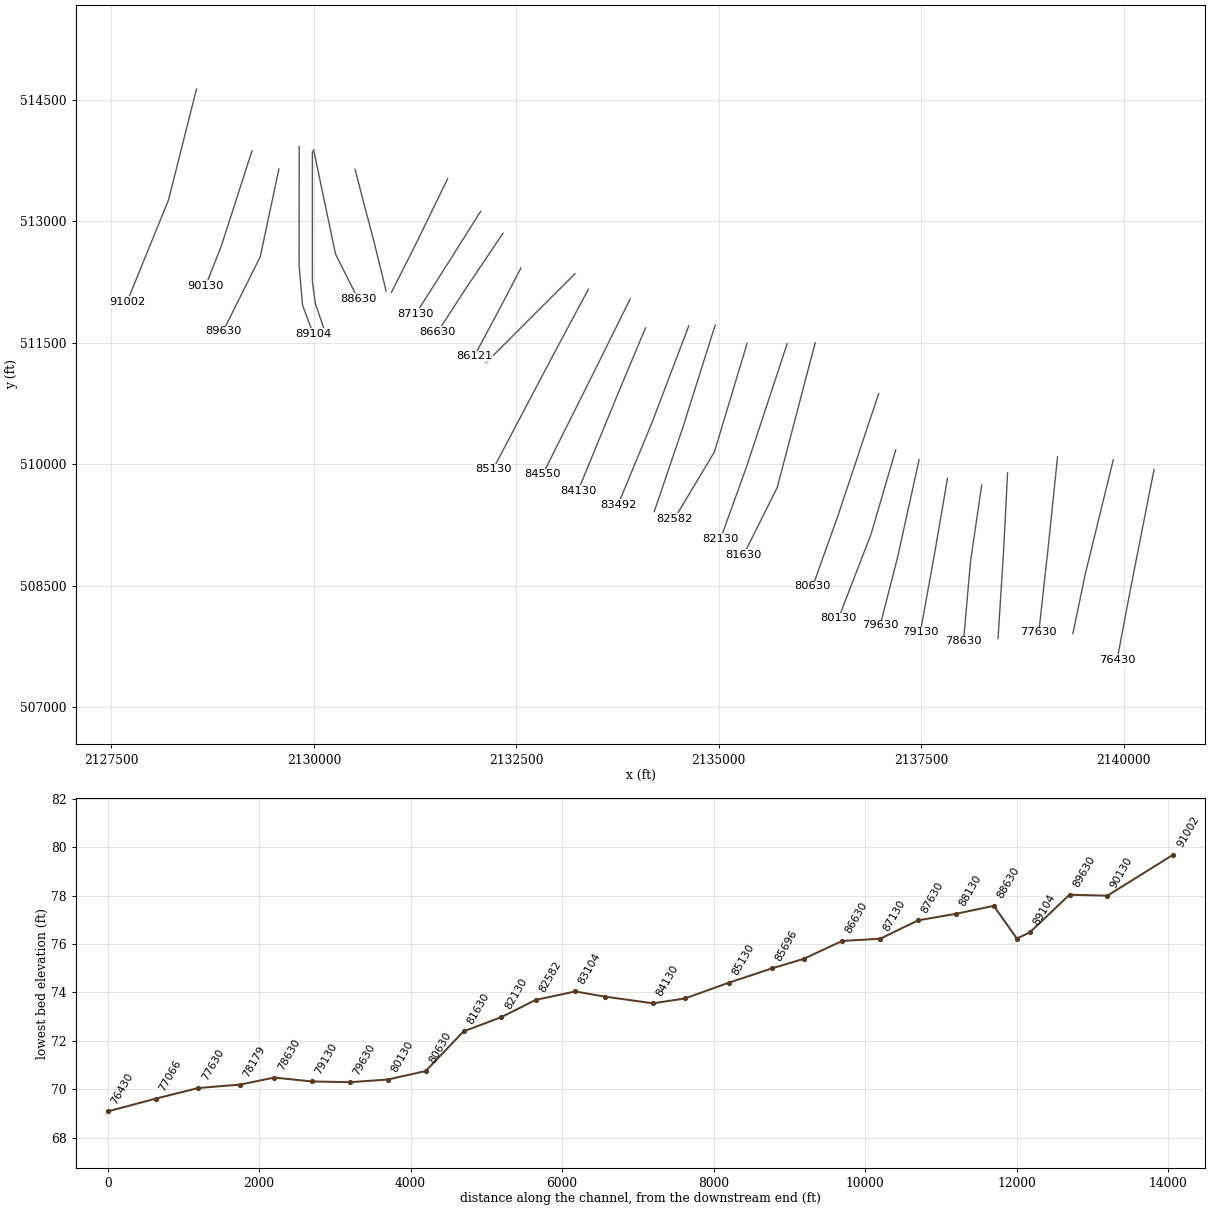
HEC-RAS study IndianFieldsSwamp.prj: S-18-19 over Indian Fields Swamp

--- IndianFieldsSwamp.g14 (geometry) --- (continued)

Type RM Length L Ch R = 3 ,91114   ,,,
BEGIN DESCRIPTION:
I-95 North at Indian Field - TOR
Structure ID: LDS_IFS_07
Approximate Survey Structure
END DESCRIPTION:
Bridge Culvert--1,0,-1,-1, 0
Deck Dist Width WeirC Skew NumUp NumDn MinLoCord MaxHiCord MaxSubmerge Is_Ogee
44.5,43,3,0, 13, 13, , , 0.95, 0, 1,1,,
  3593.6  4293.6  4313.6  4926.5  4926.5  5073.5  5073.5  5128.8  5378.8  5451.9
  5897.9  6367.9  6369.7
    92.9   92.73   92.77   93.15   93.15   93.15   93.15   92.91   93.01   92.93
   92.87   93.37   93.34
   59.95   59.95   59.95   59.95   91.65   91.65   59.95   59.95   59.95   59.95
   59.95   59.95   59.95
  3593.6  4293.6  4313.6  4926.5  4926.5  5073.5  5073.5  5128.8  5378.8  5451.9
  5897.9  6367.9  6369.7
    92.9   92.73   92.77   93.15   93.15   93.15   93.15   92.91   93.01   92.93
   92.87   93.37   93.34
   59.95   59.95   59.95   59.95   91.65   91.65   59.95   59.95   59.95   59.95
   59.95   59.95   59.95
Pier Skew, UpSta & Num, DnSta & Num=  ,4944.9, 2 ,4944.9, 2 , 0 , 0 , 0 ,0,0
     1.5     1.5
   84.72   91.65
     1.5     1.5
   84.86   91.65
Pier Skew, UpSta & Num, DnSta & Num=  ,4981.6, 2 ,4981.6, 2 , 0 , 0 , 0 ,0,0
     1.5     1.5
   83.52   91.65
     1.5     1.5
   83.27   91.65
Pier Skew, UpSta & Num, DnSta & Num=  ,5018.4, 2 ,5018.4, 2 , 0 , 0 , 0 ,0,0
     1.5     1.5
   83.52   91.65
     1.5     1.5
   83.27   91.65
Pier Skew, UpSta & Num, DnSta & Num=  ,5055.1, 2 ,5055.1, 2 , 0 , 0 , 0 ,0,0
     1.5     1.5
   84.67   91.65
     1.5     1.5
   84.68   91.65
Abutment Skew #Up #Dn= , 2 , 2
  4926.5    4949
   91.65   84.71
  4926.5    4949
   91.65   84.85
Abutment Skew #Up #Dn= , 2 , 2
    5051  5073.5
   84.68   91.65
    5051  5073.5
   84.76   91.65
BR Coef=-1 ,-1 , 0 ,1.25, 0 ,,,0.8,0,2,0,
WSPro=,,,, 1 ,,,, 0 ,,,, 0 ,,,,-1 ,-1 ,-1 , 0 , 0 , 0 , 0 , 0
BC Design=,, 0 ,, 0 ,,,,,,
BC HTab HWMax=92.21
BC Use User HTab Curves=0
BC User HTab FreeFlow(D)= 0

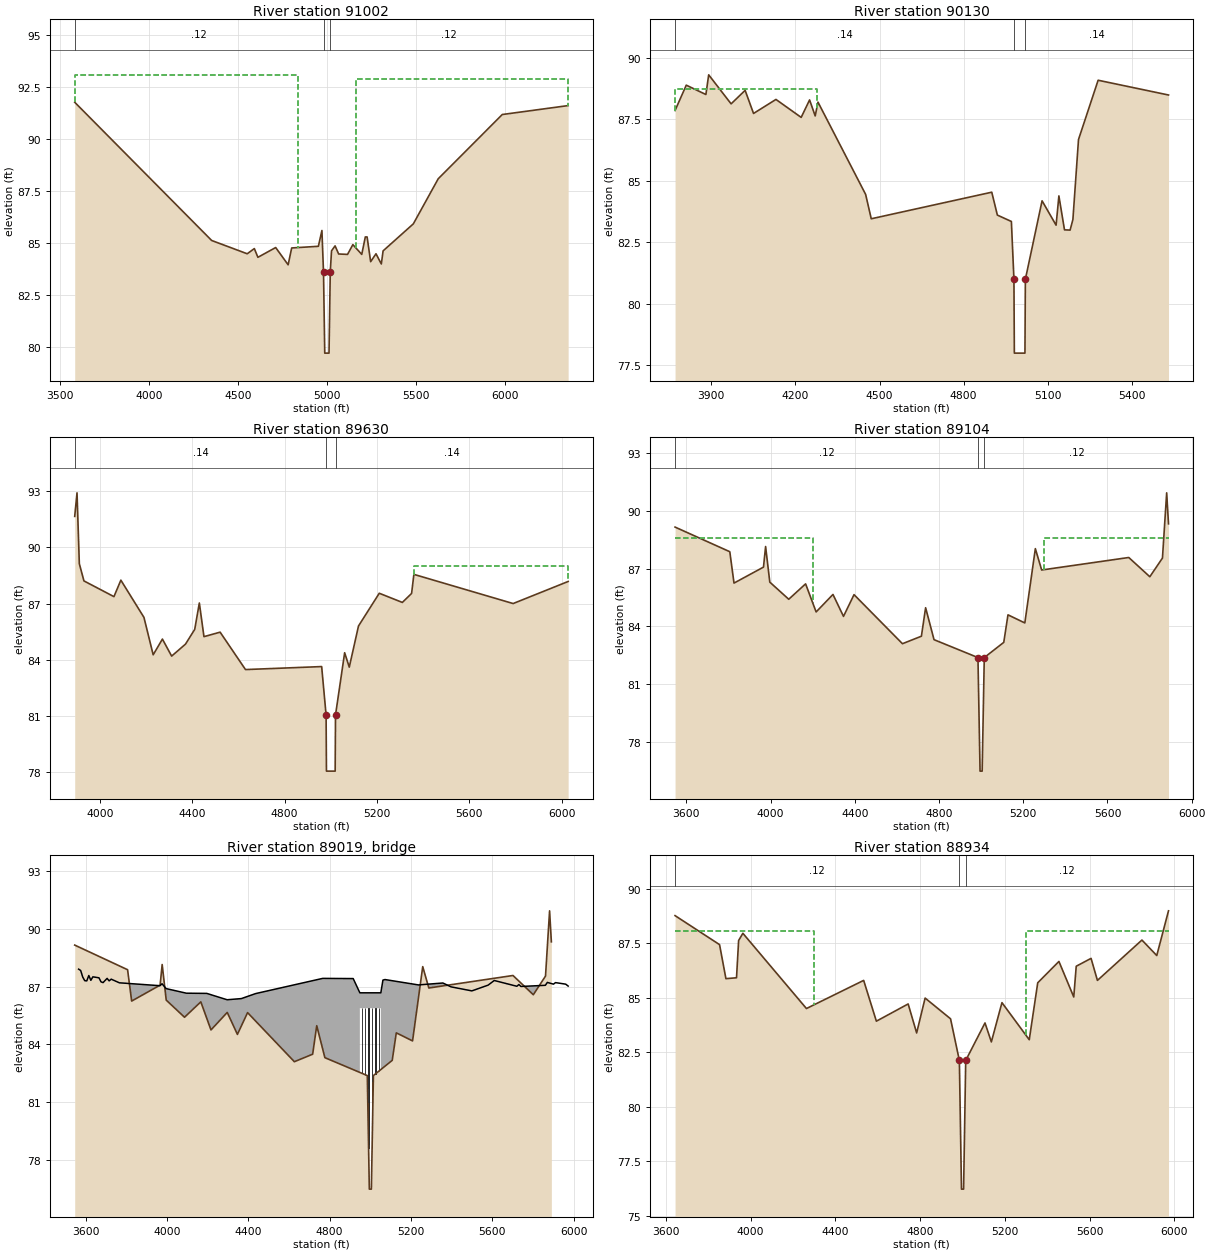
Type RM Length L Ch R = 1 ,91002   ,872,872,872
BEGIN DESCRIPTION:
I-95 North at Indian Field - DS
END DESCRIPTION:
XS GIS Cut Line= 3
      2128550.35       514635.49      2128204.09       513264.49
      2127691.94       512004.13
#Sta/Elev= 30
  3582.1   91.77  4352.1   85.12  4552.1   84.48  4592.1   84.73  4612.1   84.31
  4712.1   84.78  4782.1   83.95  4802.1   84.76  4952.1   84.84  4972.1    85.6
    4981    83.6    4988    79.7    5012    79.7    5019    83.6  5026.1   84.62
  5046.1   84.86  5066.1   84.47  5116.1   84.45  5146.1   84.92  5196.1   84.45
  5216.1   85.29  5226.1   85.29  5246.1    84.1  5276.1   84.48  5306.1   83.99
  5316.1   84.62  5486.1   85.92  5626.1   88.09  5986.1   91.18  6356.6   91.61
#Mann= 3 ,-1,0
  3582.1     .12       0    4981    .045       0    5019     .12       0
#XS Ineff= 2 , 0
            4835   93.09    5165           92.91
Permanent Ineff=
       F       F
Bank Sta=4981,5019
XS Rating Curve= 0 ,0
Exp/Cntr=0.5,0.3

Type RM Length L Ch R = 1 ,90130   ,500,500,500
BEGIN DESCRIPTION:
Indian Field Swamp 180.0
END DESCRIPTION:
XS GIS Cut Line= 3
      2129235.31       513871.49      2128858.43       512701.18
       2128663.6       512207.11
#Sta/Elev= 30
  3770.5   87.86  3810.5   88.89  3880.5   88.51  3890.5   89.31  3970.5   88.13
  4020.5   88.68  4050.5   87.74  4130.5   88.31  4220.5   87.58  4250.5   88.29
  4270.5   87.64  4280.5    88.2  4450.5   84.45  4470.5   83.46  4900.5   84.54
  4920.5   83.61  4970.5   83.35  4979.6      81  4981.1      78  5018.9      78
  5020.4      81    5080   84.19    5130    83.2    5140   84.39    5160   83.01
    5180      83    5190   83.43    5210   86.68    5280   89.09  5531.1   88.49
#Mann= 3 ,-1,0
  3770.5     .14       0  4979.6    .045       0  5020.4     .14       0
#XS Ineff= 2 , 0
          4275.9   88.74
Permanent Ineff=
       F       F
Bank Sta=4979.6,5020.4
XS Rating Curve= 0 ,0
Exp/Cntr=0.3,0.1

Type RM Length L Ch R = 1 ,89630   ,525,525,525
BEGIN DESCRIPTION:
Indian Field Swamp 179.0
END DESCRIPTION:
XS GIS Cut Line= 3
      2129567.79       513646.27      2129336.85       512560.97
      2128877.51       511640.86
#Sta/Elev= 30
  3890.4   91.66  3900.4   92.92  3910.4   89.13  3930.4   88.21  4060.4   87.37
  4090.4   88.25  4190.4   86.26  4230.4   84.26  4270.4    85.1  4310.4   84.19
  4370.4   84.83  4410.4   85.62  4430.4   87.03  4450.4   85.23  4520.4   85.47
  4630.4   83.47  4960.4   83.63  4979.6   81.04  4981.1   78.04  5018.9   78.04
  5020.4   81.04    5060   84.37    5080    83.6    5120    85.8    5210   87.55
    5310   87.06    5350   87.54    5360   88.56    5790      87  6028.4   88.18
#Mann= 3 ,-1,0
  3890.4     .14       0  4979.6    .045       0  5020.4     .14       0
#XS Ineff= 2 , 0
                            5362           88.99
Permanent Ineff=
       F       F
Bank Sta=4979.6,5020.4
XS Rating Curve= 0 ,0
Exp/Cntr=0.5,0.3

Type RM Length L Ch R = 1 ,89104   ,171,171,171
BEGIN DESCRIPTION:
Mullberry Road at Indian Fields - US
END DESCRIPTION:
XS GIS Cut Line= 4
      2129818.62       513926.35      2129816.66       512465.16
      2129859.98       511963.32      2129991.91       511608.34
#Sta/Elev= 30
  3546.4   89.16  3806.4   87.88  3826.4   86.25  3966.4   87.08  3976.4   88.15
  3996.4    86.3  4086.4   85.41  4166.4   86.21  4216.4   84.75  4296.4   85.66
  4346.4   84.52  4396.4   85.65  4626.4    83.1  4716.4   83.49  4736.4   84.97
  4776.4   83.31    4985   82.38    4995   76.48    5005   76.48    5015   82.38
  5107.6   83.17  5127.6    84.6  5207.6   84.18  5257.6   88.04  5287.6   86.93
  5701.3   87.58  5801.3   86.58  5861.3   87.55  5881.3   90.94    5890   89.33
#Mann= 3 ,-1,0
  3546.4     .12       0    4985    .045       0    5015     .12       0
#XS Ineff= 2 , 0
            4200   88.57    5300           88.57
Permanent Ineff=
       F       F
Bank Sta=4985,5015
XS Rating Curve= 0 ,0
Exp/Cntr=0.5,0.3

Type RM Length L Ch R = 3 ,89019   ,,,
BEGIN DESCRIPTION:
Mullberry Road at Indian Fields - TOR
Structure ID: LDS_IFS_06
Approximate Survey Structure
END DESCRIPTION:
Bridge Culvert--1,0,-1,-1, 0
Deck Dist Width WeirC Skew NumUp NumDn MinLoCord MaxHiCord MaxSubmerge Is_Ogee
70.5,29,3,0, 46, 46, , , 0.95, 0, 1,1,,
  3565.7  3575.7  3585.7  3595.7  3605.7  3615.7  3625.7  3635.7  3665.7  3675.7
  3685.7  3705.7  3715.7  3725.7  3765.7  3965.7  3975.7  3995.7  4095.7  4195.7
  4295.7  4365.7  4435.7  4765.7  4915.7  4948.5  4948.5  5051.5  5051.5  5061.8
  5071.8  5236.6  5356.6  5396.6  5499.2  5579.2  5609.2  5720.4  5730.4  5740.4
  5860.4  5870.4  5900.4  5910.4  5960.4  5972.6
   87.91   87.84    87.5   87.31    87.3   87.58   87.33   87.51   87.46   87.25
   87.21   87.43    87.3   87.39    87.2   87.05   87.15    86.9   86.66   86.65
   86.32   86.38   86.64   87.43   87.42   86.68   86.68   86.68   86.68   87.34
   87.37   87.09   87.19   86.99   86.78   87.08   87.32   87.02   87.11   87.01
   87.07   87.22   87.13   87.21   87.13   87.03
   56.48   56.48   56.48   56.48   56.48   56.48   56.48   56.48   56.48   56.48
   56.48   56.48   56.48   56.48   56.48   56.48   56.48   56.48   56.48   56.48
   56.48   56.48   56.48   56.48   56.48   56.48   85.88   85.88   56.48   56.48
   56.48   56.48   56.48   56.48   56.48   56.48   56.48   56.48   56.48   56.48
   56.48   56.48   56.48   56.48   56.48   56.48
  3565.7  3575.7  3585.7  3595.7  3605.7  3615.7  3625.7  3635.7  3665.7  3675.7
  3685.7  3705.7  3715.7  3725.7  3765.7  3965.7  3975.7  3995.7  4095.7  4195.7
  4295.7  4365.7  4435.7  4765.7  4915.7  4948.5  4948.5  5051.5  5051.5  5061.8
  5071.8  5236.6  5356.6  5396.6  5499.2  5579.2  5609.2  5720.4  5730.4  5740.4
  5860.4  5870.4  5900.4  5910.4  5960.4  5972.6
   87.91   87.84    87.5   87.31    87.3   87.58   87.33   87.51   87.46   87.25
   87.21   87.43    87.3   87.39    87.2   87.05   87.15    86.9   86.66   86.65
   86.32   86.38   86.64   87.43   87.42   86.68   86.68   86.68   86.68   87.34
   87.37   87.09   87.19   86.99   86.78   87.08   87.32   87.02   87.11   87.01
   87.07   87.22   87.13   87.21   87.13   87.03
   56.48   56.48   56.48   56.48   56.48   56.48   56.48   56.48   56.48   56.48
   56.48   56.48   56.48   56.48   56.48   56.48   56.48   56.48   56.48   56.48
   56.48   56.48   56.48   56.48   56.48   56.48   85.88   85.88   56.48   56.48
   56.48   56.48   56.48   56.48   56.48   56.48   56.48   56.48   56.48   56.48
   56.48   56.48   56.48   56.48   56.48   56.48
Pier Skew, UpSta & Num, DnSta & Num=  ,4957.1, 2 ,4957.1, 2 , 0 , 0 , 0 ,0,0
     1.1     1.1
   83.07   85.88
     1.1     1.1
   83.79   85.88
Pier Skew, UpSta & Num, DnSta & Num=  ,4974.3, 2 ,4974.3, 2 , 0 , 0 , 0 ,0,0
     1.1     1.1
   82.65   85.88
     1.1     1.1
   82.89   85.88
Pier Skew, UpSta & Num, DnSta & Num=  ,4991.4, 2 ,4991.4, 2 , 0 , 0 , 0 ,0,0
     1.1     1.1
    78.6   85.88
     1.1     1.1
   78.35   85.88
Pier Skew, UpSta & Num, DnSta & Num=  ,5008.6, 2 ,5008.6, 2 , 0 , 0 , 0 ,0,0
     1.1     1.1
    78.6   85.88
     1.1     1.1
   78.35   85.88
Pier Skew, UpSta & Num, DnSta & Num=  ,5025.8, 2 ,5025.8, 2 , 0 , 0 , 0 ,0,0
     1.1     1.1
   82.47   85.88
     1.1     1.1
   82.36   85.88
Pier Skew, UpSta & Num, DnSta & Num=  ,5042.9, 2 ,5042.9, 2 , 0 , 0 , 0 ,0,0
     1.1     1.1
   82.62   85.88
     1.1     1.1
   82.72   85.88
Abutment Skew #Up #Dn= , 2 , 2
  4948.5    4957
   85.88   83.08
  4948.5    4957
   85.88   83.79
Abutment Skew #Up #Dn= , 2 , 2
    5043  5051.5
   82.62   85.88
    5043  5051.5
   82.72   85.88
BR Coef=-1 ,-1 , 0 ,1.25, 0 ,,,0.8,0,2,0,
WSPro=,,,, 1 ,,,, 0 ,,,, 0 ,,,,-1 ,-1 ,-1 , 0 , 0 , 0 , 0 , 0
BC Design=,, 0 ,, 0 ,,,,,,
BC HTab HWMax=90.94
BC Use User HTab Curves=0
BC User HTab FreeFlow(D)= 0

Type RM Length L Ch R = 1 ,88934   ,304,304,304
BEGIN DESCRIPTION:
Mullberry Road at Indian Fields - DS
END DESCRIPTION:
XS GIS Cut Line= 5
      2129981.44       513864.07      2129981.16       512511.49
      2129981.45       512252.68      2130017.77        511983.4
      2130162.47       511562.17
#Sta/Elev= 30
  3643.4   88.77  3853.4   87.44  3883.4   85.88  3933.4   85.92  3943.4   87.63
  3963.4   87.96  4263.4   84.51  4533.4    85.8  4593.4   83.93  4743.4   84.72
  4783.4   83.39  4823.4   84.99  4943.4   84.04    4985   82.13    4995   76.23
    5005   76.23    5015   82.13    5106   83.85    5136   82.98    5186   84.78
  5314.8   83.08  5354.8   85.69  5454.8   86.67  5524.8   85.04  5536.5   86.45
  5606.5   86.81  5636.5    85.8  5846.5   87.65  5916.5   86.94  5971.9   88.99
#Mann= 3 ,-1,0
  3643.4     .12       0    4985    .045       0    5015     .12       0
#XS Ineff= 2 , 0
            4300   88.06    5300           88.06
Permanent Ineff=
       F       F
Bank Sta=4985,5015
XS Rating Curve= 0 ,0
Exp/Cntr=0.5,0.3

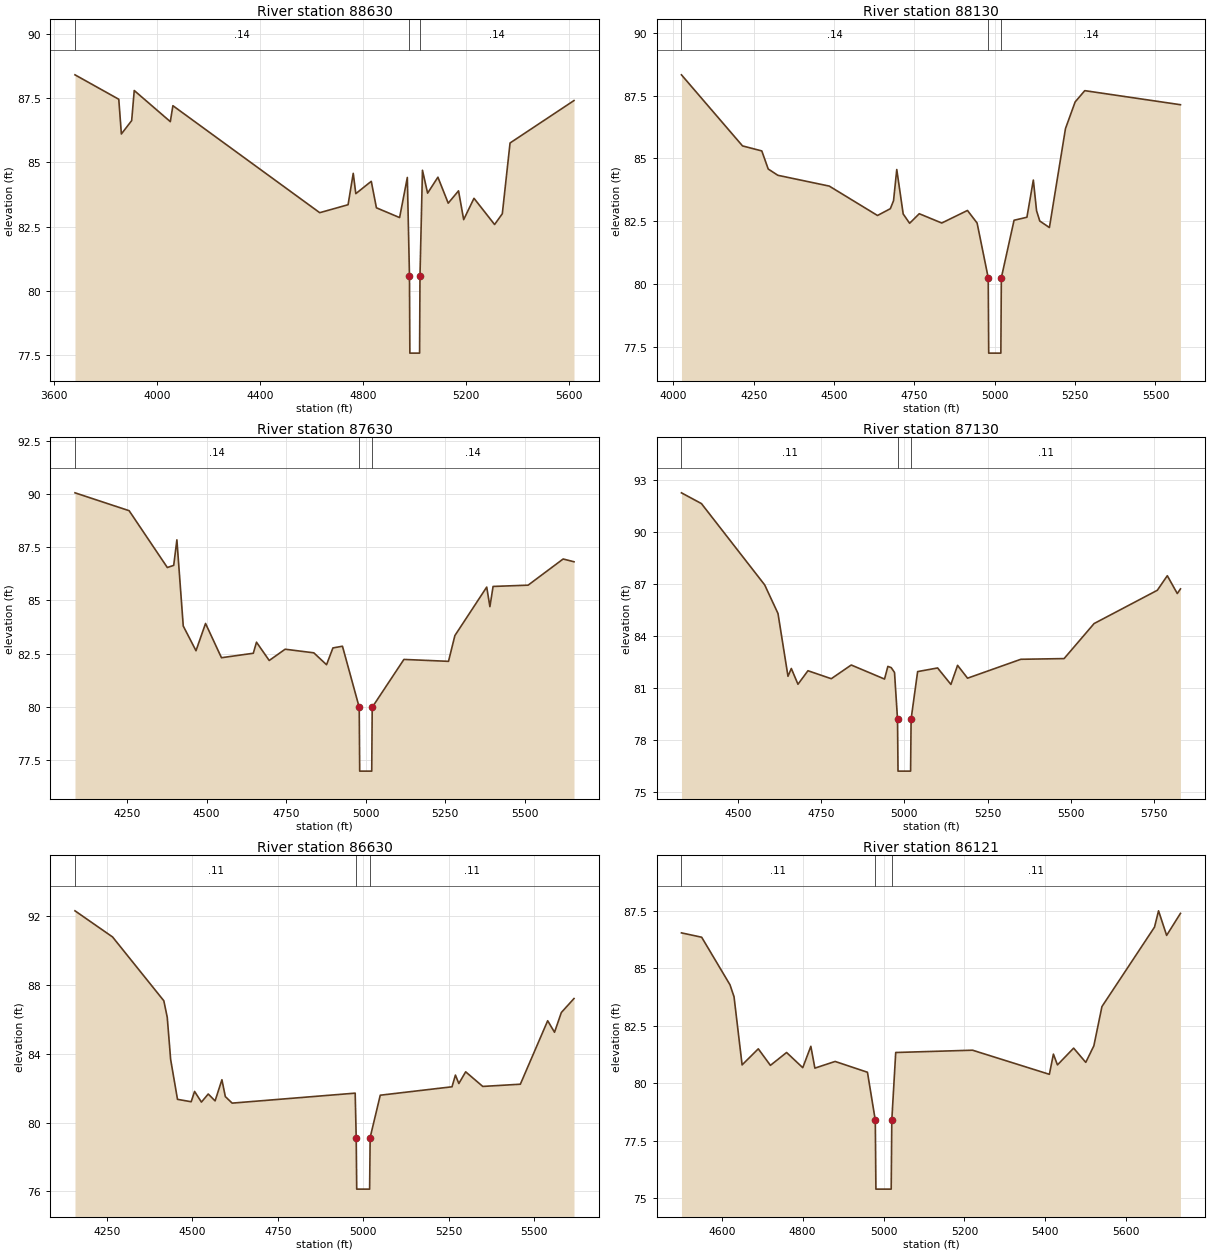
Type RM Length L Ch R = 1 ,88630   ,500,500,500
BEGIN DESCRIPTION:
Indian Field Swamp 177.0
END DESCRIPTION:
XS GIS Cut Line= 3
      2129996.28        513885.4      2130267.44       512594.88
      2130544.81       512042.39
#Sta/Elev= 30
  3681.3    88.4  3851.3   87.45  3861.3    86.1  3901.3   86.62  3911.3   87.79
  4051.3   86.58  4061.3    87.2  4631.3   83.04  4741.3   83.35  4761.3   84.57
  4771.3   83.78  4831.3   84.26  4851.3   83.23  4941.3   82.85  4971.3   84.41
  4979.6   80.58  4981.1   77.58  5018.9   77.58  5020.4   80.58    5030   84.69
    5050    83.8    5090   84.42    5130   83.41    5170   83.89    5190   82.77
    5230    83.6    5310   82.58    5340      83    5370   85.75  5618.2    87.4
#Mann= 3 ,-1,0
  3681.3     .14       0  4979.6    .045       0  5020.4     .14       0
Bank Sta=4979.6,5020.4
XS Rating Curve= 0 ,0
Exp/Cntr=0.3,0.1

Type RM Length L Ch R = 1 ,88130   ,500,500,500
BEGIN DESCRIPTION:
Indian Field Swamp 176.0
END DESCRIPTION:
XS GIS Cut Line= 3
      2130507.86       513642.86       2130754.5       512699.57
      2130892.15       512138.41
#Sta/Elev= 30
    4025   88.33    4215    85.5    4275    85.3    4295   84.58    4325   84.33
    4485    83.9    4635   82.73    4675      83    4685   83.32    4695   84.56
    4715   82.79    4735   82.42    4765    82.8    4835   82.43    4915   82.93
    4945   82.43  4979.6   80.25  4981.1   77.25  5018.9   77.25  5020.4   80.25
    5060   82.54    5100   82.66    5120   84.14    5130   82.92    5140   82.51
    5170   82.25    5220   86.19    5250   87.25    5280    87.7  5577.8   87.14
#Mann= 3 ,-1,0
    4025     .14       0  4979.6    .045       0  5020.4     .14       0
Bank Sta=4979.6,5020.4
XS Rating Curve= 0 ,0
Exp/Cntr=0.3,0.1

Type RM Length L Ch R = 1 ,87630   ,500,500,500
BEGIN DESCRIPTION:
Indian Field Swamp 175.0
END DESCRIPTION:
XS GIS Cut Line= 3
      2131652.22       513527.56      2131252.45       512706.74
      2130957.33       512122.99
#Sta/Elev= 30
    4087   90.06    4257   89.22    4377   86.55    4397   86.65    4407   87.85
    4427    83.8    4467   82.64    4497   83.92    4547   82.31    4647   82.52
    4657   83.04    4697   82.18    4747   82.71    4837   82.54    4877   81.98
    4897   82.77    4927   82.85  4979.6   79.98  4981.1   76.98  5018.9   76.98
  5020.4   79.98    5120   82.23    5260   82.14    5280   83.35    5380   85.63
    5390   84.71    5400   85.66    5510   85.72    5620   86.95  5654.1   86.82
#Mann= 3 ,-1,0
    4087     .14       0  4979.6    .045       0  5020.4     .14       0
Bank Sta=4979.6,5020.4
XS Rating Curve= 0 ,0
Exp/Cntr=0.3,0.1

Type RM Length L Ch R = 1 ,87130   ,500,500,500
BEGIN DESCRIPTION:
Indian Field Swamp 174.0
END DESCRIPTION:
XS GIS Cut Line= 3
      2132059.25       513124.25      2131702.89       512557.58
      2131258.96       511856.88
#Sta/Elev= 30
  4330.6   92.27  4390.6   91.65  4580.6   86.96  4620.6   85.31  4650.6   81.69
  4660.6   82.14  4680.6   81.23  4710.6   82.01  4780.6   81.55  4840.6   82.34
  4940.6   81.53  4950.6   82.26  4960.6   82.19  4970.6   81.91  4979.6   79.22
  4981.1   76.22  5018.9   76.22  5020.4   79.22    5040   81.96    5100   82.17
    5140   81.22    5160   82.32    5190   81.58    5350   82.67    5480   82.71
    5570   84.73    5760   86.65    5790   87.49    5820   86.46  5829.5   86.73
#Mann= 3 ,-1,0
  4330.6     .11       0  4979.6    .045       0  5020.4     .11       0
Bank Sta=4979.6,5020.4
XS Rating Curve= 0 ,0
Exp/Cntr=0.3,0.1

Type RM Length L Ch R = 1 ,86630   ,509,509,509
BEGIN DESCRIPTION:
Indian Field Swamp 173.0
END DESCRIPTION:
XS GIS Cut Line= 3
       2132335.3       512853.37      2131865.07       512153.21
      2131530.04        511635.1
#Sta/Elev= 30
  4156.6   92.31  4266.6   90.79  4416.6   87.08  4426.6   86.12  4436.6   83.66
  4456.6   81.35  4496.6   81.21  4506.6   81.81  4526.6   81.19  4546.6   81.66
  4566.6   81.26  4586.6   82.49  4596.6   81.51  4616.6   81.13  4976.6   81.71
  4979.6   79.13  4981.1   76.13  5018.9   76.13  5020.4   79.13    5050   81.59
    5260   82.08    5270   82.76    5280   82.27    5300   82.95    5350    82.1
    5460   82.23    5540   85.92    5560   85.25    5580    86.4    5617   87.21
#Mann= 3 ,-1,0
  4156.6     .11       0  4979.6    .045       0  5020.4     .11       0
Bank Sta=4979.6,5020.4
XS Rating Curve= 0 ,0
Exp/Cntr=0.3,0.1

Type RM Length L Ch R = 1 ,86121   ,424,424,424
BEGIN DESCRIPTION:
Indian Field Swamp 172.0
END DESCRIPTION:
XS GIS Cut Line= 3
      2132557.06       512424.57      2132326.42       511981.03
      2131980.46       511333.47
#Sta/Elev= 30
  4500.2   86.55  4550.2   86.36  4620.2   84.29  4630.2   83.77  4650.2    80.8
  4690.2    81.5  4720.2   80.78  4760.2   81.34  4800.2   80.68  4820.2   81.61
  4830.2   80.66  4880.2   80.95  4960.2   80.48  4979.6   78.39  4981.1   75.39
  5018.9   75.39  5020.4   78.39  5030.1   81.34  5220.1   81.44  5410.1   80.39
  5420.1   81.27  5430.1    80.8  5470.1   81.53  5500.1   80.91  5520.1   81.63
  5540.1   83.34  5670.1    86.8  5680.1   87.51  5700.1   86.44  5734.3    87.4
#Mann= 3 ,-1,0
  4500.2     .11       0  4979.6    .045       0  5020.4     .11       0
Bank Sta=4979.6,5020.4
XS Rating Curve= 0 ,0
Exp/Cntr=0.3,0.1

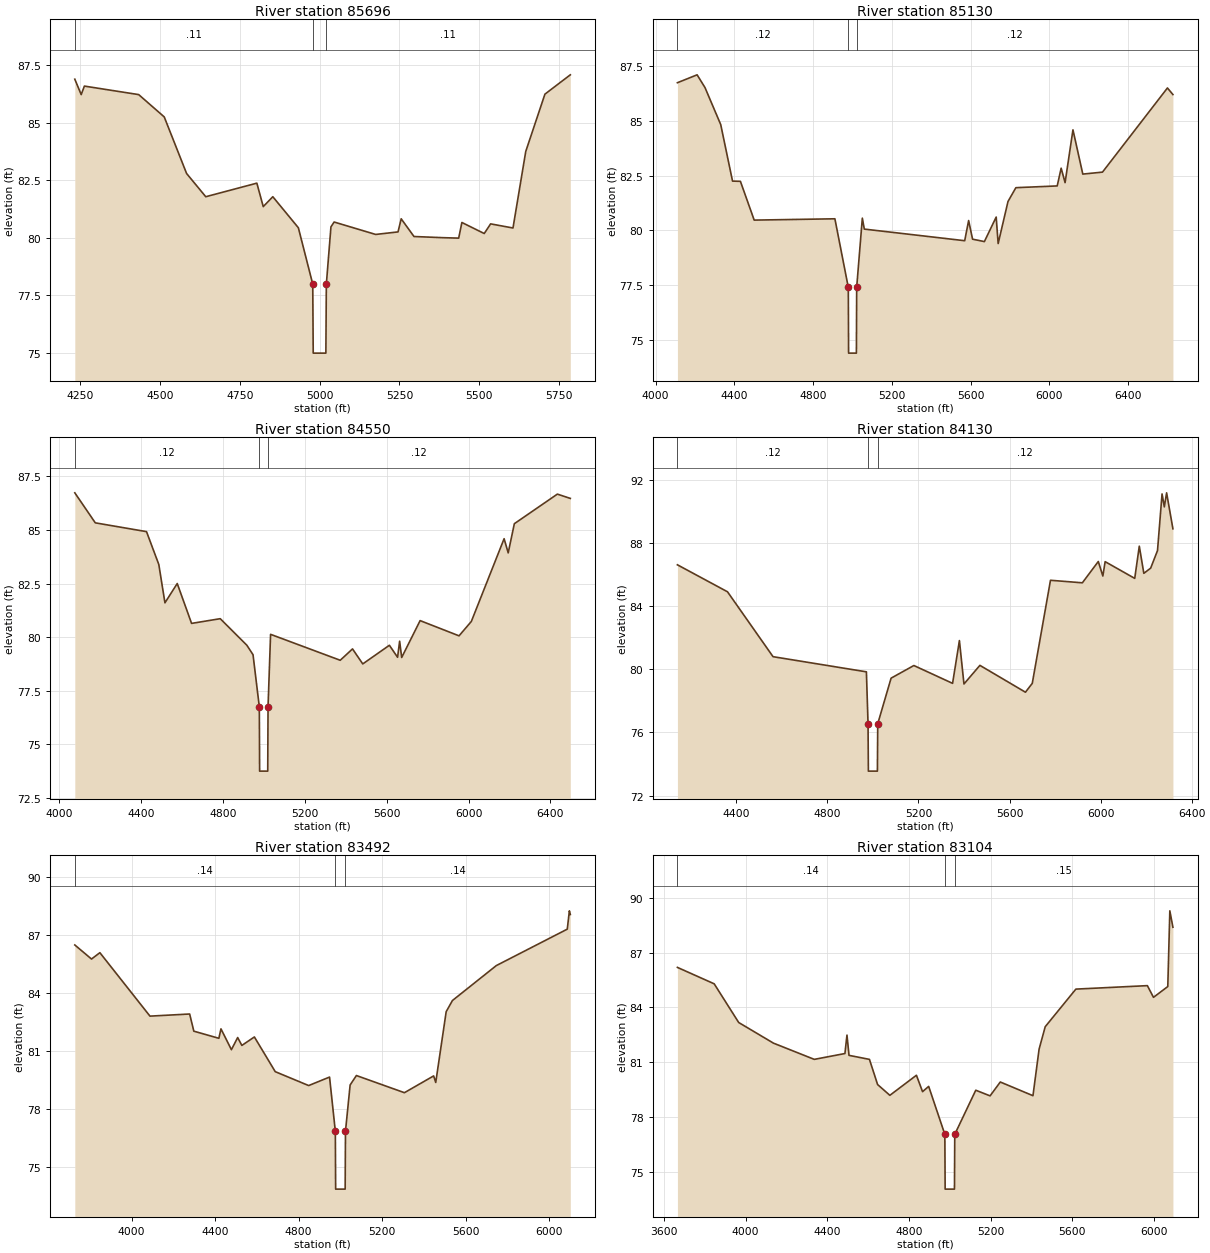
Type RM Length L Ch R = 1 ,85696   ,567,567,567
BEGIN DESCRIPTION:
Indian Field Swamp 171.0
END DESCRIPTION:
XS GIS Cut Line= 3
      2133225.37       512353.64      2132672.39       511800.66
      2132128.29       511256.56
#Sta/Elev= 30
  4233.7    86.9  4253.7   86.23  4263.7    86.6  4433.7   86.23  4513.7   85.26
  4583.7    82.8  4643.7   81.79  4803.7   82.38  4823.7   81.36  4853.7   81.79
  4933.7   80.44  4978.7   77.99  4980.2   74.99  5019.8   74.99  5021.3   77.99
  5035.7   80.48  5045.7   80.69  5175.7   80.15  5245.7   80.26  5255.7   80.83
  5295.7   80.06  5385.7   80.01  5435.7   79.99  5445.7   80.67  5515.7   80.19
  5535.7   80.61  5605.7   80.43  5645.7   83.76  5705.7   86.25  5785.2   87.09
#Mann= 3 ,-1,0
  4233.7     .11       0  4978.7    .045       0  5021.3     .11       0
Bank Sta=4978.7,5021.3
XS Rating Curve= 0 ,0
Exp/Cntr=0.3,0.1

Type RM Length L Ch R = 1 ,85130   ,579,579,579
BEGIN DESCRIPTION:
Indian Field Swamp 170.0
END DESCRIPTION:
XS GIS Cut Line= 3
       2133390.7       512161.84      2132970.85       511377.77
      2132212.52       509937.41
#Sta/Elev= 30
  4110.6   86.74  4210.6    87.1  4250.6   86.52  4330.6   84.83  4390.6   82.25
  4430.6   82.24  4500.6   80.47  4910.6   80.53  4978.7    77.4  4980.2    74.4
  5019.8    74.4  5021.3    77.4    5050   80.56    5060   80.06    5570   79.53
    5590   80.45    5610    79.6    5670   79.49    5730   80.61    5740    79.4
    5790   81.32    5830   81.95    6040   82.03    6060   82.84    6080   82.18
    6120   84.59    6170   82.57    6270   82.66    6600    86.5  6627.8    86.2
#Mann= 3 ,-1,0
  4110.6     .12       0  4978.7    .045       0  5021.3     .12       0
Bank Sta=4978.7,5021.3
XS Rating Curve= 0 ,0
Exp/Cntr=0.3,0.1

Type RM Length L Ch R = 1 ,84550   ,421,421,421
BEGIN DESCRIPTION:
Indian Field Swamp 169.0
END DESCRIPTION:
XS GIS Cut Line= 3
      2133904.76       512039.07      2133494.44       511209.25
      2132826.64       509873.73
#Sta/Elev= 30
    4078   86.73    4178   85.33    4428   84.92    4488   83.39    4518    81.6
    4578    82.5    4648   80.64    4788   80.86    4918   79.62    4948   79.18
  4978.7   76.75  4980.2   73.75  5019.8   73.75  5021.3   76.75  5033.7   80.13
  5373.7   78.92  5433.7   79.45  5483.7   78.75  5613.7   79.62  5653.7   79.06
  5663.7   79.81  5673.7   79.05  5763.7   80.77  5953.7   80.06  6013.7   80.73
  6173.7   84.59  6193.7   83.93  6223.7   85.29  6433.7   86.67  6496.9   86.47
#Mann= 3 ,-1,0
    4078     .12       0  4978.7    .045       0  5021.3     .12       0
Bank Sta=4978.7,5021.3
XS Rating Curve= 0 ,0
Exp/Cntr=0.3,0.1

Type RM Length L Ch R = 1 ,84130   ,638,638,638
BEGIN DESCRIPTION:
Indian Field Swamp 168.0
END DESCRIPTION:
XS GIS Cut Line= 3
      2134095.81       511684.23      2133764.23       510892.35
      2133263.34       509673.56
#Sta/Elev= 30
  4141.5   86.62  4361.5   84.91  4561.5    80.8  4971.5   79.84  4978.7   76.55
  4980.2   73.55  5019.8   73.55  5021.3   76.55    5080   79.44    5180   80.24
    5350   79.11    5380   81.82    5400   79.07    5470   80.25    5670   78.55
    5700   79.11    5780   85.64    5920   85.48    5990   86.83    6010   85.91
    6020   86.82    6150   85.76    6170    87.8    6190   86.08    6220   86.41
    6250   87.52    6270   91.11    6280   90.29    6290   91.18  6317.7    88.9
#Mann= 3 ,-1,0
  4141.5     .12       0  4978.7    .045       0  5021.3     .12       0
Bank Sta=4978.7,5021.3
XS Rating Curve= 0 ,0
Exp/Cntr=0.3,0.1

Type RM Length L Ch R = 1 ,83492   ,388,388,388
BEGIN DESCRIPTION:
Indian Field Swamp 167.0
END DESCRIPTION:
XS GIS Cut Line= 3
      2134629.19        511707.5      2134179.21       510521.34
      2133756.87       509500.83
#Sta/Elev= 30
    3728   86.49    3808   85.76    3848   86.09    4088    82.8    4278   82.91
    4298   82.02    4418   81.65    4428   82.14    4478   81.06    4508   81.69
    4528   81.28    4588   81.72    4688   79.92    4848    79.2    4948   79.64
  4975.7   76.83  4977.2   73.83  5022.8   73.83  5024.3   76.83  5046.6   79.23
  5076.6   79.72  5306.6   78.83  5446.6    79.7  5456.6   79.36  5506.6   83.03
  5536.6   83.61  5746.6   85.42  6086.6   87.31  6096.6   88.26  6101.1   88.07
#Mann= 3 ,-1,0
    3728     .14       0  4975.7    .045       0  5024.3     .14       0
Bank Sta=4975.7,5024.3
XS Rating Curve= 0 ,0
Exp/Cntr=0.3,0.1

Type RM Length L Ch R = 1 ,83104   ,522,522,522
BEGIN DESCRIPTION:
Indian Field Swamp 166.0
END DESCRIPTION:
XS GIS Cut Line= 3
      2134956.32       511718.61      2134555.61       510449.87
       2134203.2       509413.04
#Sta/Elev= 30
  3666.6   86.19  3846.6   85.29  3966.6   83.17  4136.6   82.04  4336.6   81.15
  4486.6   81.47  4496.6   82.48  4506.6   81.37  4606.6   81.15  4646.6   79.77
  4706.6   79.18  4836.6   80.28  4866.6   79.38  4896.6   79.67  4975.7   77.04
  4977.2   74.04  5022.8   74.04  5024.3   77.04  5127.1   79.46  5197.1   79.15
  5247.1   79.91  5407.1   79.16  5437.1   81.71  5467.1   82.94  5617.1      85
  5967.1   85.19  5997.1   84.55  6067.1   85.14  6077.1   89.29  6092.2   88.39
#Mann= 3 ,-1,0
  3666.6     .14       0  4975.7    .045       0  5024.3     .15       0
Bank Sta=4975.7,5024.3
XS Rating Curve= 0 ,0
Exp/Cntr=0.3,0.1

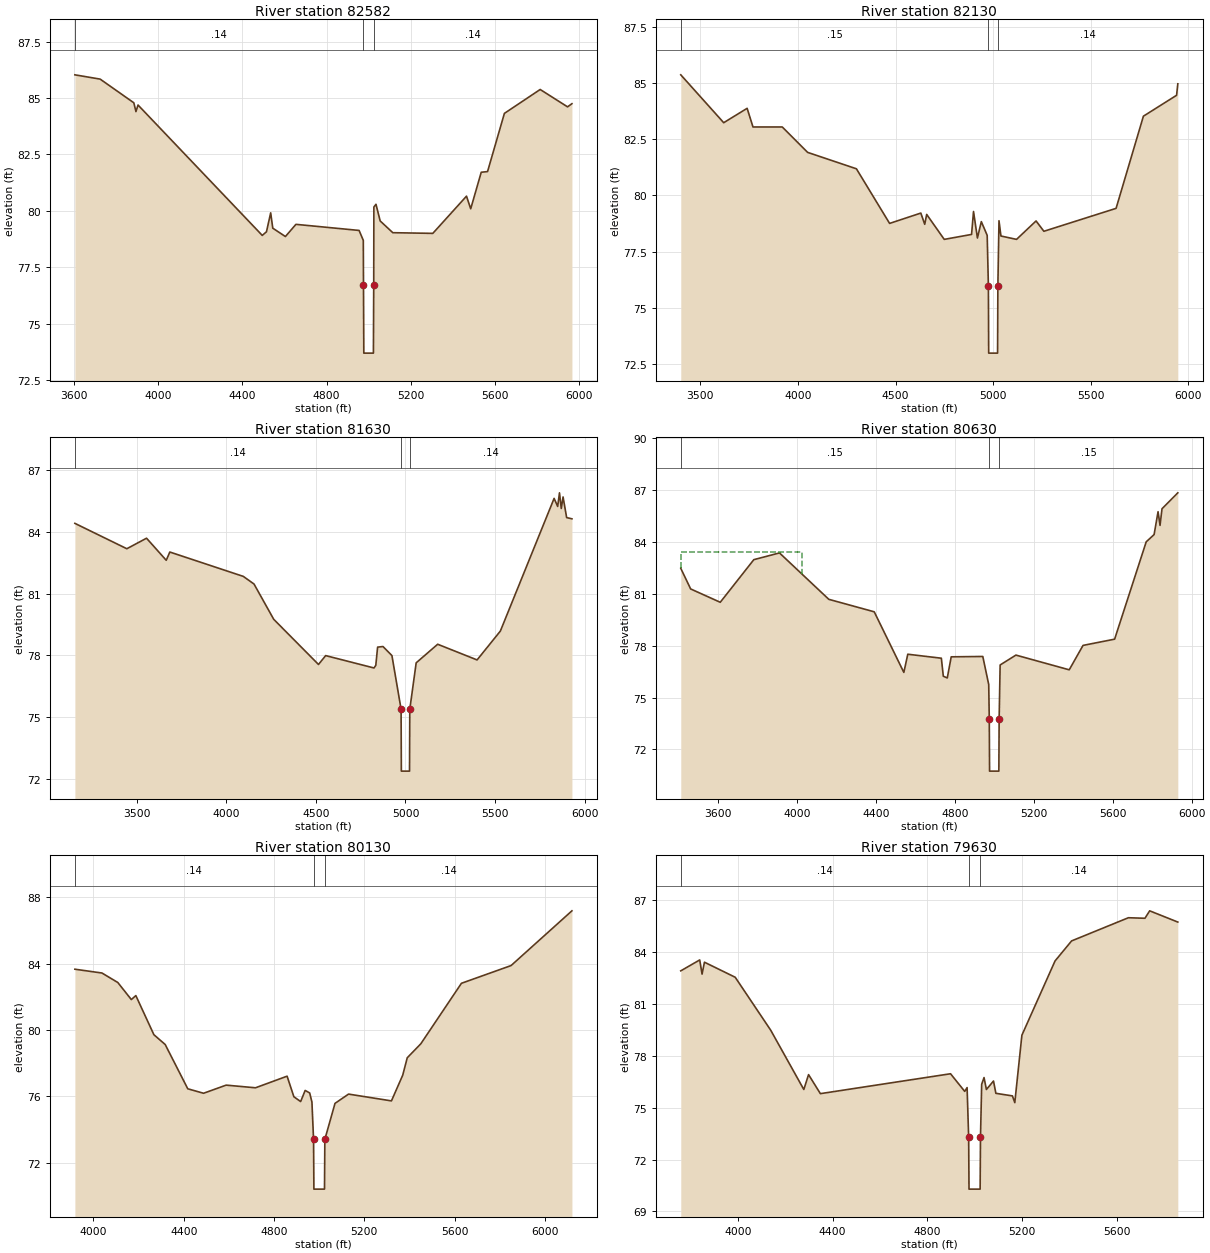
Type RM Length L Ch R = 1 ,82582   ,452,452,452
BEGIN DESCRIPTION:
Indian Field Swamp 165.0
END DESCRIPTION:
XS GIS Cut Line= 3
      2135350.16       511493.22      2134947.08        510152.3
      2134453.71       509327.83
#Sta/Elev= 30
  3604.8   86.03  3724.8   85.84  3884.8   84.79  3894.8    84.4  3904.8   84.69
  4494.8   78.91  4514.8   79.07  4534.8   79.91  4544.8   79.23  4604.8   78.86
  4654.8    79.4  4954.8   79.13  4974.8   78.69  4975.7   76.69  4977.2   73.69
  5022.8   73.69  5024.3   76.69    5025   80.17    5035   80.29    5055   79.55
    5115   79.03    5305      79    5465   80.65    5485   80.09    5535   81.71
    5565   81.74    5645   84.32    5815   85.38    5945   84.61  5965.8   84.75
#Mann= 3 ,-1,0
  3604.8     .14       0  4975.7    .045       0  5024.3     .14       0
Bank Sta=4975.7,5024.3
XS Rating Curve= 0 ,0
Exp/Cntr=0.3,0.1

Type RM Length L Ch R = 1 ,82130   ,500,500,500
BEGIN DESCRIPTION:
Indian Field Swamp 164.0
END DESCRIPTION:
XS GIS Cut Line= 3
      2135844.98       511487.77      2135343.37        509967.9
      2135022.54       509077.65
#Sta/Elev= 30
  3399.5   85.36  3619.5   83.23  3739.5   83.87  3769.5   83.04  3919.5   83.04
  4049.5   81.91  4299.5   81.18  4469.5   78.75  4629.5   79.21  4649.5   78.71
  4659.5   79.15  4749.5   78.04  4889.5   78.26  4899.5   79.28  4919.5    78.1
  4939.5   78.83  4969.5   78.22  4975.7   75.98  4977.2   72.98  5022.8   72.98
  5024.3   75.98    5030   78.87    5040   78.19    5120   78.04    5220   78.86
    5260    78.4    5630   79.42    5770   83.52    5940   84.45  5946.3   84.96
#Mann= 3 ,-1,0
  3399.5     .15       0  4975.7    .045       0  5024.3     .14       0
Bank Sta=4975.7,5024.3
XS Rating Curve= 0 ,0
Exp/Cntr=0.3,0.1

Type RM Length L Ch R = 1 ,81630   ,500,500,500
BEGIN DESCRIPTION:
Indian Field Swamp 163.0
END DESCRIPTION:
XS GIS Cut Line= 3
      2136190.86       511499.27      2135723.47       509714.04
      2135308.44       508882.35
#Sta/Elev= 30
  3154.6    84.4  3444.6   83.17  3554.6   83.68  3664.6   82.61  3684.6   83.01
  4094.6   81.83  4154.6   81.46  4264.6   79.75  4514.6   77.56  4554.6   77.99
  4824.6   77.39  4834.6   77.52  4844.6    78.4  4874.6   78.43  4924.6   77.99
  4975.7   75.39  4977.2   72.39  5022.8   72.39  5024.3   75.39    5060   77.64
    5180   78.54    5400   77.78    5530   79.18    5830   85.61    5850   85.22
    5860   85.88    5870   85.12    5880   85.68    5900   84.68  5929.5   84.62
#Mann= 3 ,-1,0
  3154.6     .14       0  4975.7    .045       0  5024.3     .14       0
Bank Sta=4975.7,5024.3
XS Rating Curve= 0 ,0
Exp/Cntr=0.3,0.1

Type RM Length L Ch R = 1 ,80630   ,500,500,500
BEGIN DESCRIPTION:
Indian Field Swamp 161.0
END DESCRIPTION:
XS GIS Cut Line= 3
      2136976.03       510873.91      2136473.74       509367.65
      2136161.28       508491.61
#Sta/Elev= 30
  3412.2   82.46  3462.2   81.27  3612.2    80.5  3782.2   82.96  3912.2   83.35
  4162.2   80.67  4392.2   79.95  4542.2   76.45  4562.2    77.5  4732.2   77.27
  4742.2   76.23  4762.2   76.13  4782.2   77.35  4942.2   77.37  4972.2   75.75
    4975   73.75  4976.5   70.75  5023.5   70.75    5025   73.75    5030   76.88
    5110   77.45    5380    76.6    5450   78.01    5610   78.37    5770   83.99
    5810   84.41    5830   85.73    5840   84.94    5850    85.9  5930.1   86.82
#Mann= 3 ,-1,0
  3412.2     .15       0    4975    .045       0    5025     .15       0
#XS Ineff= 2 , 0
          4026.4   83.41
Permanent Ineff=
       F       F
Bank Sta=4975,5025
XS Rating Curve= 0 ,0
Exp/Cntr=0.3,0.1

Type RM Length L Ch R = 1 ,80130   ,500,500,500
BEGIN DESCRIPTION:
Indian Field Swamp 160.0
END DESCRIPTION:
XS GIS Cut Line= 3
      2137186.23       510177.17      2136882.46       509138.47
      2136479.08       508094.17
#Sta/Elev= 30
  3917.8   83.66  4037.8   83.43  4107.8   82.86  4167.8   81.83  4187.8   82.07
  4267.8   79.71  4317.8   79.12  4417.8   76.45  4487.8   76.18  4587.8   76.67
  4717.8   76.51  4857.8   77.21  4887.8   75.97  4917.8   75.68  4937.8   76.35
  4957.8    76.2  4967.8   75.65    4975    73.4  4976.5    70.4  5023.5    70.4
    5025    73.4    5070   75.57    5130   76.13    5320   75.72    5370   77.27
    5390   78.32    5450   79.16    5630   82.81    5850   83.88  6119.5   87.18
#Mann= 3 ,-1,0
  3917.8     .14       0    4975    .045       0    5025     .14       0
Bank Sta=4975,5025
XS Rating Curve= 0 ,0
Exp/Cntr=0.3,0.1

Type RM Length L Ch R = 1 ,79630   ,500,500,500
BEGIN DESCRIPTION:
Indian Field Swamp 159.0
END DESCRIPTION:
XS GIS Cut Line= 3
      2137474.47       510054.21      2137207.18       508841.72
      2136994.09       508009.67
#Sta/Elev= 30
  3758.4   82.91  3838.4   83.54  3848.4   82.72  3858.4   83.41  3988.4   82.54
  4138.4   79.48  4278.4   76.05  4298.4   76.91  4348.4   75.81  4898.4   76.96
  4958.4   75.94  4968.4   76.16    4975   73.29  4976.5   70.29  5023.5   70.29
    5025   73.29    5030   76.35    5040   76.74    5050   76.05    5080   76.54
    5090   75.83    5160   75.68    5170   75.29    5200   79.19    5340   83.48
    5410   84.64    5650   85.98    5720   85.95    5740   86.38  5858.9   85.73
#Mann= 3 ,-1,0
  3758.4     .14       0    4975    .045       0    5025     .14       0
Bank Sta=4975,5025
XS Rating Curve= 0 ,0
Exp/Cntr=0.3,0.1

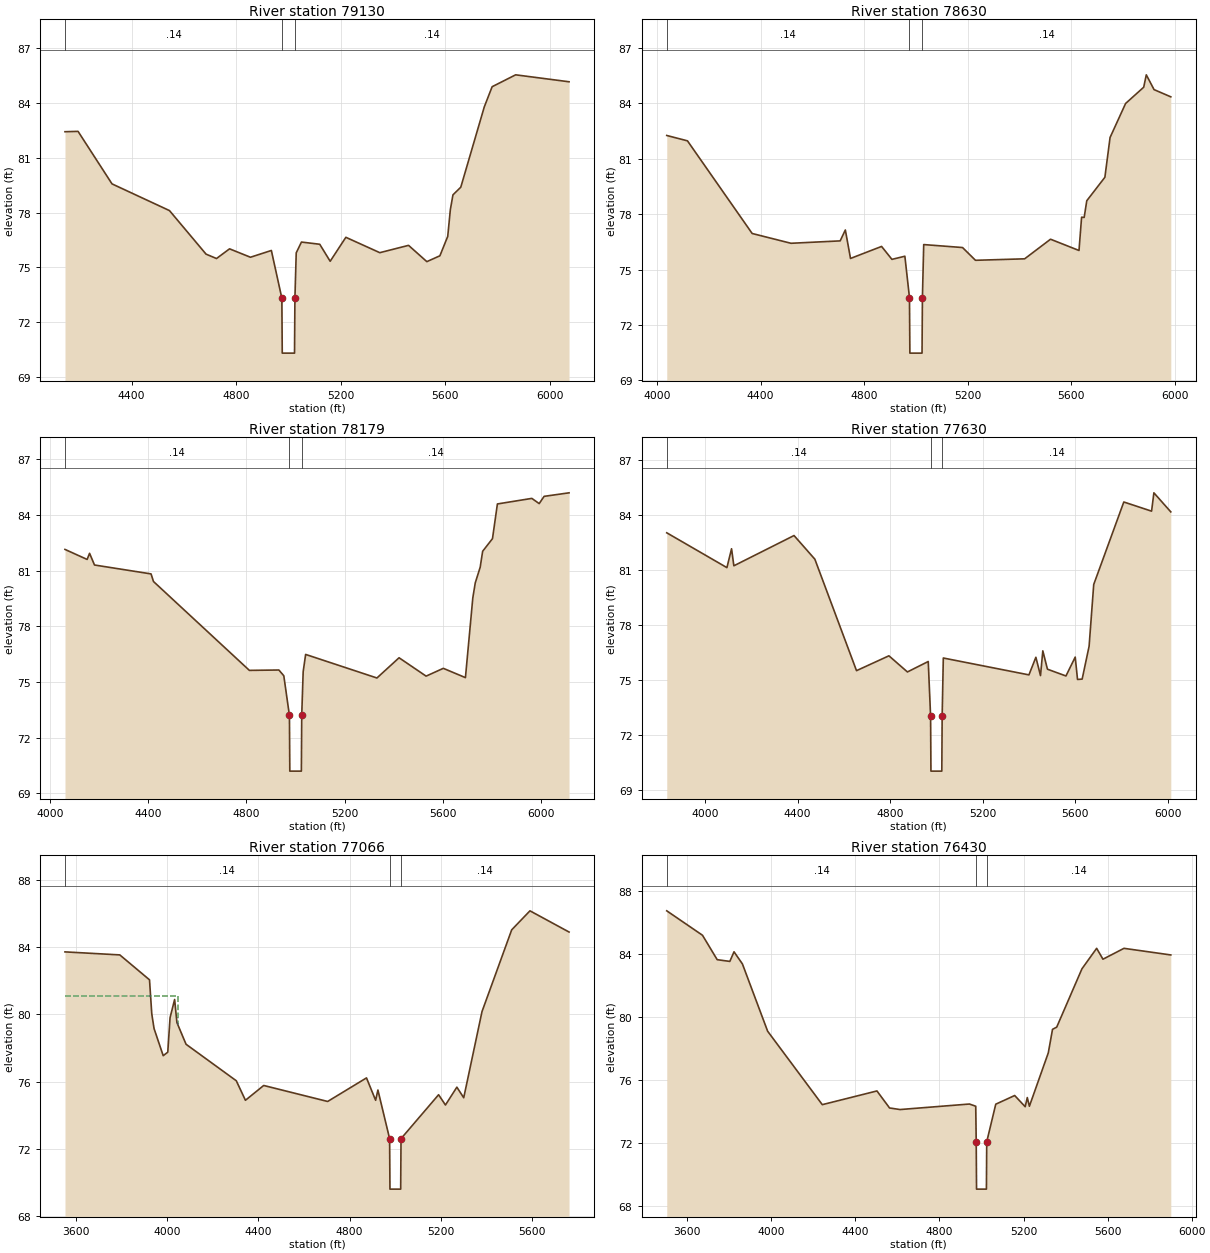
Type RM Length L Ch R = 1 ,79130   ,500,500,500
BEGIN DESCRIPTION:
Indian Field Swamp 158.0
END DESCRIPTION:
XS GIS Cut Line= 3
      2137825.01       509825.05      2137680.96       508982.07
      2137490.62       507924.66
#Sta/Elev= 30
  4144.8   82.42  4194.8   82.44  4324.8   79.57  4544.8   78.11  4684.8   75.73
  4724.8   75.49  4774.8   76.02  4854.8   75.56  4934.8   75.93    4975   73.32
  4976.5   70.32  5023.5   70.32    5025   73.32    5030    75.8    5050   76.39
    5120   76.27    5160   75.34    5220   76.65    5350   75.81    5460   76.21
    5530   75.32    5580   75.64    5610    76.7    5620   78.16    5630   78.97
    5660   79.39    5750   83.78    5780   84.88    5870   85.53  6074.4   85.15
#Mann= 3 ,-1,0
  4144.8     .14       0    4975    .045       0    5025     .14       0
Bank Sta=4975,5025
XS Rating Curve= 0 ,0
Exp/Cntr=0.3,0.1

Type RM Length L Ch R = 1 ,78630   ,450,450,450
BEGIN DESCRIPTION:
Indian Field Swamp 157.0
END DESCRIPTION:
XS GIS Cut Line= 3
      2138247.61       509742.82      2138109.01       508790.05
      2138022.46       507809.16
#Sta/Elev= 30
  4037.2   82.25  4117.2   81.96  4367.2   76.95  4517.2   76.42  4707.2   76.55
  4727.2   77.14  4747.2    75.6  4867.2   76.25  4907.2   75.55  4957.2   75.72
    4975   73.48  4976.5   70.48  5023.5   70.48    5025   73.48    5030   76.35
    5180   76.19    5230    75.5    5420   75.58    5520   76.64    5630   76.03
    5640   77.83    5650   77.82    5660   78.72    5730   79.99    5750   82.14
    5810   83.98    5880   84.86    5890   85.53    5920   84.73  5984.7   84.34
#Mann= 3 ,-1,0
  4037.2     .14       0    4975    .045       0    5025     .14       0
Bank Sta=4975,5025
XS Rating Curve= 0 ,0
Exp/Cntr=0.3,0.1

Type RM Length L Ch R = 1 ,78179   ,550,550,550
BEGIN DESCRIPTION:
Indian Field Swamp 156.0
END DESCRIPTION:
XS GIS Cut Line= 3
      2138567.41       509892.41      2138519.11       508944.88
      2138449.58       507845.63
#Sta/Elev= 30
  4062.1   82.14  4152.1    81.6  4162.1   81.93  4182.1    81.3  4412.1   80.82
  4422.1   80.41  4812.1   75.62  4932.1   75.64  4952.1   75.33    4975   73.19
  4976.5   70.19  5023.5   70.19    5025   73.19  5030.9   75.55  5040.9   76.48
  5330.9   75.21  5420.9    76.3  5530.9   75.31  5600.9   75.73  5690.9   75.23
  5720.9   79.53  5730.9   80.34  5750.9   81.18  5760.9   82.04  5800.9   82.72
  5820.9   84.59  5960.9   84.89  5990.9   84.61  6010.9      85  6112.3   85.19
#Mann= 3 ,-1,0
  4062.1     .14       0    4975    .045       0    5025     .14       0
Bank Sta=4975,5025
XS Rating Curve= 0 ,0
Exp/Cntr=0.3,0.1

Type RM Length L Ch R = 1 ,77630   ,563,563,563
BEGIN DESCRIPTION:
Indian Field Swamp 155.0
END DESCRIPTION:
XS GIS Cut Line= 3
      2139184.62       510090.48      2139064.55       508931.59
      2138953.34       507924.61
#Sta/Elev= 30
  3834.9   83.05  4094.9   81.15  4114.9   82.18  4124.9   81.25  4384.9    82.9
  4474.9   81.61  4654.9   75.53  4794.9   76.34  4874.9   75.46  4964.9   76.03
    4975   73.05  4976.5   70.05  5023.5   70.05    5025   73.05    5030   76.22
    5400    75.3    5430   76.26    5450   75.26    5460   76.61    5480   75.61
    5560   75.24    5600   76.27    5610   75.05    5630   75.07    5660   76.86
    5680   80.23    5810   84.73    5930   84.23    5940   85.23  6013.1   84.19
#Mann= 3 ,-1,0
  3834.9     .14       0    4975    .045       0    5025     .14       0
Bank Sta=4975,5025
XS Rating Curve= 0 ,0
Exp/Cntr=0.3,0.1

Type RM Length L Ch R = 1 ,77066   ,636,636,636
BEGIN DESCRIPTION:
Indian Field Swamp 154.0
END DESCRIPTION:
XS GIS Cut Line= 3
      2139872.91        510054.4      2139528.97        508650.2
      2139373.34       507905.19
#Sta/Elev= 30
  3553.8   83.71  3793.8   83.53  3923.8   82.05  3933.8   80.02  3943.8   79.15
  3983.8   77.54  4003.8   77.75  4013.8    79.8  4033.8   80.88  4043.8   79.51
  4083.8   78.22  4303.8   76.05  4343.8   74.89  4423.8   75.77  4703.8   74.82
  4873.8   76.22  4913.8   74.89  4923.8    75.5    4975   72.61  4976.5   69.61
  5023.5   69.61    5025   72.61  5189.5   75.22  5219.5   74.61  5269.5   75.67
  5299.5   75.04  5379.5   80.16  5509.5   85.02  5589.5   86.15  5760.6   84.89
#Mann= 3 ,-1,0
  3553.8     .14       0    4975    .045       0    5025     .14       0
#XS Ineff= 2 , 0
          4048.1   81.06
Permanent Ineff=
       F       F
Bank Sta=4975,5025
XS Rating Curve= 0 ,0
Exp/Cntr=0.3,0.1

Type RM Length L Ch R = 1 ,76430   ,529,529,529
BEGIN DESCRIPTION:
Indian Field Swamp 153.0
END DESCRIPTION:
XS GIS Cut Line= 3
      2140376.58       509934.88      2140087.32        508467.8
      2139919.66       507580.73
#Sta/Elev= 30
  3502.7   86.74  3672.7   85.19  3742.7   83.64  3802.7   83.53  3822.7   84.14
  3862.7   83.37  3982.7    79.1  4242.7   74.44  4502.7   75.31  4562.7   74.23
  4612.7   74.13  4942.7   74.48  4972.7   74.34    4975   72.08  4976.5   69.08
  5023.5   69.08    5025   72.08    5068   74.47    5158   75.02    5208   74.31
    5218   74.89    5228   74.34    5318   77.73    5338   79.22    5358   79.36
    5478   83.06    5548   84.36    5578   83.67    5678   84.36  5900.8   83.94
#Mann= 3 ,-1,0
  3502.7     .14       0    4975    .045       0    5025     .14       0
Bank Sta=4975,5025
XS Rating Curve= 0 ,0
Exp/Cntr=0.5,0.3