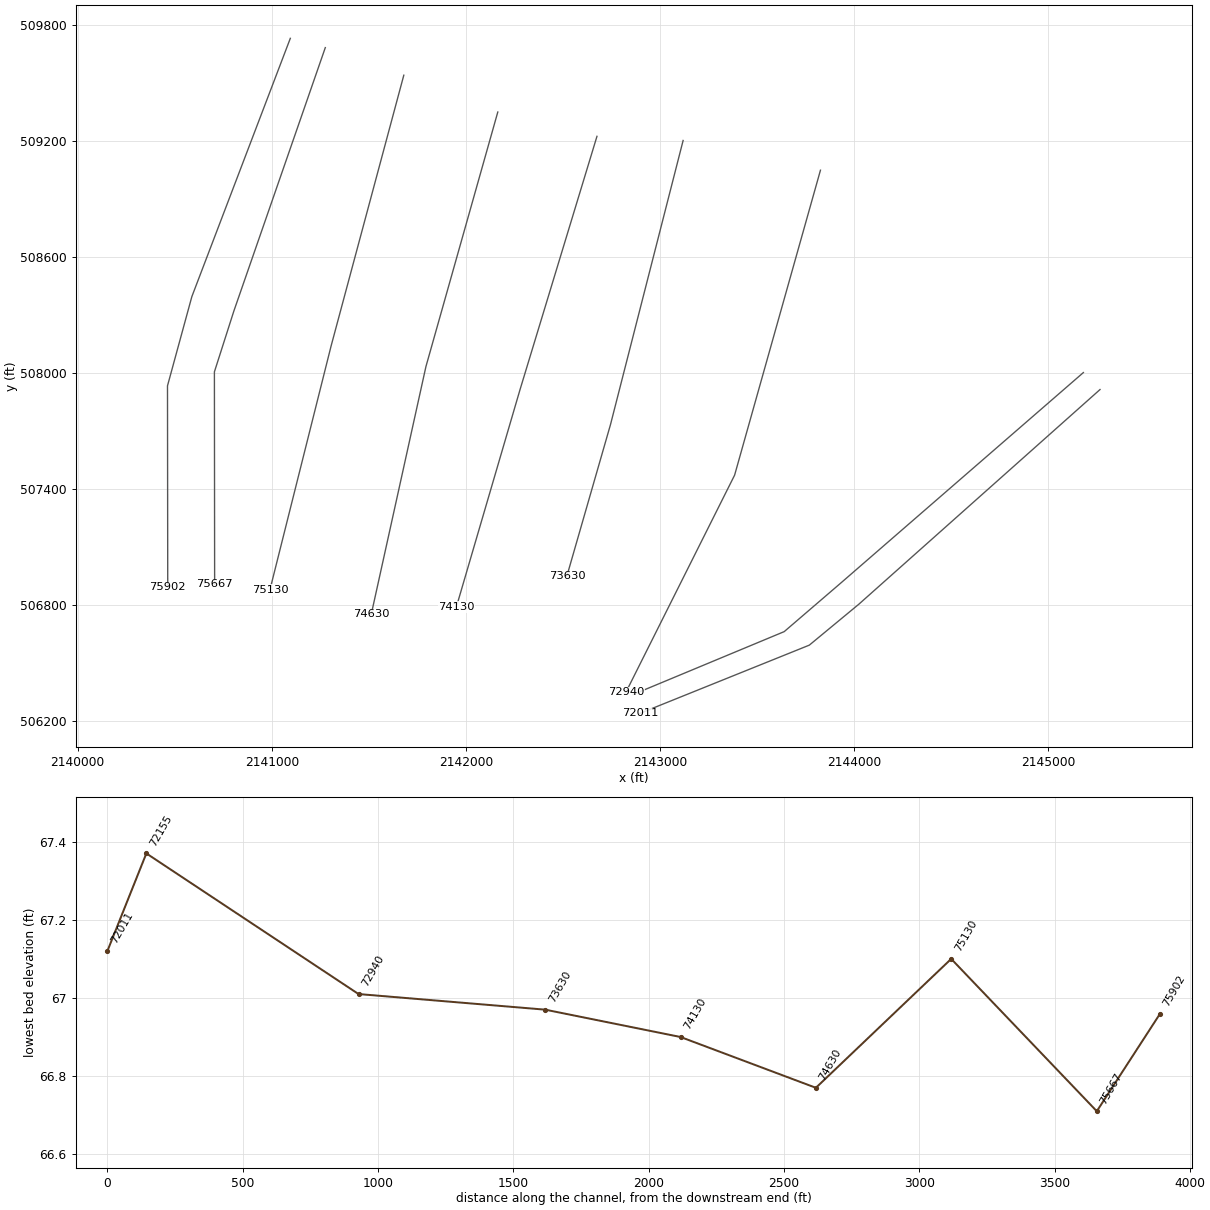
HEC-RAS study IndianFieldsSwamp.prj: S-18-19 over Indian Fields Swamp

--- IndianFieldsSwamp.g14 (geometry) --- (continued)

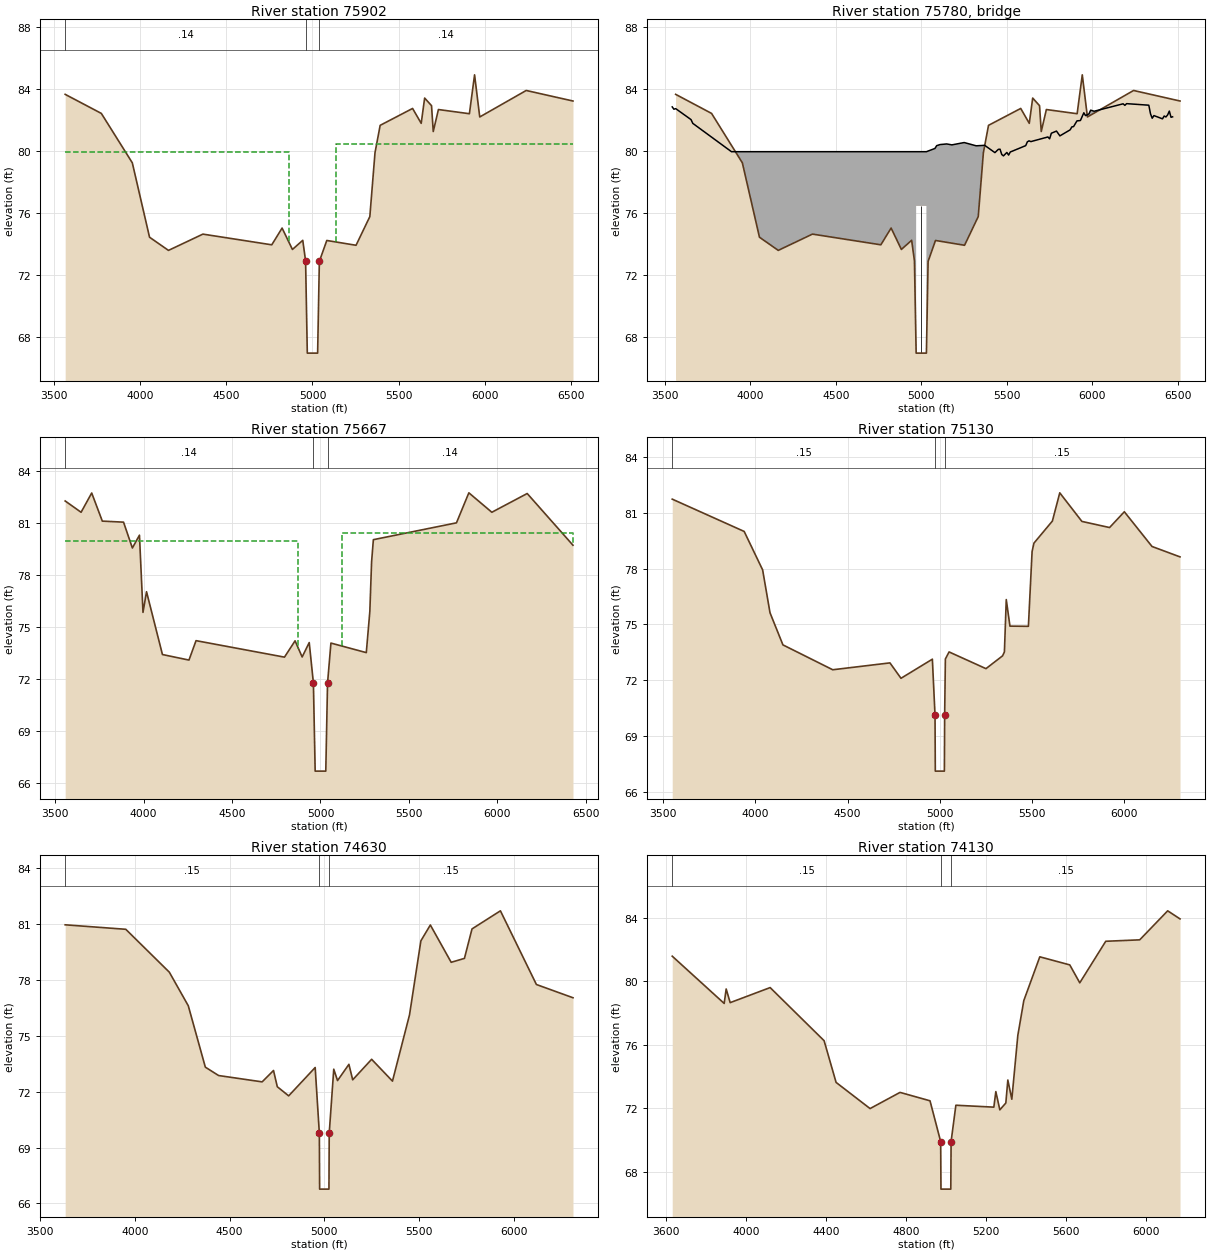
Type RM Length L Ch R = 1 ,75902   ,234,234,234
BEGIN DESCRIPTION:
Highway 15 at Indian Field - US
END DESCRIPTION:
XS GIS Cut Line= 4
      2141095.58       509730.61      2140588.44       508394.01
      2140462.93       507932.34       2140464.2       506890.74
#Sta/Elev= 30
  3563.6   83.66  3773.6   82.43  3953.6   79.24  4053.6   74.44  4163.6   73.59
  4363.6   74.64  4763.6   73.95  4823.6   75.03  4883.6   73.65  4943.6   74.24
    4960   72.92    4970   66.96    5030   66.96    5040   72.88  5083.2   74.23
  5253.2   73.92  5333.2   75.77  5363.2   79.89  5393.2   81.66  5581.6   82.75
  5631.6   81.79  5651.6   83.42  5691.6   82.93  5701.6   81.26  5731.6   82.68
  5911.6   82.41  5941.6   84.92  5971.6    82.2  6241.6   83.91  6513.2   83.23
#Mann= 3 ,-1,0
  3563.6     .14       0    4960    .045       0    5040     .14       0
#XS Ineff= 2 , 0
          4865.5   79.96  5134.5           80.45
Permanent Ineff=
       F       F
Bank Sta=4960,5040
XS Rating Curve= 0 ,0
Exp/Cntr=0.5,0.3

Type RM Length L Ch R = 3 ,75780   ,,,
BEGIN DESCRIPTION:
Highway 15 at Indian Field - TOR
Structure ID: LDS_IFS_05
Approximate Survey Structure
END DESCRIPTION:
Bridge Culvert--1,0,-1,-1, 0
Deck Dist Width WeirC Skew NumUp NumDn MinLoCord MaxHiCord MaxSubmerge Is_Ogee
104.5,35,3,0, 59, 59, , , 0.95, 0, 1,1,,
  3543.5  3553.5  3563.5  3653.5  3663.5  3889.8    4970    4970    5030    5030
    5080    5090    5110  5148.8  5178.8    5251    5321  5370.6  5430.6  5450.6
  5460.6  5470.6  5480.6  5500.6  5510.6  5520.6  5610.6  5620.6  5630.6  5640.6
  5740.6  5750.6  5760.6  5790.6  5810.6  5870.6  5880.6  5890.6  5910.6  5930.6
  5950.6  5960.6  5980.6  5990.6  6010.6  6180.6  6190.6  6200.6  6330.6  6340.6
  6350.6  6360.6  6410.6  6420.6  6430.6  6440.6  6450.6  6460.6  6469.6
   82.85    82.7   82.74   82.03   81.79   79.96   79.96   79.96   79.96   79.96
   80.17   80.35   80.42   80.46    80.4   80.55   80.34   80.37    79.9   80.11
   80.12   79.78   79.69   79.91   79.74   79.94   80.35    80.6   80.66   80.61
   80.91   80.79   81.15   81.29   80.98   81.37   81.56   81.58   81.95   81.97
   82.47   82.29    82.4   82.64   82.57   83.05   82.95   83.06   82.96    82.4
   82.12   82.29   82.08   82.26    82.2   82.33   82.58   82.18   82.21
   46.96   46.96   46.96   46.96   46.96   46.96   46.96   76.46   76.46   46.96
   46.96   46.96   46.96   46.96   46.96   46.96   46.96   46.96   46.96   46.96
   46.96   46.96   46.96   46.96   46.96   46.96   46.96   46.96   46.96   46.96
   46.96   46.96   46.96   46.96   46.96   46.96   46.96   46.96   46.96   46.96
   46.96   46.96   46.96   46.96   46.96   46.96   46.96   46.96   46.96   46.96
   46.96   46.96   46.96   46.96   46.96   46.96   46.96   46.96   46.96
  3543.5  3553.5  3563.5  3653.5  3663.5  3889.8    4970    4970    5030    5030
    5080    5090    5110  5148.8  5178.8    5251    5321  5370.6  5430.6  5450.6
  5460.6  5470.6  5480.6  5500.6  5510.6  5520.6  5610.6  5620.6  5630.6  5640.6
  5740.6  5750.6  5760.6  5790.6  5810.6  5870.6  5880.6  5890.6  5910.6  5930.6
  5950.6  5960.6  5980.6  5990.6  6010.6  6180.6  6190.6  6200.6  6330.6  6340.6
  6350.6  6360.6  6410.6  6420.6  6430.6  6440.6  6450.6  6460.6  6469.6
   82.85    82.7   82.74   82.03   81.79   79.96   79.96   79.96   79.96   79.96
   80.17   80.35   80.42   80.46    80.4   80.55   80.34   80.37    79.9   80.11
   80.12   79.78   79.69   79.91   79.74   79.94   80.35    80.6   80.66   80.61
   80.91   80.79   81.15   81.29   80.98   81.37   81.56   81.58   81.95   81.97
   82.47   82.29    82.4   82.64   82.57   83.05   82.95   83.06   82.96    82.4
   82.12   82.29   82.08   82.26    82.2   82.33   82.58   82.18   82.21
   46.96   46.96   46.96   46.96   46.96   46.96   46.96   76.46   76.46   46.96
   46.96   46.96   46.96   46.96   46.96   46.96   46.96   46.96   46.96   46.96
   46.96   46.96   46.96   46.96   46.96   46.96   46.96   46.96   46.96   46.96
   46.96   46.96   46.96   46.96   46.96   46.96   46.96   46.96   46.96   46.96
   46.96   46.96   46.96   46.96   46.96   46.96   46.96   46.96   46.96   46.96
   46.96   46.96   46.96   46.96   46.96   46.96   46.96   46.96   46.96
Pier Skew, UpSta & Num, DnSta & Num=  ,5000, 2 ,5000, 2 , 0 , 0 , 0 ,0,0
     1.5     1.5
   66.96   76.46
     1.5     1.5
   66.71   76.46
BR Coef=-1 ,-1 , 0 ,1.25, 0 ,,,0.8,-1,2,0,
WSPro=,,,, 1 ,,,, 0 ,,,, 0 ,,,,-1 ,-1 ,-1 , 0 , 0 , 0 , 0 , 0
BC Design=,, 0 ,, 0 ,,,,,,
BC HTab HWMax=84.92
BC Use User HTab Curves=0
BC User HTab FreeFlow(D)= 0

Type RM Length L Ch R = 1 ,75667   ,538,538,538
BEGIN DESCRIPTION:
Highway 15 at Indian Field - DS
END DESCRIPTION:
XS GIS Cut Line= 4
      2141275.76       509682.61      2140804.65       508318.96
      2140704.57       508004.64      2140705.76       506905.85
#Sta/Elev= 30
  3556.4   82.28  3646.4   81.63  3706.4   82.74  3766.4   81.12  3886.4   81.06
  3936.4   79.57  3976.4   80.31  3996.4   75.86  4016.4   77.05  4106.4   73.43
  4256.4   73.11  4296.4   74.23  4796.4   73.28  4856.4   74.22  4896.4   73.29
  4936.4   74.12    4960   71.79    4970   66.71    5030   66.71    5040   71.79
  5059.1   74.09  5259.1   73.54  5279.1   75.91  5289.1   78.78  5299.1   80.05
    5769   81.02    5839   82.75    5969   81.63    6169   82.71  6427.8   79.73
#Mann= 3 ,-1,0
  3556.4     .14       0    4960    .045       0    5040     .14       0
#XS Ineff= 2 , 0
          4875.5   79.96  5124.5           80.43
Permanent Ineff=
       F       F
Bank Sta=4960,5040
XS Rating Curve= 0 ,0
Exp/Cntr=0.5,0.3

Type RM Length L Ch R = 1 ,75130   ,500,500,500
BEGIN DESCRIPTION:
Indian Field Swamp 150.0
END DESCRIPTION:
XS GIS Cut Line= 3
      2141680.12       509539.81       2141305.6       508138.49
      2140990.22       506875.47
#Sta/Elev= 30
  3549.5   81.75  3939.5   80.01  4039.5   77.94  4079.5   75.63  4149.5    73.9
  4419.5   72.56  4729.5   72.93  4789.5    72.1  4959.5   73.13  4973.9    70.1
  4975.4    67.1  5024.6    67.1  5026.1    70.1    5030   73.14    5050   73.52
    5250   72.62    5340   73.31    5350   73.52    5360   76.34    5380   74.91
    5480    74.9    5500   78.93    5510   79.38    5610   80.57    5650   82.09
    5770   80.55    5920   80.22    6000   81.07    6150    79.2  6301.8   78.64
#Mann= 3 ,-1,0
  3549.5     .15       0  4973.9    .045       0  5026.1     .15       0
Bank Sta=4973.9,5026.1
XS Rating Curve= 0 ,0
Exp/Cntr=0.3,0.1

Type RM Length L Ch R = 1 ,74630   ,500,500,500
BEGIN DESCRIPTION:
Indian Field Swamp 149.0
END DESCRIPTION:
XS GIS Cut Line= 3
      2142164.22       509349.26      2141794.12       508032.17
      2141512.41       506749.65
#Sta/Elev= 30
  3631.9   80.94  3951.9    80.7  4181.9    78.4  4281.9    76.6  4371.9   73.31
  4441.9   72.86  4671.9   72.52  4731.9   73.13  4751.9   72.26  4811.9   71.77
  4951.9   73.29  4973.9   69.77  4975.4   66.77  5024.6   66.77  5026.1   69.77
    5050    73.2    5070   72.59    5130   73.46    5150   72.63    5250   73.73
    5360   72.56    5450   76.11    5510   80.08    5560   80.93    5670   78.93
    5740   79.14    5780   80.72    5930   81.69    6120   77.74  6313.1   77.03
#Mann= 3 ,-1,0
  3631.9     .15       0  4973.9    .045       0  5026.1     .15       0
Bank Sta=4973.9,5026.1
XS Rating Curve= 0 ,0
Exp/Cntr=0.3,0.1

Type RM Length L Ch R = 1 ,74130   ,500,500,500
BEGIN DESCRIPTION:
Indian Field Swamp 148.0
END DESCRIPTION:
XS GIS Cut Line= 3
      2142674.97       509223.43      2142278.68       507912.63
      2141950.75       506787.76
#Sta/Elev= 30
  3630.6   81.59  3890.6   78.61  3900.6   79.52  3920.6   78.66  4120.6   79.61
  4390.6   76.26  4450.6   73.63  4620.6   71.98  4770.6      73  4920.6   72.47
  4973.9    69.9  4975.4    66.9  5024.6    66.9  5026.1    69.9    5050   72.19
    5240   72.07    5250   73.05    5270    71.9    5300   72.33    5310   73.78
    5330   72.57    5360   76.59    5390   78.79    5470   81.55    5620   81.04
    5670   79.91    5800   82.53    5970   82.62    6110   84.45  6171.7   83.94
#Mann= 3 ,-1,0
  3630.6     .15       0  4973.9    .045       0  5026.1     .15       0
Bank Sta=4973.9,5026.1
XS Rating Curve= 0 ,0
Exp/Cntr=0.3,0.1

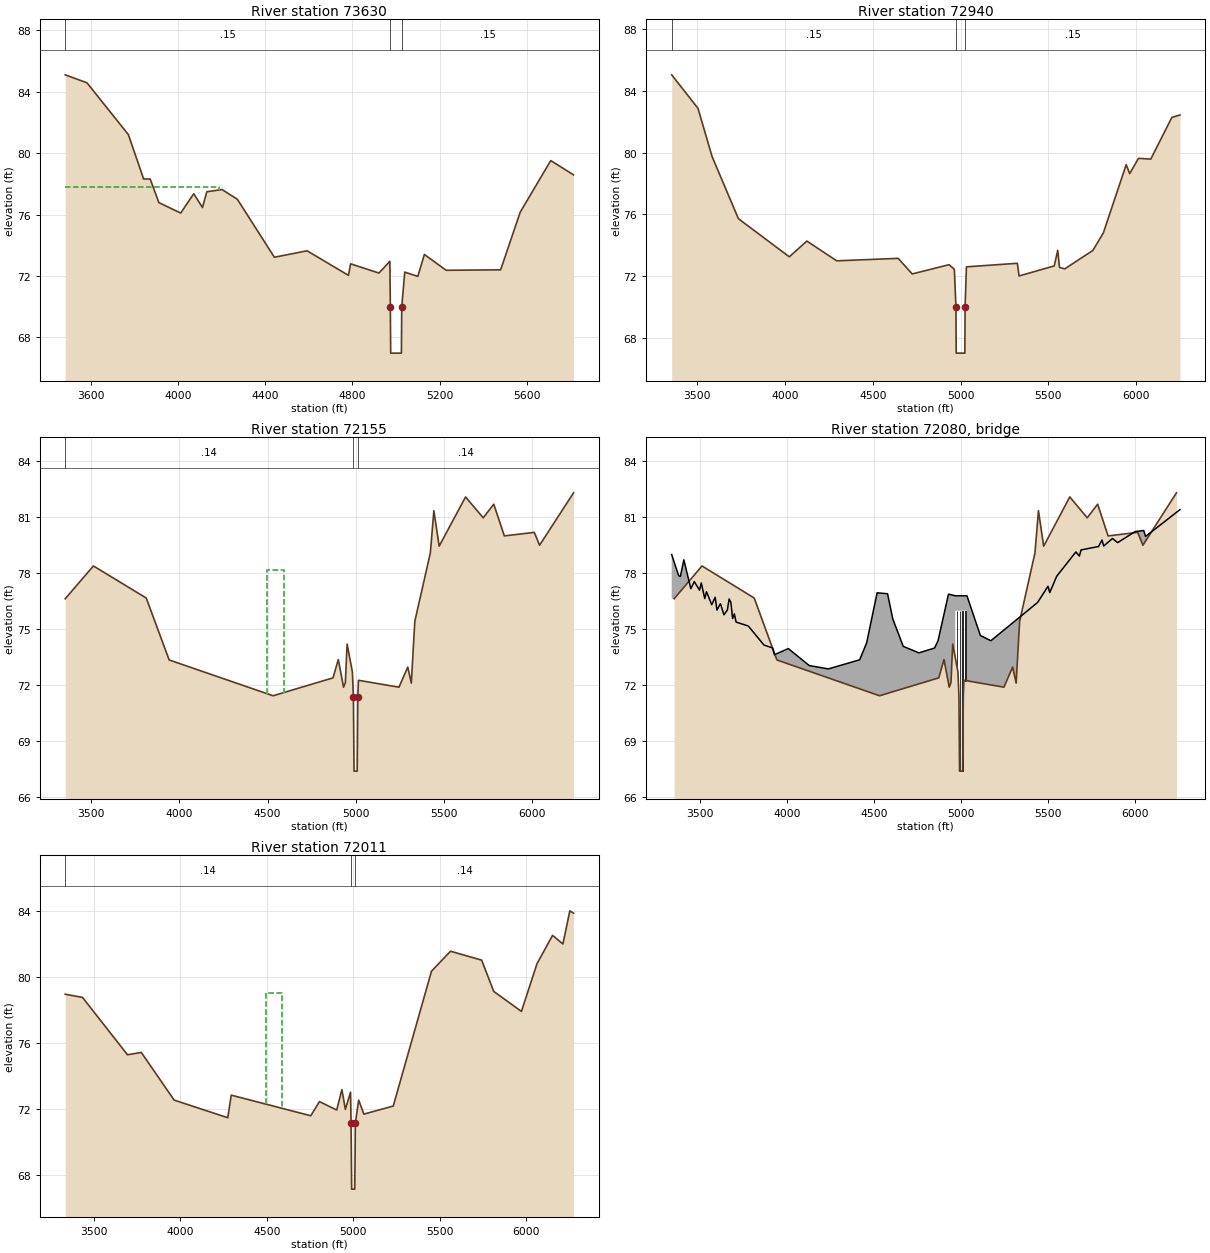
Type RM Length L Ch R = 1 ,73630   ,690,690,690
BEGIN DESCRIPTION:
Indian Field Swamp 147.0
END DESCRIPTION:
XS GIS Cut Line= 3
      2143118.76       509201.99      2142744.33       507730.48
      2142519.95        506947.4
#Sta/Elev= 30
  3481.6   85.11  3581.6   84.59  3771.6   81.21  3841.6   78.32  3871.6   78.32
  3911.6   76.78  4011.6    76.1  4071.6   77.36  4111.6   76.46  4131.6   77.49
  4201.6   77.63  4271.6      77  4441.6   73.22  4591.6   73.64  4781.6   72.04
  4791.6   72.79  4921.6   72.19  4971.6   72.95  4973.9   69.97  4975.4   66.97
  5024.6   66.97  5026.1   69.97    5040   72.25    5100   71.97    5130    73.4
    5230   72.37    5480    72.4    5570   76.16    5710   79.52  5814.6   78.59
#Mann= 3 ,-1,0
  3481.6     .15       0  4973.9    .045       0  5026.1     .15       0
#XS Ineff= 2 , 0
          4187.8   77.78  5812.2           77.78
Permanent Ineff=
       F       F
Bank Sta=4973.9,5026.1
XS Rating Curve= 0 ,0
Exp/Cntr=0.3,0.1

Type RM Length L Ch R = 1 ,72940   ,784,784,784
BEGIN DESCRIPTION:
Indian Field Swamp 146.0
END DESCRIPTION:
XS GIS Cut Line= 3
      2143826.11       509048.15      2143383.95       507470.09
      2142823.61        506345.6
#Sta/Elev= 30
  3354.9   85.04  3504.9   82.87  3584.9   79.75  3734.9   75.72  4024.9   73.25
  4124.9   74.27  4294.9   72.99  4644.9   73.15  4724.9   72.14  4934.9   72.74
  4964.9   72.44  4973.9   70.01  4975.4   67.01  5024.6   67.01  5026.1   70.01
  5033.7    72.6  5323.7   72.83  5333.7   72.01  5533.7   72.66  5553.7   73.67
  5563.7   72.56  5593.7   72.47  5753.7   73.66  5813.7    74.8  5943.7   79.22
  5963.7   78.64  6013.7   79.63  6083.7   79.58  6203.7   82.28  6250.1   82.44
#Mann= 3 ,-1,0
  3354.9     .15       0  4973.9    .045       0  5026.1     .15       0
Bank Sta=4973.9,5026.1
XS Rating Curve= 0 ,0
Exp/Cntr=0.5,0.3

Type RM Length L Ch R = 1 ,72155   ,144,144,144
BEGIN DESCRIPTION:
Gavins Road - US
END DESCRIPTION:
XS GIS Cut Line= 4
      2145180.31       508000.94      2143933.27       506913.81
      2143639.38       506660.26      2142861.95       506335.14
#Sta/Elev= 30
  3351.7   76.61  3511.7   78.37  3811.7   76.65  3941.7   73.33  4531.7   71.41
  4871.7   72.37  4901.7   73.35  4931.7   71.87  4941.7   72.11  4951.7   74.18
  4981.7   72.69  4987.5   71.37    4991   67.37    5009   67.37  5012.5   71.37
  5016.1   72.24  5246.1   71.87  5296.1   72.95  5316.1   72.09  5336.1    75.4
  5424.2   79.07  5444.2   81.33  5474.2   79.43  5624.2   82.07  5724.2   80.95
  5784.2   81.68  5844.2   79.98  6014.2   80.17  6044.2   79.48  6236.9   82.29
#Mann= 3 ,-1,0
  3351.7     .14       0  4987.5    .045       0  5012.5     .14       0
#XS Ineff= 1 ,-1
  4494.8  4590.8   78.17
Permanent Ineff=
       F
Bank Sta=4987.5,5012.5
XS Rating Curve= 0 ,0
Exp/Cntr=0.5,0.3

Type RM Length L Ch R = 3 ,72080   ,,,
BEGIN DESCRIPTION:
Gavins Road - TOR
Structure ID: LDS_IFS_04
Approximate Survey Structure
END DESCRIPTION:
Bridge Culvert--1,0,-1,-1, 0
Deck Dist Width WeirC Skew NumUp NumDn MinLoCord MaxHiCord MaxSubmerge Is_Ogee
62.5,25,3,0, 60, 60, , , 0.95, 0, 1,1,,
  3337.5  3377.5  3387.5  3407.5  3447.5  3467.5  3497.5  3507.5  3527.5  3537.5
  3567.5  3587.5  3597.5  3617.5  3637.5  3657.5  3667.5  3677.5  3687.5  3697.5
  3707.5  3777.5  3867.5  3917.5  3927.5  4007.5  4127.5  4237.5  4417.5  4457.5
  4517.5  4577.5  4607.5  4667.5  4757.5  4847.5  4867.5  4927.5  4966.5  4966.5
  5033.5  5033.5  5110.7  5170.7  5439.1  5499.1  5509.1  5549.1  5659.1  5679.1
  5689.1  5789.1  5809.1  5819.1  5869.1  5899.1  5999.1  6049.1  6059.1  6257.2
   78.98   77.85   77.81    78.7   77.15   77.53   77.07   77.46   76.62   76.99
   76.29   76.69      76   76.35   75.75   76.01    76.6   76.42   75.55    75.8
   75.36   75.15   74.13   73.97   73.61   73.94   73.03   72.85   73.34   74.25
   76.93   76.88   75.53   74.06   73.71   73.97   74.36   76.86   76.77   76.77
   76.77   76.77   74.64   74.36   76.41   77.28   76.94   77.82   79.12    78.9
   79.23   79.41   79.76   79.44   79.84   79.62   80.21   80.27   79.95   81.39
   47.37   47.37   47.37   47.37   47.37   47.37   47.37   47.37   47.37   47.37
   47.37   47.37   47.37   47.37   47.37   47.37   47.37   47.37   47.37   47.37
   47.37   47.37   47.37   47.37   47.37   47.37   47.37   47.37   47.37   47.37
   47.37   47.37   47.37   47.37   47.37   47.37   47.37   47.37   47.37   75.97
   75.97   47.37   47.37   47.37   47.37   47.37   47.37   47.37   47.37   47.37
   47.37   47.37   47.37   47.37   47.37   47.37   47.37   47.37   47.37   47.37
  3337.5  3377.5  3387.5  3407.5  3447.5  3467.5  3497.5  3507.5  3527.5  3537.5
  3567.5  3587.5  3597.5  3617.5  3637.5  3657.5  3667.5  3677.5  3687.5  3697.5
  3707.5  3777.5  3867.5  3917.5  3927.5  4007.5  4127.5  4237.5  4417.5  4457.5
  4517.5  4577.5  4607.5  4667.5  4757.5  4847.5  4867.5  4927.5  4966.5  4966.5
  5033.5  5033.5  5110.7  5170.7  5439.1  5499.1  5509.1  5549.1  5659.1  5679.1
  5689.1  5789.1  5809.1  5819.1  5869.1  5899.1  5999.1  6049.1  6059.1  6257.2
   78.98   77.85   77.81    78.7   77.15   77.53   77.07   77.46   76.62   76.99
   76.29   76.69      76   76.35   75.75   76.01    76.6   76.42   75.55    75.8
   75.36   75.15   74.13   73.97   73.61   73.94   73.03   72.85   73.34   74.25
   76.93   76.88   75.53   74.06   73.71   73.97   74.36   76.86   76.77   76.77
   76.77   76.77   74.64   74.36   76.41   77.28   76.94   77.82   79.12    78.9
   79.23   79.41   79.76   79.44   79.84   79.62   80.21   80.27   79.95   81.39
   47.37   47.37   47.37   47.37   47.37   47.37   47.37   47.37   47.37   47.37
   47.37   47.37   47.37   47.37   47.37   47.37   47.37   47.37   47.37   47.37
   47.37   47.37   47.37   47.37   47.37   47.37   47.37   47.37   47.37   47.37
   47.37   47.37   47.37   47.37   47.37   47.37   47.37   47.37   47.37   75.97
   75.97   47.37   47.37   47.37   47.37   47.37   47.37   47.37   47.37   47.37
   47.37   47.37   47.37   47.37   47.37   47.37   47.37   47.37   47.37   47.37
Pier Skew, UpSta & Num, DnSta & Num=  ,4974.9, 2 ,4974.9, 2 , 0 , 0 , 0 ,0,0
     1.1     1.1
   72.82   75.97
     1.1     1.1
   72.49   75.97
Pier Skew, UpSta & Num, DnSta & Num=  ,4991.6, 2 ,4991.6, 2 , 0 , 0 , 0 ,0,0
     1.1     1.1
   67.37   75.97
     1.1     1.1
   67.12   75.97
Pier Skew, UpSta & Num, DnSta & Num=  ,5008.4, 2 ,5008.4, 2 , 0 , 0 , 0 ,0,0
     1.1     1.1
   67.37   75.97
     1.1     1.1
   67.12   75.97
Pier Skew, UpSta & Num, DnSta & Num=  ,5025.1, 2 ,5025.1, 2 , 0 , 0 , 0 ,0,0
     1.1     1.1
      72   75.97
     1.1     1.1
   72.04   75.97
Abutment Skew #Up #Dn= , 2 , 2
  4966.5    4968
   75.97    73.1
  4966.5    4968
   75.97    72.3
Abutment Skew #Up #Dn= , 2 , 2
    5032  5033.5
   72.05   75.97
    5032  5033.5
    72.5   75.97
BR Coef=-1 ,-1 , 0 ,1.25, 0 ,,,0.8,0,2,0,
WSPro=,,,, 1 ,,,, 0 ,,,, 0 ,,,,-1 ,-1 ,-1 , 0 , 0 , 0 , 0 , 0
BC Design=,, 0 ,, 0 ,,,,,,
BC HTab HWMax=82.29
BC Use User HTab Curves=0
BC User HTab FreeFlow(D)= 0

Type RM Length L Ch R = 1 ,72011   ,694,694,694
BEGIN DESCRIPTION:
Gavins Road - DS
END DESCRIPTION:
XS GIS Cut Line= 4
      2145266.01       507913.06      2144023.39       506801.78
       2143768.7       506590.31      2142896.14       506237.18
#Sta/Elev= 30
  3334.6   78.94  3434.6   78.75  3694.6   75.27  3774.6   75.41  3964.6   72.52
  4274.6   71.45  4294.6   72.82  4754.6   71.57  4804.6   72.43  4904.6   71.92
  4934.6   73.16  4954.6   71.96  4984.6      73  4987.5   71.12    4991   67.12
    5009   67.12  5012.5   71.12  5031.6   72.52  5061.6   71.67  5231.6   72.16
  5452.7   80.34  5562.7   81.55  5742.7   81.01  5812.7   79.11  5972.7    77.9
  6062.7   80.79  6152.7   82.51  6212.7   81.99  6252.7      84    6274   83.86
#Mann= 3 ,-1,0
  3334.6     .14       0  4987.5    .045       0  5012.5     .14       0
#XS Ineff= 1 ,-1
  4496.8  4590.5      79
Permanent Ineff=
       F
Bank Sta=4987.5,5012.5
XS Rating Curve= 0 ,0
Exp/Cntr=0.5,0.3