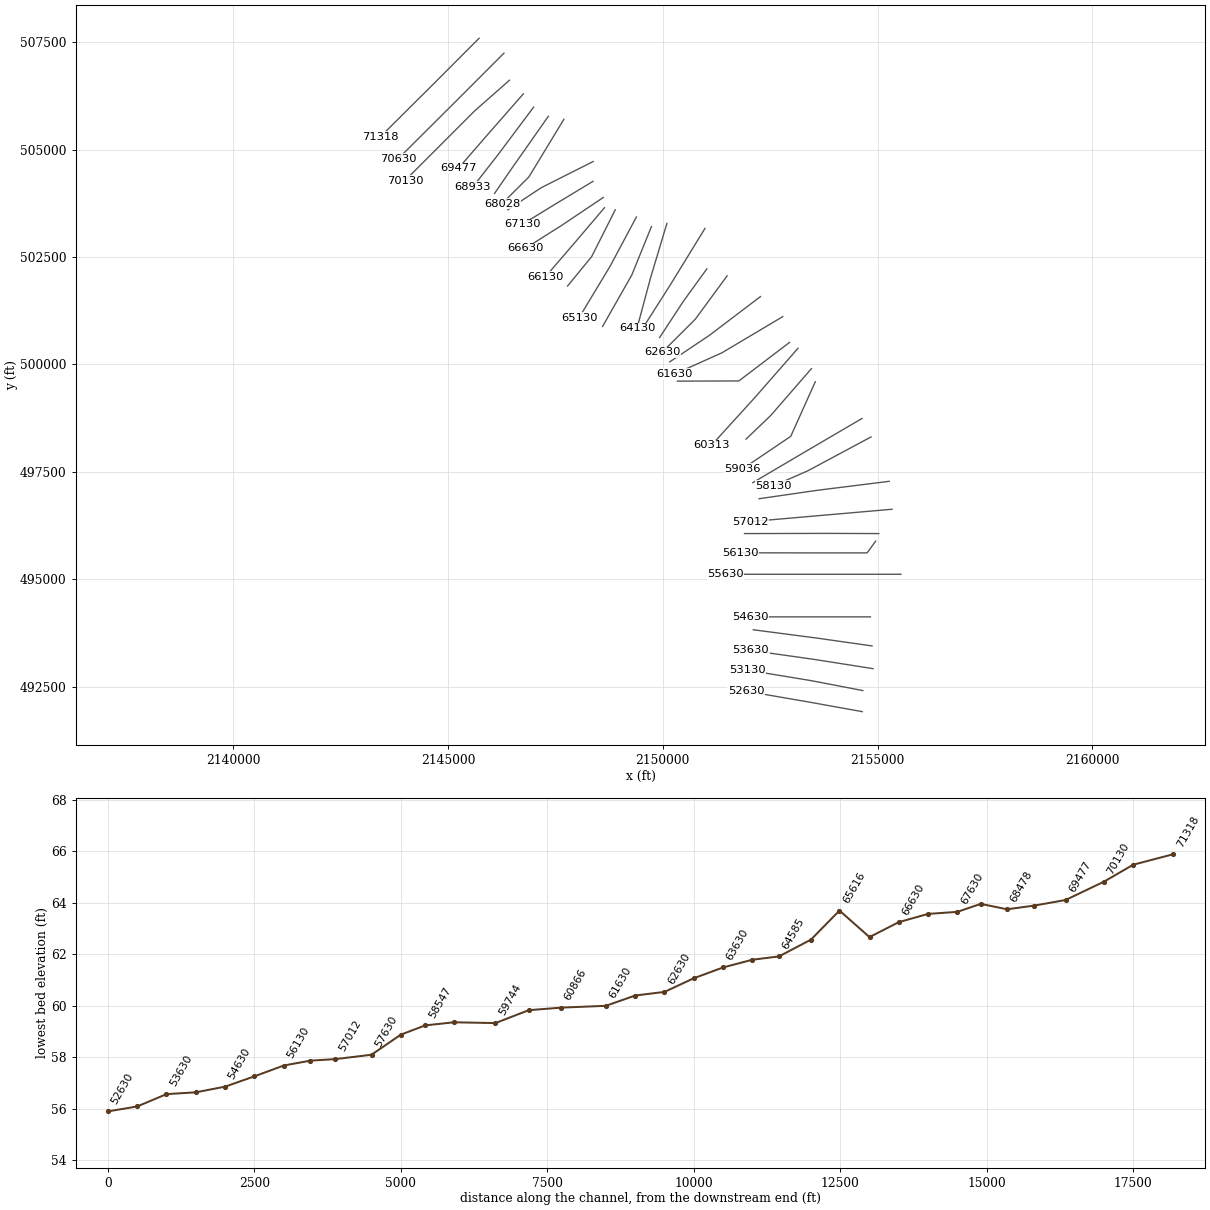
HEC-RAS study IndianFieldsSwamp.prj: S-18-19 over Indian Fields Swamp

--- IndianFieldsSwamp.g14 (geometry) --- (continued)

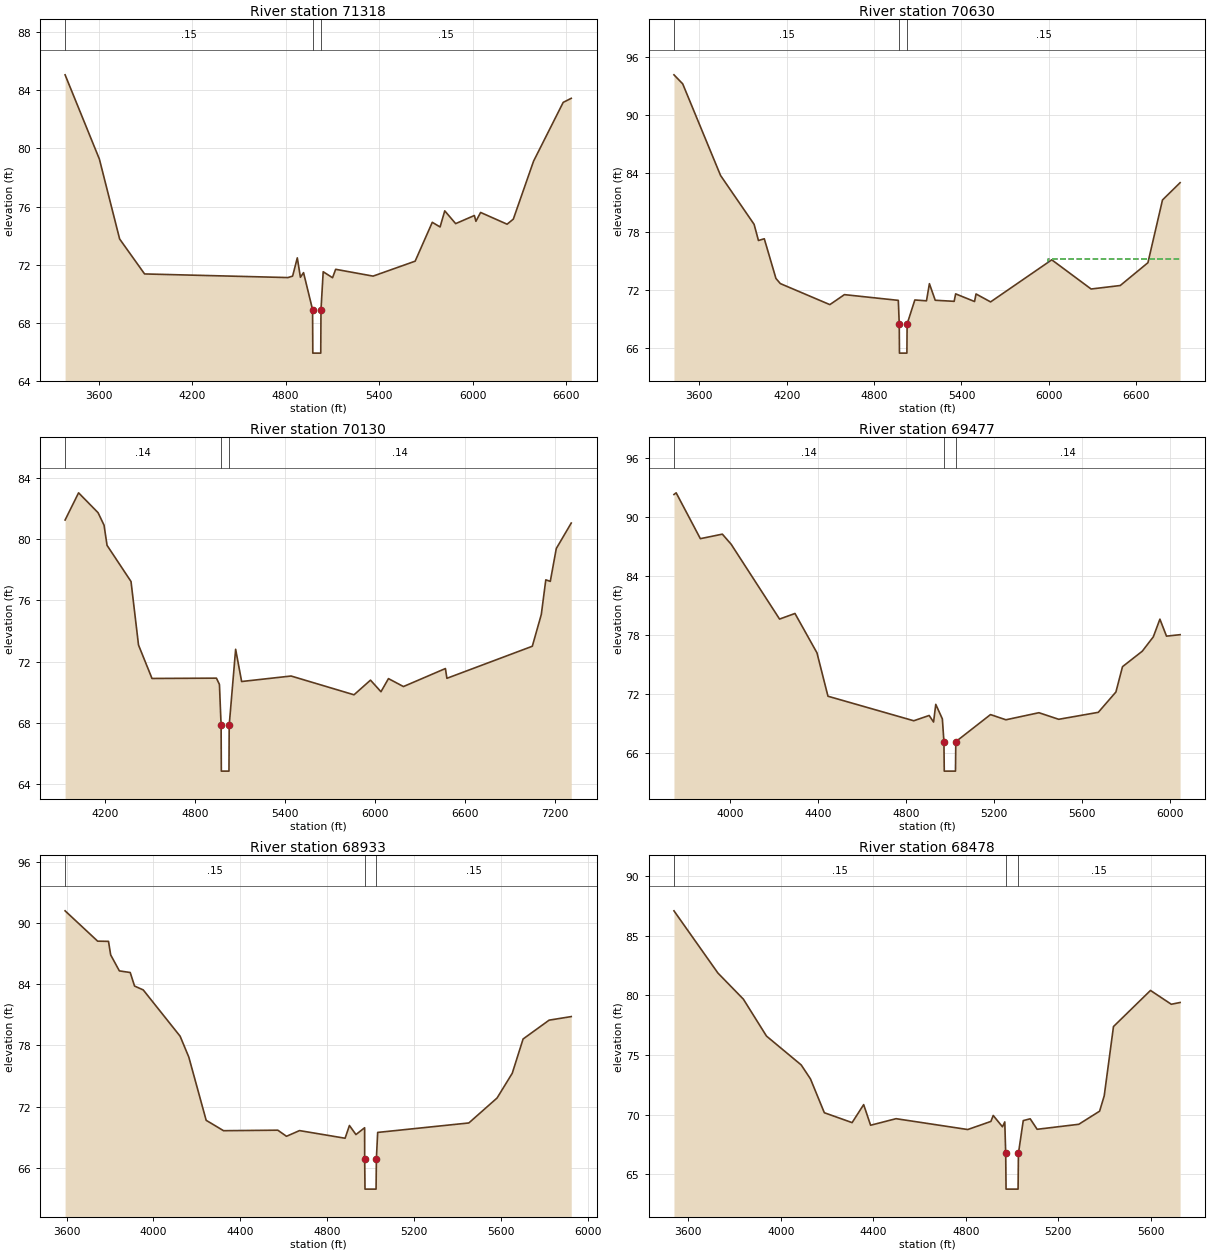
Type RM Length L Ch R = 1 ,71318   ,688,688,688
BEGIN DESCRIPTION:
Indian Field Swamp 142.0
END DESCRIPTION:
XS GIS Cut Line= 3
      2145724.45       507593.74      2144582.68       506449.83
      2143425.74       505299.38
#Sta/Elev= 30
    3385   85.08    3605   79.27    3735   73.76    3895   71.35    4815    71.1
    4845    71.2    4875   72.46    4895   71.12    4915   71.44    4973   68.89
  4974.5   65.89  5025.5   65.89    5027   68.89  5041.2    71.5  5101.2   71.09
  5121.2   71.67  5361.2    71.2  5631.2   72.23  5741.2   74.91  5791.2   74.59
  5821.2    75.7  5891.2   74.82  6011.2   75.38  6021.2   74.98  6051.2   75.59
  6221.2   74.78  6261.2   75.13  6391.2   79.13  6581.2   83.18  6632.8   83.46
#Mann= 3 ,-1,0
    3385     .15       0    4973    .045       0    5027     .15       0
Bank Sta=4973,5027
XS Rating Curve= 0 ,0
Exp/Cntr=0.3,0.1

Type RM Length L Ch R = 1 ,70630   ,500,500,500
BEGIN DESCRIPTION:
Indian Field Swamp 141.0
END DESCRIPTION:
XS GIS Cut Line= 3
      2146302.38       507246.12       2145190.5       506132.88
       2143843.7        504791.4
#Sta/Elev= 30
  3426.6   94.17  3486.6   93.24  3746.6   83.79  3976.6   78.76  4006.6   77.09
  4046.6   77.27  4126.6   73.18  4156.6   72.65  4496.6   70.48  4596.6   71.51
  4966.6   70.92    4973   68.48  4974.5   65.48  5025.5   65.48    5027   68.48
    5080   70.96    5160   70.87    5180   72.64    5220   70.93    5350   70.82
    5360   71.59    5490    70.8    5500   71.58    5600   70.76    6020    75.1
    6290   72.09    6490   72.45    6680    74.8    6780   81.27  6900.9   83.05
#Mann= 3 ,-1,0
  3426.6     .15       0    4973    .045       0    5027     .15       0
#XS Ineff= 2 , 0
          4008.9   75.19  5991.1           75.19
Permanent Ineff=
       F       F
Bank Sta=4973,5027
XS Rating Curve= 0 ,0
Exp/Cntr=0.3,0.1

Type RM Length L Ch R = 1 ,70130   ,653,653,653
BEGIN DESCRIPTION:
Indian Field Swamp 140.0
END DESCRIPTION:
XS GIS Cut Line= 3
      2146430.94       506616.29      2145629.16       505910.46
      2143996.21       504276.86
#Sta/Elev= 30
  3931.8   81.27  4021.8   83.05  4151.8   81.75  4191.8   80.93  4211.8   79.61
  4371.8   77.24  4421.8   73.08  4511.8   70.89  4941.8   70.91  4961.8    70.5
    4973   67.82  4974.5   64.82  5025.5   64.82    5027   67.82    5070    72.8
    5110   70.69    5440   71.05    5860   69.82    5970   70.78    6040   70.02
    6090   70.88    6190   70.36    6470   71.54    6480    70.9    7050      73
    7110   75.08    7140   77.35    7170   77.25    7210    79.4  7309.8   81.07
#Mann= 3 ,-1,0
  3931.8     .14       0    4973    .045       0    5027     .14       0
Bank Sta=4973,5027
XS Rating Curve= 0 ,0
Exp/Cntr=0.3,0.1

Type RM Length L Ch R = 1 ,69477   ,543,543,543
BEGIN DESCRIPTION:
Indian Field Swamp 139.0
END DESCRIPTION:
XS GIS Cut Line= 3
      2146754.28       506298.83      2145917.67       505344.97
      2145242.11       504565.04
#Sta/Elev= 30
  3745.9   92.29  3755.9   92.46  3865.9   87.79  3965.9   88.25  4005.9   87.22
  4225.9    79.6  4295.9   80.17  4395.9   76.16  4445.9   71.74  4835.9   69.24
  4905.9   69.78  4925.9   69.11  4935.9   70.91  4965.9   69.43    4973   67.11
  4974.5   64.11  5025.5   64.11    5027   67.11  5184.7   69.87  5254.7   69.34
  5404.7   70.06  5494.7   69.39  5674.7    70.1  5754.7   72.17  5784.7   74.75
  5874.7   76.33  5924.7   77.79  5954.7   79.59  5984.7   77.86  6046.5   78.01
#Mann= 3 ,-1,0
  3745.9     .14       0    4973    .045       0    5027     .14       0
Bank Sta=4973,5027
XS Rating Curve= 0 ,0
Exp/Cntr=0.3,0.1

Type RM Length L Ch R = 1 ,68933   ,456,456,456
BEGIN DESCRIPTION:
Indian Field Swamp 138.0
END DESCRIPTION:
XS GIS Cut Line= 3
      2146993.26       505990.29      2146154.62       504869.21
      2145581.02       504134.82
#Sta/Elev= 30
  3592.8   91.23  3742.8   88.25  3792.8   88.23  3802.8    86.9  3842.8   85.33
  3892.8   85.17  3912.8   83.84  3952.8   83.46  4122.8   78.91  4162.8   76.86
  4242.8   70.65  4322.8   69.63  4572.8   69.68  4612.8   69.08  4672.8   69.64
  4882.8   68.89  4902.8   70.14  4932.8   69.25  4972.8   69.92    4973   66.89
  4974.5   63.89  5025.5   63.89    5027   66.89  5032.9   69.46  5452.9   70.39
  5582.9   72.84  5652.9   75.27  5702.9   78.64  5822.9   80.49  5924.7   80.84
#Mann= 3 ,-1,0
  3592.8     .15       0    4973    .045       0    5027     .15       0
Bank Sta=4973,5027
XS Rating Curve= 0 ,0
Exp/Cntr=0.3,0.1

Type RM Length L Ch R = 1 ,68478   ,450,450,450
BEGIN DESCRIPTION:
Indian Field Swamp 137.0
END DESCRIPTION:
XS GIS Cut Line= 3
      2147336.53       505777.36       2146497.9       504582.42
      2146085.07       503982.73
#Sta/Elev= 30
  3538.5    87.1  3728.5   81.88  3838.5   79.69  3938.5   76.59  4088.5   74.17
  4128.5      73  4188.5   70.16  4308.5   69.33  4358.5   70.84  4388.5   69.11
  4498.5   69.66  4808.5   68.75  4908.5   69.43  4918.5   69.93  4958.5   68.98
  4968.5   69.39  4972.5   66.75    4974   63.75    5026   63.75  5027.5   66.75
  5048.4    69.5  5078.4   69.65  5108.4   68.77  5288.4   69.19  5378.4   70.29
  5398.4   71.58  5438.4   77.39  5598.4   80.42  5688.4   79.26  5726.4   79.41
#Mann= 3 ,-1,0
  3538.5     .15       0  4972.5    .045       0  5027.5     .15       0
Bank Sta=4972.5,5027.5
XS Rating Curve= 0 ,0
Exp/Cntr=0.3,0.1

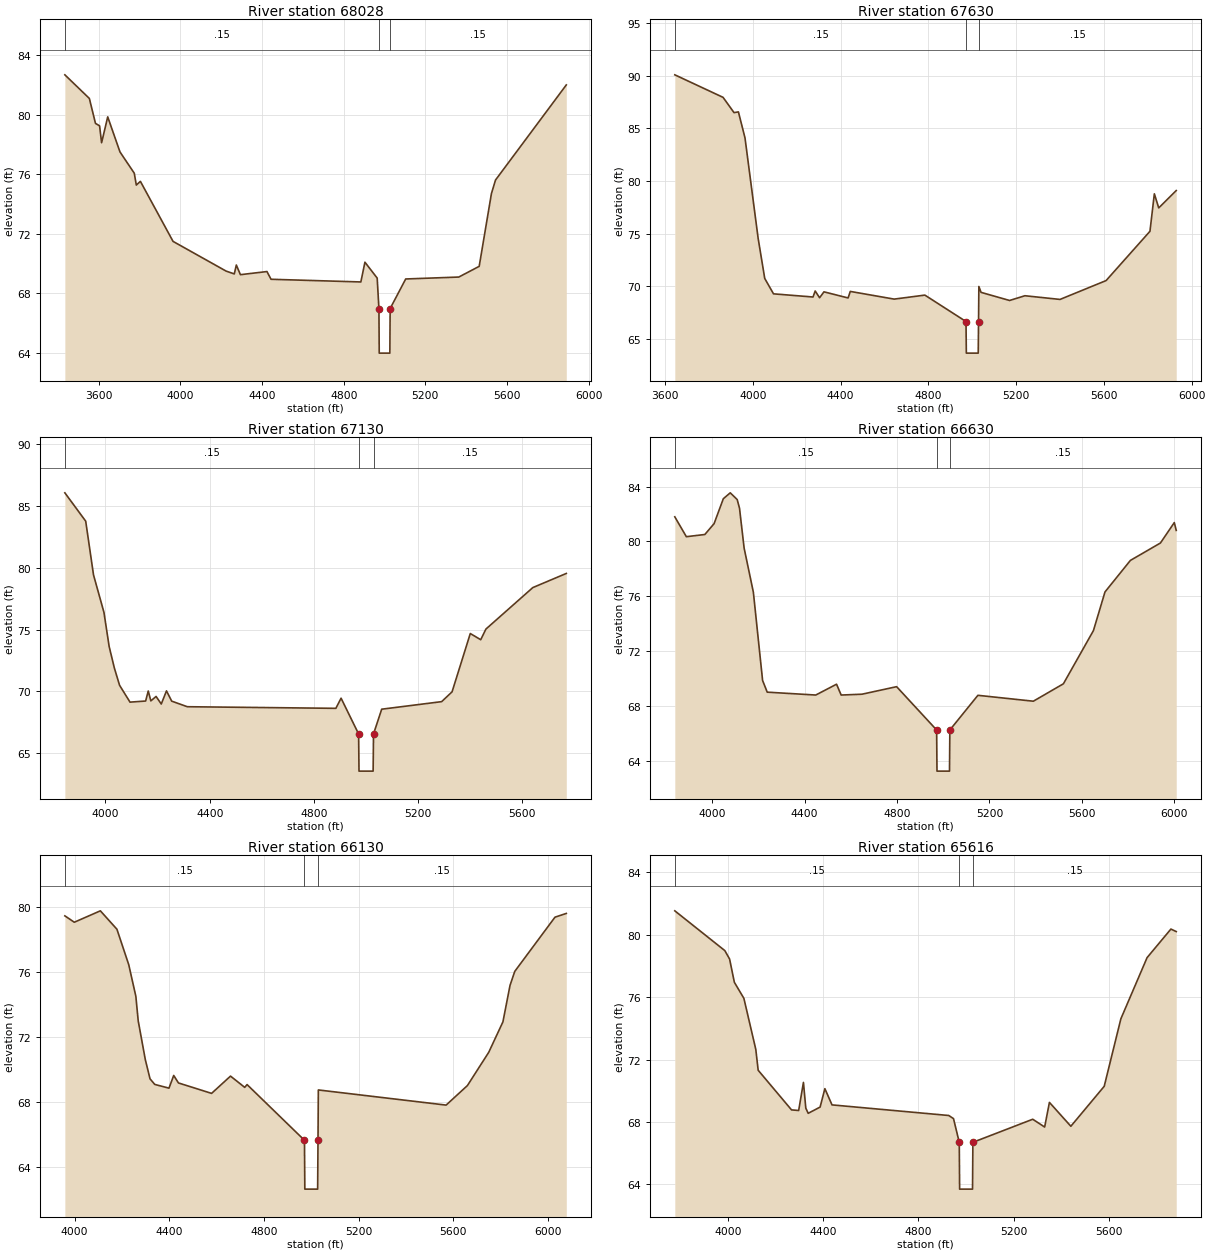
Type RM Length L Ch R = 1 ,68028   ,398,398,398
BEGIN DESCRIPTION:
Indian Field Swamp 136.0
END DESCRIPTION:
XS GIS Cut Line= 3
      2147697.45       505706.82      2146883.16       504364.84
      2146254.59       503739.45
#Sta/Elev= 30
    3434   82.69    3554    81.1    3584   79.42    3604   79.26    3614   78.12
    3644   79.86    3704    77.5    3774   76.07    3784   75.27    3804   75.52
    3964   71.48    4224   69.48    4264   69.29    4274   69.89    4294   69.24
    4424   69.45    4444   68.93    4884   68.75    4904   70.08    4964   69.01
  4972.5   66.96    4974   63.96    5026   63.96  5027.5   66.96  5103.7   68.95
  5363.7   69.08  5463.7    69.8  5523.7    74.7  5543.7   75.61  5890.4   82.01
#Mann= 3 ,-1,0
    3434     .15       0  4972.5    .045       0  5027.5     .15       0
Bank Sta=4972.5,5027.5
XS Rating Curve= 0 ,0
Exp/Cntr=0.3,0.1

Type RM Length L Ch R = 1 ,67630   ,500,500,500
BEGIN DESCRIPTION:
Indian Field Swamp 135.0
END DESCRIPTION:
XS GIS Cut Line= 3
       2148379.8       504724.22       2147168.9       504113.72
      2146393.64       503600.39
#Sta/Elev= 30
  3643.9   90.08  3863.9   87.94  3913.9   86.49  3933.9   86.56  3963.9   84.09
  4023.9   74.54  4053.9   70.74  4093.9   69.28  4273.9   68.98  4283.9   69.55
  4303.9   68.91  4323.9   69.47  4433.9   68.89  4443.9   69.51  4643.9   68.78
  4783.9   69.16  4971.4   66.65  4972.9   63.65  5027.1   63.65  5028.6   66.65
    5030   69.98    5040   69.42    5170   68.65    5240    69.1    5400   68.75
    5610   70.54    5810   75.22    5830   78.78    5850   77.44  5929.8   79.09
#Mann= 3 ,-1,0
  3643.9     .15       0  4971.4    .045       0  5028.6     .15       0
Bank Sta=4971.4,5028.6
XS Rating Curve= 0 ,0
Exp/Cntr=0.3,0.1

Type RM Length L Ch R = 1 ,67130   ,500,500,500
BEGIN DESCRIPTION:
Indian Field Swamp 134.0
END DESCRIPTION:
XS GIS Cut Line= 3
      2148374.84       504262.53      2147385.85       503664.19
      2146731.11       503262.01
#Sta/Elev= 30
  3844.1   86.04  3924.1   83.75  3954.1   79.41  3994.1   76.39  4014.1   73.63
  4034.1   71.89  4054.1    70.5  4094.1   69.14  4154.1   69.23  4164.1   70.04
  4174.1   69.24  4194.1    69.6  4214.1   68.99  4234.1   70.05  4254.1   69.22
  4314.1   68.77  4884.1   68.64  4904.1   69.46  4971.4   66.57  4972.9   63.57
  5027.1   63.57  5028.6   66.57    5060   68.57    5290   69.18    5330   69.97
    5400   74.68    5440   74.18    5460   75.04    5640   78.39  5768.4   79.53
#Mann= 3 ,-1,0
  3844.1     .15       0  4971.4    .045       0  5028.6     .15       0
Bank Sta=4971.4,5028.6
XS Rating Curve= 0 ,0
Exp/Cntr=0.3,0.1

Type RM Length L Ch R = 1 ,66630   ,500,500,500
BEGIN DESCRIPTION:
Indian Field Swamp 133.0
END DESCRIPTION:
XS GIS Cut Line= 3
      2148614.11       503887.19      2147649.57       503239.55
       2146797.8       502699.77
#Sta/Elev= 30
  3838.2    81.8  3888.2   80.35  3968.2   80.51  4008.2    81.3  4048.2   83.12
  4078.2   83.55  4108.2   83.06  4118.2   82.43  4138.2   79.52  4178.2    76.3
  4218.2   69.86  4238.2   69.01  4448.2    68.8  4538.2   69.59  4558.2    68.8
  4648.2   68.86  4798.2   69.41  4971.4   66.25  4972.9   63.25  5027.1   63.25
  5028.6   66.25    5150   68.78    5390   68.35    5520   69.62    5650    73.5
    5700   76.32    5810   78.62    5940   79.89    6000   81.38  6008.4   80.81
#Mann= 3 ,-1,0
  3838.2     .15       0  4971.4    .045       0  5028.6     .15       0
Bank Sta=4971.4,5028.6
XS Rating Curve= 0 ,0
Exp/Cntr=0.3,0.1

Type RM Length L Ch R = 1 ,66130   ,513,513,513
BEGIN DESCRIPTION:
Indian Field Swamp 132.0
END DESCRIPTION:
XS GIS Cut Line= 3
      2148641.71       503647.94      2147967.78        502854.4
      2147264.72       502037.48
#Sta/Elev= 30
  3958.9   79.45  3998.9   79.06  4108.9   79.76  4178.9   78.63  4228.9   76.45
  4258.9   74.51  4268.9      73  4298.9   70.62  4318.9   69.44  4338.9    69.1
  4398.9   68.87  4418.9   69.65  4438.9   69.19  4578.9   68.55  4658.9   69.61
  4718.9   68.92  4728.9   69.09  4971.4   65.67  4972.9   62.67  5027.1   62.67
  5028.6   65.67    5030   68.76    5570   67.83    5660   69.03    5750   71.07
    5810   72.94    5840   75.18    5860   76.04    6030   79.37  6077.8    79.6
#Mann= 3 ,-1,0
  3958.9     .15       0  4971.4    .045       0  5028.6     .15       0
Bank Sta=4971.4,5028.6
XS Rating Curve= 0 ,0
Exp/Cntr=0.3,0.1

Type RM Length L Ch R = 1 ,65616   ,487,487,487
BEGIN DESCRIPTION:
Indian Field Swamp 131.0
END DESCRIPTION:
XS GIS Cut Line= 3
      2148893.83       503600.59       2148343.4       502508.83
      2147783.87       501826.47
#Sta/Elev= 30
  3777.2   81.54  3987.2   78.99  4007.2   78.45  4027.2   76.96  4067.2   75.93
  4117.2   72.66  4127.2   71.32  4267.2   68.78  4297.2   68.74  4317.2   70.54
  4327.2   68.89  4337.2   68.56  4387.2   68.96  4407.2   70.14  4437.2    69.1
  4927.2   68.42  4947.2   68.22  4971.4    66.7  4972.9    63.7  5027.1    63.7
  5028.6    66.7  5279.9   68.18  5329.9   67.68  5349.9   69.26  5439.9   67.73
  5579.9   70.29  5649.9   74.62  5759.9   78.54  5859.9   80.37  5882.3   80.21
#Mann= 3 ,-1,0
  3777.2     .15       0  4971.4    .045       0  5028.6     .15       0
Bank Sta=4971.4,5028.6
XS Rating Curve= 0 ,0
Exp/Cntr=0.3,0.1

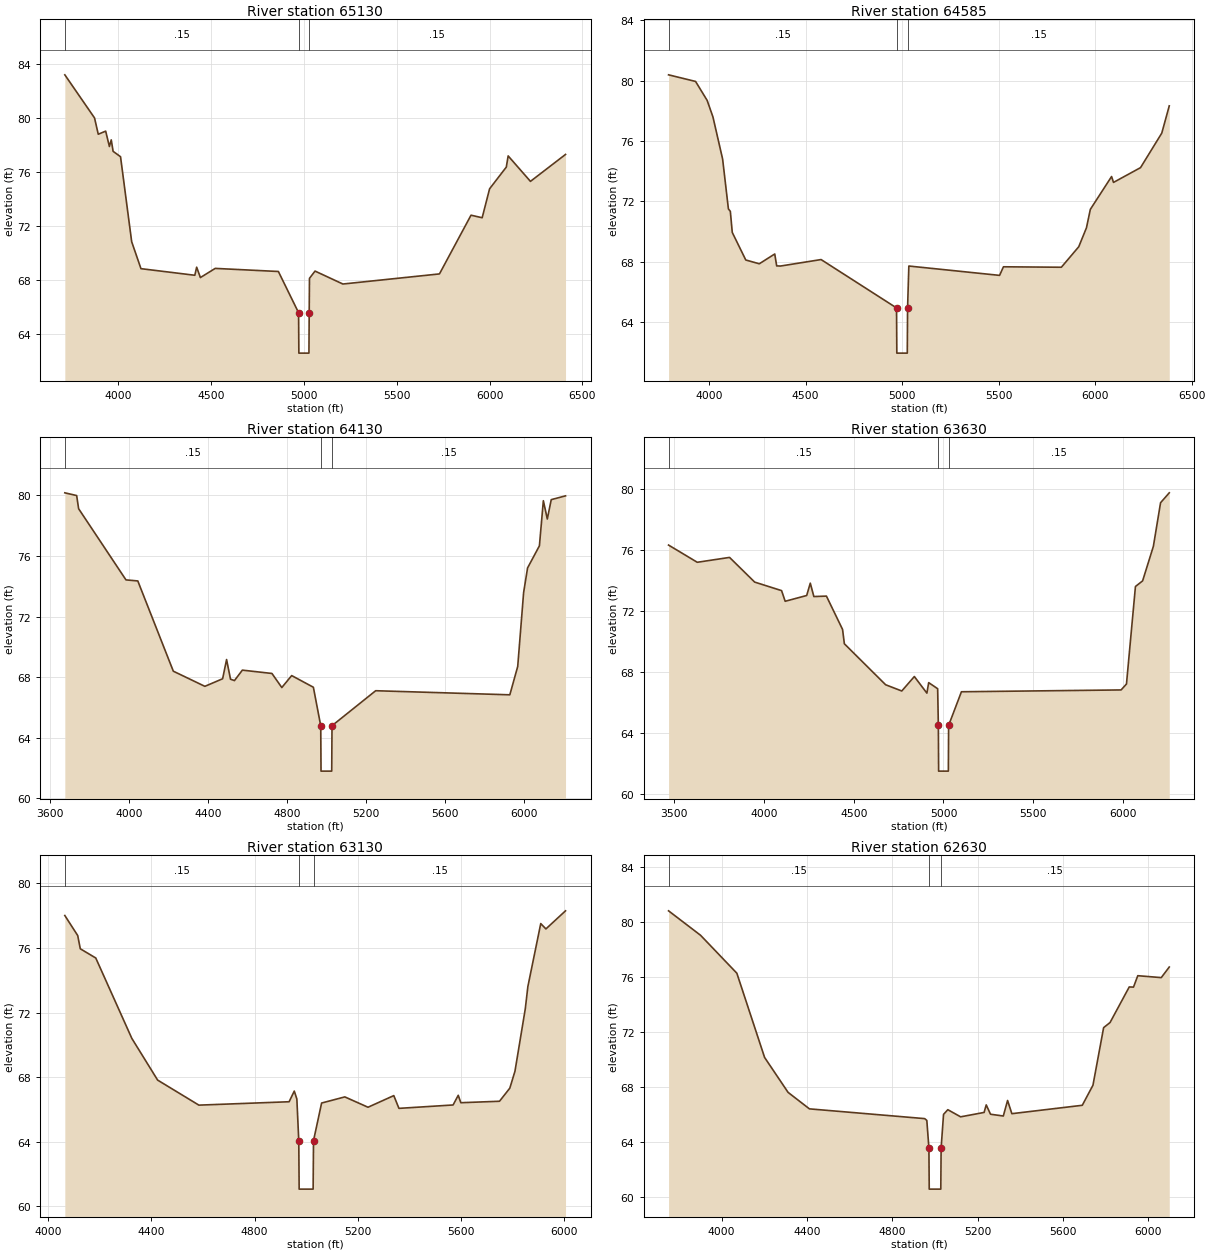
Type RM Length L Ch R = 1 ,65130   ,544,544,544
BEGIN DESCRIPTION:
Indian Field Swamp 130.0
END DESCRIPTION:
XS GIS Cut Line= 3
      2149385.13       503432.29      2148779.12       502296.44
      2148052.26       501089.52
#Sta/Elev= 30
  3712.6   83.23  3872.6   80.03  3892.6   78.82  3932.6   79.05  3952.6   77.91
  3962.6    78.4  3972.6   77.55  4012.6   77.15  4072.6   70.84  4122.6   68.84
  4412.6   68.35  4422.6   68.95  4442.6   68.18  4522.6   68.86  4862.6   68.63
  4971.4   65.57  4972.9   62.57  5027.1   62.57  5028.6   65.57    5030   68.12
    5060   68.66    5210    67.7    5730   68.45    5900   72.81    5960   72.62
    6000   74.77    6090   76.38    6100   77.21    6220   75.32  6408.9   77.32
#Mann= 3 ,-1,0
  3712.6     .15       0  4971.4    .045       0  5028.6     .15       0
Bank Sta=4971.4,5028.6
XS Rating Curve= 0 ,0
Exp/Cntr=0.3,0.1

Type RM Length L Ch R = 1 ,64585   ,456,456,456
BEGIN DESCRIPTION:
Indian Field Swamp 129.0
END DESCRIPTION:
XS GIS Cut Line= 3
       2149735.4       503209.38      2149278.91       502083.85
      2148598.14       500884.81
#Sta/Elev= 30
  3790.6   80.39  3930.6   79.95  3990.6   78.69  4020.6   77.59  4070.6    74.8
  4100.6   71.49  4110.6   71.33  4120.6   69.93  4190.6    68.1  4260.6   67.85
  4340.6    68.5  4350.6   67.71  4370.6    67.7  4580.6   68.13  4971.4   64.92
  4972.9   61.92  5027.1   61.92  5028.6   64.92  5035.2    67.7  5505.2   67.08
  5525.2   67.65  5825.2   67.62  5915.2   68.98  5955.2   70.24  5975.2   71.46
  6085.2   73.64  6095.2   73.25  6235.2   74.23  6345.2   76.52    6384   78.33
#Mann= 3 ,-1,0
  3790.6     .15       0  4971.4    .045       0  5028.6     .15       0
Bank Sta=4971.4,5028.6
XS Rating Curve= 0 ,0
Exp/Cntr=0.3,0.1

Type RM Length L Ch R = 1 ,64130   ,500,500,500
BEGIN DESCRIPTION:
Indian Field Swamp 128.0
END DESCRIPTION:
XS GIS Cut Line= 3
      2150094.91       503281.09      2149713.48       502011.24
      2149399.54       500840.19
#Sta/Elev= 30
  3674.1   80.17  3734.1   79.99  3744.1   79.12  3984.1   74.42  4044.1   74.35
  4224.1   68.39  4384.1   67.39  4474.1   67.89  4494.1   69.16  4514.1   67.86
  4534.1   67.77  4574.1   68.46  4724.1   68.24  4774.1   67.31  4824.1    68.1
  4934.1   67.33  4971.4   64.79  4972.9   61.79  5027.1   61.79  5028.6   64.79
    5250    67.1    5930   66.83    5970    68.7    6000   73.59    6020   75.21
    6080   76.67    6100   79.65    6120   78.44    6140   79.72  6212.4   79.97
#Mann= 3 ,-1,0
  3674.1     .15       0  4971.4    .045       0  5028.6     .15       0
Bank Sta=4971.4,5028.6
XS Rating Curve= 0 ,0
Exp/Cntr=0.3,0.1

Type RM Length L Ch R = 1 ,63630   ,500,500,500
BEGIN DESCRIPTION:
Indian Field Swamp 127.0
END DESCRIPTION:
XS GIS Cut Line= 3
      2150981.14       503166.74      2150179.74       501860.48
      2149504.11       500798.72
#Sta/Elev= 30
  3467.5   76.33  3627.5    75.2  3807.5   75.52  3947.5    73.9  4097.5   73.34
  4117.5   72.64  4237.5   73.02  4257.5   73.83  4277.5   72.95  4347.5   72.98
  4437.5   70.79  4447.5   69.85  4677.5   67.16  4767.5   66.75  4837.5    67.7
  4907.5   66.61  4917.5    67.3  4967.5    66.9  4971.4   64.49  4972.9   61.49
  5027.1   61.49  5028.6   64.49    5100    66.7    5990   66.82    6020   67.21
    6070   73.61    6110   73.98    6170   76.25    6210   79.11  6258.5   79.76
#Mann= 3 ,-1,0
  3467.5     .15       0  4971.4    .045       0  5028.6     .15       0
Bank Sta=4971.4,5028.6
XS Rating Curve= 0 ,0
Exp/Cntr=0.3,0.1

Type RM Length L Ch R = 1 ,63130   ,500,500,500
BEGIN DESCRIPTION:
Indian Field Swamp 126.0
END DESCRIPTION:
XS GIS Cut Line= 3
      2151024.97       502224.96      2150476.24       501466.68
      2149925.02       500625.02
#Sta/Elev= 30
    4064   78.01    4114   76.77    4124   75.95    4184   75.38    4324    70.4
    4424   67.82    4584   66.27    4934   66.48    4954   67.14    4964   66.65
  4971.4   64.07  4972.9   61.07  5027.1   61.07  5028.6   64.07    5060    66.4
    5150   66.78    5240   66.14    5340   66.86    5360   66.07    5570   66.28
    5590   66.88    5600   66.42    5750   66.51    5790   67.32    5810   68.37
    5850   72.23    5860   73.61    5910   77.51    5930   77.18  6006.1    78.3
#Mann= 3 ,-1,0
    4064     .15       0  4971.4    .045       0  5028.6     .15       0
Bank Sta=4971.4,5028.6
XS Rating Curve= 0 ,0
Exp/Cntr=0.3,0.1

Type RM Length L Ch R = 1 ,62630   ,500,500,500
BEGIN DESCRIPTION:
Indian Field Swamp 125.0
END DESCRIPTION:
XS GIS Cut Line= 3
      2151495.69       502061.31      2150757.46       501054.58
      2149980.57       500279.37
#Sta/Elev= 30
  3751.6   80.79  3901.6   79.01  4071.6   76.25  4201.6   70.12  4311.6   67.58
  4411.6   66.38  4951.6   65.67  4961.6   65.54  4971.4   63.54  4972.9   60.54
  5027.1   60.54  5028.6   63.54    5040   65.98    5060   66.32    5120    65.8
    5230   66.12    5240   66.67    5260   65.99    5320   65.86    5340   66.99
    5360   66.03    5690   66.64    5740    68.1    5790   72.29    5820   72.66
    5910   75.25    5930   75.24    5950   76.07    6060   75.93  6097.5    76.7
#Mann= 3 ,-1,0
  3751.6     .15       0  4971.4    .045       0  5028.6     .15       0
Bank Sta=4971.4,5028.6
XS Rating Curve= 0 ,0
Exp/Cntr=0.3,0.1

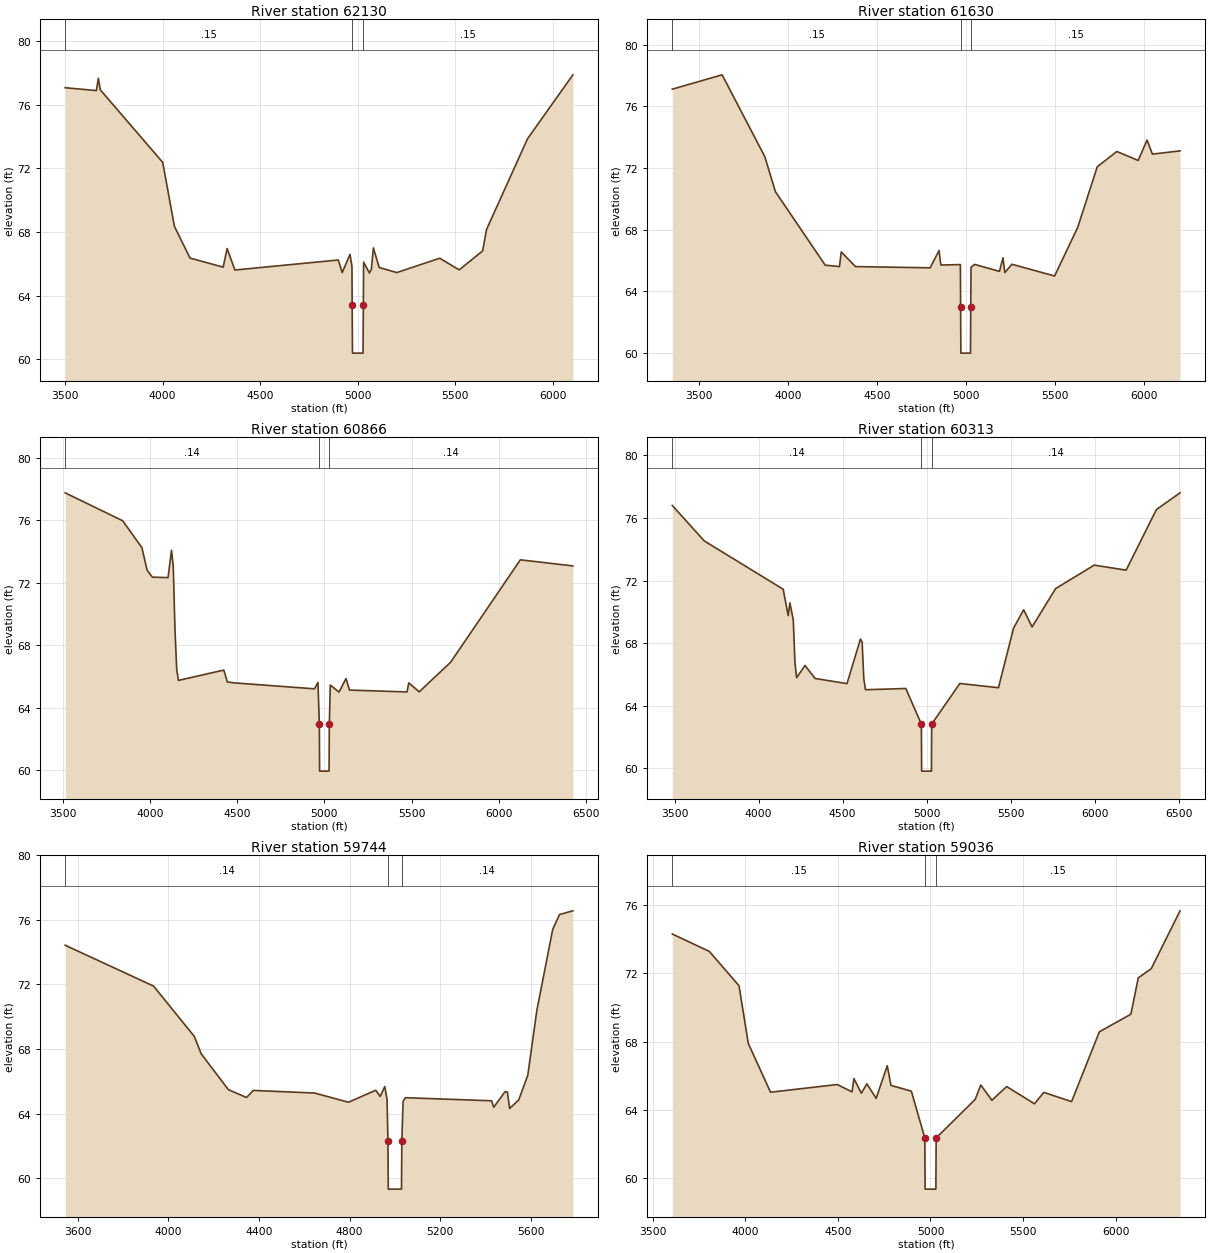
Type RM Length L Ch R = 1 ,62130   ,500,500,500
BEGIN DESCRIPTION:
Indian Field Swamp 124.0
END DESCRIPTION:
XS GIS Cut Line= 3
      2152272.83       501579.79       2151078.3       500673.04
       2150161.6       500060.17
#Sta/Elev= 30
  3500.3   77.07  3660.3   76.89  3670.3   77.66  3680.3   76.94  4000.3   72.38
  4060.3   68.36  4140.3   66.37  4310.3    65.8  4330.3   66.97  4370.3   65.62
  4900.3   66.25  4920.3   65.46  4960.3    66.6  4970.3   65.85  4971.4    63.4
  4972.9    60.4  5027.1    60.4  5028.6    63.4    5030   66.11    5060   65.43
    5070   65.68    5080   67.01    5110   65.78    5200   65.46    5420   66.36
    5520   65.63    5640   66.82    5660   68.16    5870   73.86  6102.7   77.88
#Mann= 3 ,-1,0
  3500.3     .15       0  4971.4    .045       0  5028.6     .15       0
Bank Sta=4971.4,5028.6
XS Rating Curve= 0 ,0
Exp/Cntr=0.3,0.1

Type RM Length L Ch R = 1 ,61630   ,763,763,763
BEGIN DESCRIPTION:
Indian Field Swamp 123.0
END DESCRIPTION:
XS GIS Cut Line= 3
      2152791.66       501113.15      2151373.85       500269.75
        2150274.       499776.49
#Sta/Elev= 30
  3350.3   77.11  3630.3   78.04  3870.3   72.74  3930.3   70.46  4210.3    65.7
  4290.3   65.61  4300.3   66.56  4380.3   65.61  4800.3   65.53  4850.3   66.65
  4860.3   65.71  4970.3   65.74  4971.4      63  4972.9      60  5027.1      60
  5028.6      63    5030   65.56    5050   65.75    5190    65.3    5210   66.18
    5220   65.22    5260   65.76    5500      65    5630   68.15    5740   72.08
    5850   73.07    5970   72.49    6020   73.81    6050    72.9  6205.4   73.11
#Mann= 3 ,-1,0
  3350.3     .15       0  4971.4    .045       0  5028.6     .15       0
Bank Sta=4971.4,5028.6
XS Rating Curve= 0 ,0
Exp/Cntr=0.3,0.1

Type RM Length L Ch R = 1 ,60866   ,554,554,554
BEGIN DESCRIPTION:
Indian Field Swamp 122.0
END DESCRIPTION:
XS GIS Cut Line= 3
       2152948.9       500512.82      2151770.56       499615.95
       2150339.2       499611.36
#Sta/Elev= 30
  3513.5   77.75  3843.5   75.96  3953.5   74.24  3983.5    72.8  4013.5   72.35
  4103.5   72.32  4123.5   74.07  4133.5   73.01  4143.5   68.94  4153.5   66.39
  4163.5   65.74  4423.5    66.4  4443.5   65.64  4483.5   65.58  4943.5    65.2
  4963.5   65.61  4971.4   62.93  4972.9   59.93  5027.1   59.93  5028.6   62.93
  5034.3   65.44  5084.3   64.99  5124.3   65.86  5144.3   65.12  5474.3      65
  5484.3   65.58  5544.3   65.01  5724.3    66.9  6124.3   73.46  6425.7   73.07
#Mann= 3 ,-1,0
  3513.5     .14       0  4971.4    .045       0  5028.6     .14       0
Bank Sta=4971.4,5028.6
XS Rating Curve= 0 ,0
Exp/Cntr=0.3,0.1

Type RM Length L Ch R = 1 ,60313   ,568,568,568
BEGIN DESCRIPTION:
Indian Field Swamp 120.0
END DESCRIPTION:
XS GIS Cut Line= 3
      2153146.27       500376.16      2152150.88       499238.62
      2151134.34        498120.9
#Sta/Elev= 30
  3486.7    76.8  3676.7   74.54  4146.7   71.45  4176.7   69.76  4186.7   70.58
  4206.7   69.49  4216.7   66.77  4226.7    65.8  4276.7   66.58  4336.7   65.75
  4526.7   65.42  4606.7   68.27  4616.7   68.07  4626.7   65.71  4636.7   65.03
  4876.7   65.11  4969.4   62.83  4970.9   59.83  5029.1   59.83  5030.6   62.83
  5198.3   65.43  5428.3   65.16  5518.3   68.97  5578.3   70.14  5628.3   69.04
  5768.3   71.49  5998.3   72.99  6188.3   72.67  6368.3   76.54  6509.1   77.61
#Mann= 3 ,-1,0
  3486.7     .14       0  4969.4    .045       0  5030.6     .14       0
Bank Sta=4969.4,5030.6
XS Rating Curve= 0 ,0
Exp/Cntr=0.3,0.1

Type RM Length L Ch R = 1 ,59744   ,709,709,709
BEGIN DESCRIPTION:
Indian Field Swamp 119.0
END DESCRIPTION:
XS GIS Cut Line= 3
      2153459.13       499902.53      2152507.57       498807.19
      2151937.54       498261.73
#Sta/Elev= 30
  3545.4   74.43  3935.4    71.9  4115.4   68.78  4145.4   67.71  4265.4   65.49
  4345.4      65  4375.4   65.44  4645.4   65.28  4795.4   64.71  4915.4   65.45
  4935.4   65.07  4955.4   65.68  4965.4   64.89  4969.4   62.33  4970.9   59.33
  5029.1   59.33  5030.6   62.33  5036.3   64.77  5046.3   64.99  5426.3    64.8
  5436.3    64.4  5486.3   65.37  5496.3   65.34  5506.3   64.33  5546.3   64.85
  5586.3   66.38  5626.3   70.39  5696.3   75.41  5726.3   76.33  5785.3   76.56
#Mann= 3 ,-1,0
  3545.4     .14       0  4969.4    .045       0  5030.6     .14       0
Bank Sta=4969.4,5030.6
XS Rating Curve= 0 ,0
Exp/Cntr=0.3,0.1

Type RM Length L Ch R = 1 ,59036   ,489,489,489
BEGIN DESCRIPTION:
Indian Field Swamp 118.0
END DESCRIPTION:
XS GIS Cut Line= 3
      2153549.22       499597.98      2152977.49       498325.86
      2151862.54       497573.03
#Sta/Elev= 30
  3606.7   74.31  3806.7   73.29  3966.7   71.28  4016.7    67.9  4136.7   65.04
  4496.7   65.49  4576.7   65.06  4586.7   65.84  4626.7   64.98  4656.7   65.53
  4706.7   64.68  4766.7   66.59  4786.7   65.44  4896.7    65.1  4969.4   62.36
  4970.9   59.36  5029.1   59.36  5030.6   62.36  5241.4   64.62  5271.4   65.46
  5331.4   64.57  5411.4   65.37  5561.4   64.36  5611.4   65.03  5761.4   64.49
  5911.4   68.58  6081.4   69.61  6121.4   71.74  6191.4   72.28  6346.7   75.67
#Mann= 3 ,-1,0
  3606.7     .15       0  4969.4    .045       0  5030.6     .15       0
Bank Sta=4969.4,5030.6
XS Rating Curve= 0 ,0
Exp/Cntr=0.3,0.1

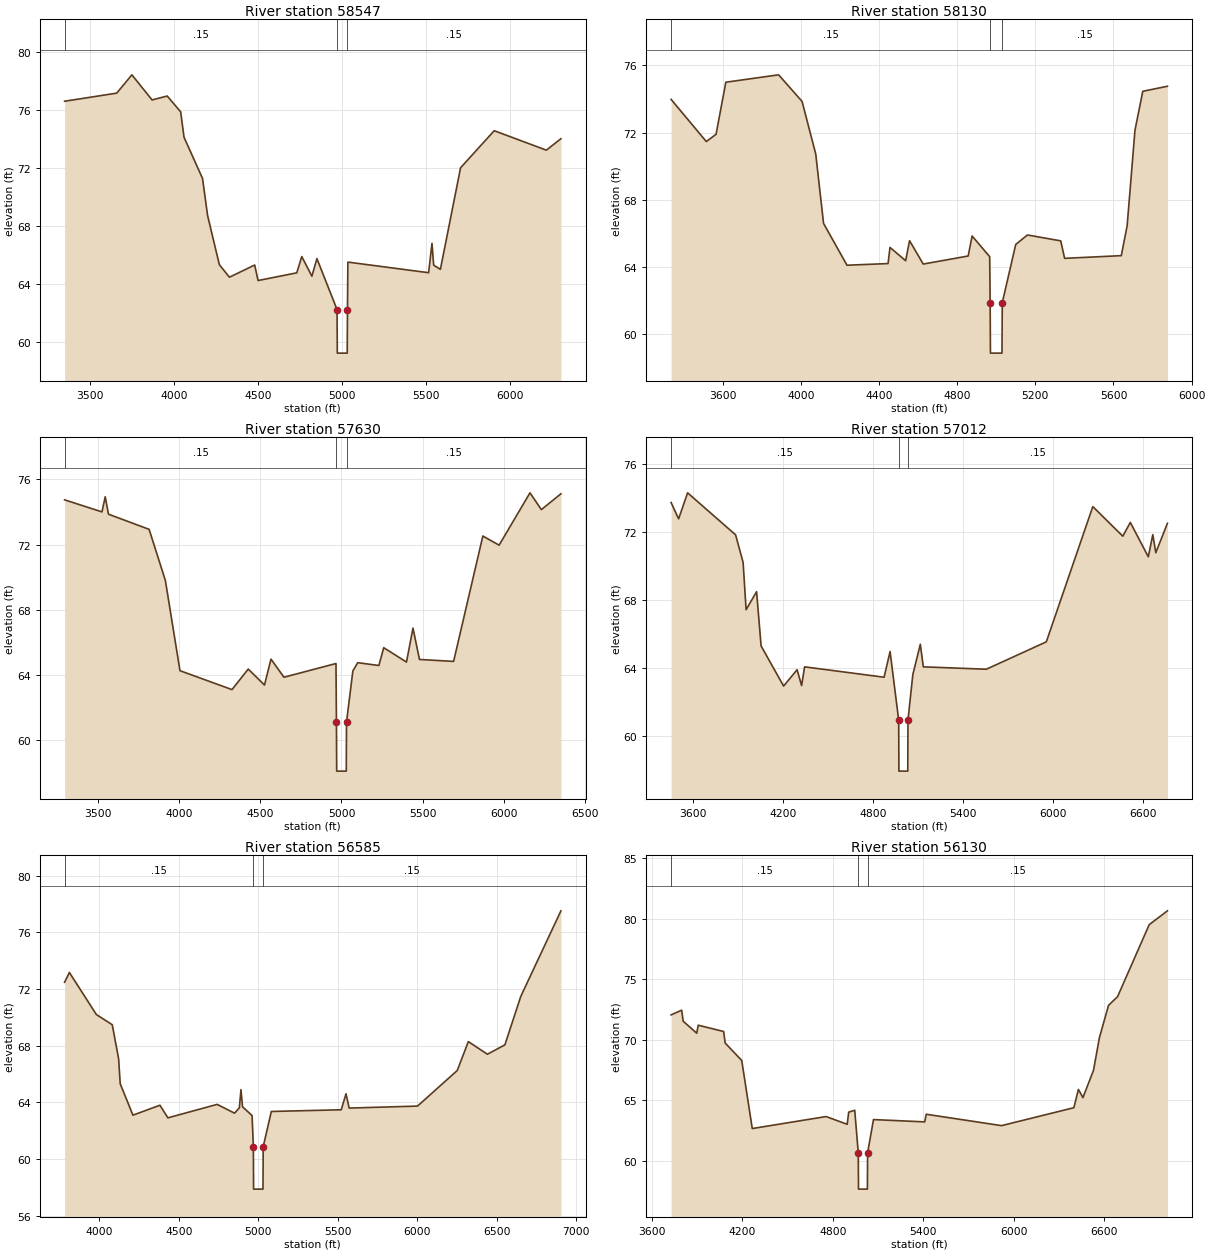
Type RM Length L Ch R = 1 ,58547   ,417,417,417
BEGIN DESCRIPTION:
Indian Field Swamp 117.0
END DESCRIPTION:
XS GIS Cut Line= 3
      2154636.68       498742.29      2153209.58       497906.18
      2152093.11       497247.08
#Sta/Elev= 30
  3349.4   76.59  3659.4   77.15  3749.4   78.41  3869.4   76.68  3959.4   76.95
  4039.4   75.86  4059.4   74.11  4169.4   71.27  4199.4   68.72  4269.4   65.33
  4329.4   64.47  4479.4   65.31  4499.4   64.24  4729.4   64.77  4759.4   65.89
  4819.4   64.54  4849.4   65.75    4969   62.24  4970.5   59.24  5029.5   59.24
    5031   62.24  5033.4   65.51  5513.4   64.78  5533.4    66.8  5543.4    65.3
  5583.4   65.01  5703.4   72.01  5903.4   74.56  6213.4   73.22  6299.9   74.01
#Mann= 3 ,-1,0
  3349.4     .15       0    4969    .045       0    5031     .15       0
Bank Sta=4969,5031
XS Rating Curve= 0 ,0
Exp/Cntr=0.3,0.1

Type RM Length L Ch R = 1 ,58130   ,500,500,500
BEGIN DESCRIPTION:
Indian Field Swamp 116.0
END DESCRIPTION:
XS GIS Cut Line= 3
      2154845.23       498311.58      2153378.99       497526.06
      2152577.01       497173.64
#Sta/Elev= 30
  3336.6   73.98  3516.6   71.47  3566.6    71.9  3616.6      75  3886.6   75.44
  4006.6   73.86  4076.6   70.73  4116.6    66.6  4236.6   64.11  4446.6   64.21
  4456.6   65.17  4536.6   64.38  4556.6   65.57  4626.6   64.18  4856.6   64.66
  4876.6   65.85  4966.6   64.62    4969   61.88  4970.5   58.88  5029.5   58.88
    5031   61.88    5100   65.35    5160   65.91    5330   65.56    5350   64.52
    5640   64.68    5670   66.47    5710   72.15    5750   74.46    5876   74.76
#Mann= 3 ,-1,0
  3336.6     .15       0    4969    .045       0    5031     .15       0
Bank Sta=4969,5031
XS Rating Curve= 0 ,0
Exp/Cntr=0.3,0.1

Type RM Length L Ch R = 1 ,57630   ,617,617,617
BEGIN DESCRIPTION:
Indian Field Swamp 115.0
END DESCRIPTION:
XS GIS Cut Line= 3
      2155269.43       497279.35      2153578.82       497067.73
      2152242.41       496873.81
#Sta/Elev= 30
  3296.2   74.74  3526.2      74  3546.2   74.93  3566.2   73.86  3816.2   72.93
  3916.2    69.8  4006.2   64.26  4326.2    63.1  4426.2   64.36  4526.2   63.38
  4566.2   64.97  4646.2   63.86  4966.2    64.7    4969    61.1  4970.5    58.1
  5029.5    58.1    5031    61.1    5070   64.24    5100   64.75    5230   64.58
    5260   65.67    5400   64.79    5440   66.87    5480   64.95    5690   64.83
    5870   72.52    5970   71.96    6160   75.17    6230   74.14  6350.4   75.11
#Mann= 3 ,-1,0
  3296.2     .15       0    4969    .045       0    5031     .15       0
Bank Sta=4969,5031
XS Rating Curve= 0 ,0
Exp/Cntr=0.3,0.1

Type RM Length L Ch R = 1 ,57012   ,428,428,428
BEGIN DESCRIPTION:
Indian Field Swamp 114.0
END DESCRIPTION:
XS GIS Cut Line= 3
       2155335.8       496628.88      2153800.04       496494.89
      2152039.23       496341.26
#Sta/Elev= 30
  3451.7   73.72  3501.7   72.76  3561.7   74.29  3881.7   71.82  3931.7    70.2
  3951.7   67.42  4021.7   68.48  4051.7   65.29  4201.7   62.93  4291.7   63.89
  4321.7   62.96  4341.7   64.06  4871.7   63.45  4911.7   64.96    4969   60.93
  4970.5   57.93  5029.5   57.93    5031   60.93  5063.3    63.6  5113.3   65.39
  5133.3   64.06  5553.3   63.92  5953.3   65.53  6263.3   73.48  6463.3   71.74
  6513.3   72.55  6633.3   70.53  6663.3   71.83  6683.3   70.77  6760.8    72.5
#Mann= 3 ,-1,0
  3451.7     .15       0    4969    .045       0    5031     .15       0
Bank Sta=4969,5031
XS Rating Curve= 0 ,0
Exp/Cntr=0.3,0.1

Type RM Length L Ch R = 1 ,56585   ,455,455,455
BEGIN DESCRIPTION:
Indian Field Swamp 113.0
END DESCRIPTION:
XS GIS Cut Line= 3
      2155026.05       496062.49      2153804.75       496066.92
      2151902.06       496062.49
#Sta/Elev= 30
  3780.9   72.47  3810.9   73.16  3980.9   70.19  4080.9   69.47  4120.9   67.07
  4130.9   65.31  4210.9   63.09  4380.9   63.79  4430.9    62.9  4740.9   63.85
  4850.9   63.23  4880.9   63.61  4890.9   64.89  4900.9   63.68  4960.9   63.06
    4969   60.87  4970.5   57.87  5029.5   57.87    5031   60.87  5082.2   63.35
  5522.2   63.47  5552.2    64.6  5572.2   63.59  6002.2   63.73  6252.2   66.24
  6322.2   68.28  6442.2   67.39  6552.2   68.05  6652.2   71.47  6904.9   77.51
#Mann= 3 ,-1,0
  3780.9     .15       0    4969    .045       0    5031     .15       0
Bank Sta=4969,5031
XS Rating Curve= 0 ,0
Exp/Cntr=0.3,0.1

Type RM Length L Ch R = 1 ,56130   ,500,500,500
BEGIN DESCRIPTION:
Indian Field Swamp 112.0
END DESCRIPTION:
XS GIS Cut Line= 4
      2154954.97       495887.31      2154755.89       495613.27
      2153821.41       495612.37      2151800.61        495614.8
#Sta/Elev= 30
  3726.8   72.06  3796.8   72.45  3806.8   71.54  3896.8   70.55  3906.8   71.21
  4075.5   70.69  4085.5   69.74  4195.5    68.3  4265.5   62.68  4755.5   63.67
  4895.5   63.03  4905.5   64.03  4945.5   64.19    4969   60.68  4970.5   57.68
  5029.5   57.68    5031   60.68    5070   63.42    5410   63.23    5420   63.86
    5920   62.92    6400    64.4    6430   65.91    6460   65.23    6530   67.48
    6570   70.21    6630   72.85    6690   73.57    6900   79.51  7020.8   80.65
#Mann= 3 ,-1,0
  3726.8     .15       0    4969    .045       0    5031     .15       0
Bank Sta=4969,5031
XS Rating Curve= 0 ,0
Exp/Cntr=0.3,0.1

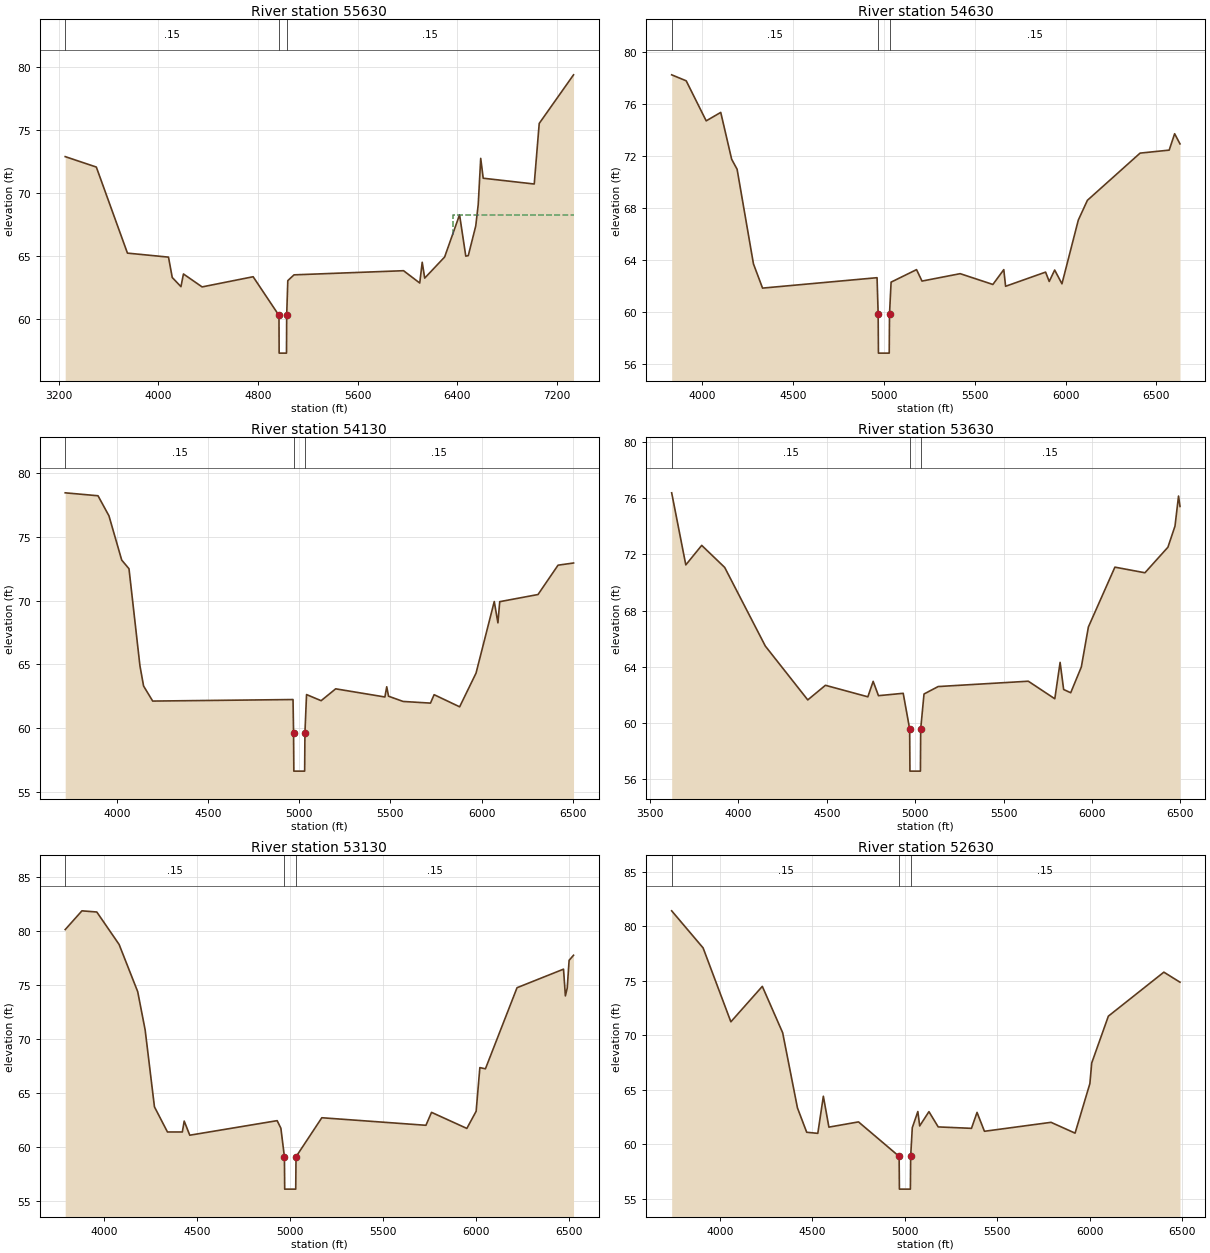
Type RM Length L Ch R = 1 ,55630   ,500,500,500
BEGIN DESCRIPTION:
Indian Field Swamp 111.0
END DESCRIPTION:
XS GIS Cut Line= 3
      2155543.72       495115.56      2153795.22       495114.74
      2151459.52       495115.56
#Sta/Elev= 30
  3251.5    72.9  3501.5   72.07  3751.5   65.22  4081.5    64.9  4111.5   63.28
  4181.5   62.55  4201.5   63.56  4351.5   62.53  4761.5   63.34    4969   60.26
  4970.5   57.26  5029.5   57.26    5031   60.26    5040   63.03    5090   63.49
    5970   63.82    6100   62.84    6120   64.49    6140   63.23    6300   64.91
    6420   68.27    6470   64.98    6490   65.02    6550   67.38    6570   69.09
    6590   72.76    6610   71.18    7020   70.72    7060   75.54  7335.7   79.41
#Mann= 3 ,-1,0
  3251.5     .15       0    4969    .045       0    5031     .15       0
#XS Ineff= 2 , 0
          3636.1   68.22  6363.9           68.22
Permanent Ineff=
       F       F
Bank Sta=4969,5031
XS Rating Curve= 0 ,0
Exp/Cntr=0.3,0.1

Type RM Length L Ch R = 1 ,54630   ,500,500,500
BEGIN DESCRIPTION:
Indian Field Swamp 109.0
END DESCRIPTION:
XS GIS Cut Line= 3
      2154830.88       494123.48      2153663.58       494123.44
      2152034.08       494123.48
#Sta/Elev= 30
  3832.7   78.26  3912.7    77.8  4022.7   74.72  4102.7   75.37  4162.7   71.77
  4192.7      71  4282.7   63.72  4332.7   61.86  4962.7   62.66  4968.8   59.86
  4970.3   56.86  5029.7   56.86  5031.2   59.86    5040   62.32    5180   63.28
    5210    62.4    5420   62.97    5600   62.14    5660   63.28    5670      62
    5890   63.09    5910   62.37    5940   63.25    5980   62.19    6070   67.09
    6120   68.61    6410   72.24    6570   72.47    6600   73.73  6629.5   72.95
#Mann= 3 ,-1,0
  3832.7     .15       0  4968.8    .045       0  5031.2     .15       0
Bank Sta=4968.8,5031.2
XS Rating Curve= 0 ,0
Exp/Cntr=0.3,0.1

Type RM Length L Ch R = 1 ,54130   ,500,500,500
BEGIN DESCRIPTION:
Indian Field Swamp 108.0
END DESCRIPTION:
XS GIS Cut Line= 3
      2154869.05        493446.9      2153597.75       493627.79
      2152105.61        493823.3
#Sta/Elev= 30
  3715.9   78.45  3895.9   78.22  3955.9   76.65  4025.9   73.18  4065.9    72.5
  4125.9    64.9  4145.9   63.31  4195.9   62.13  4965.9   62.25  4968.8   59.64
  4970.3   56.64  5029.7   56.64  5031.2   59.64    5040   62.64    5120   62.16
    5200   63.09    5470   62.45    5480   63.25    5490   62.51    5570    62.1
    5720   61.97    5740   62.63    5880   61.68    5970   64.32    6070   69.93
    6090   68.26    6100   69.92    6310   70.48    6420   72.78  6504.9   72.95
#Mann= 3 ,-1,0
  3715.9     .15       0  4968.8    .045       0  5031.2     .15       0
Bank Sta=4968.8,5031.2
XS Rating Curve= 0 ,0
Exp/Cntr=0.3,0.1

Type RM Length L Ch R = 1 ,53630   ,500,500,500
BEGIN DESCRIPTION:
Indian Field Swamp 107.0
END DESCRIPTION:
XS GIS Cut Line= 3
      2154892.89       492918.03      2153531.93       493132.14
      2152048.41       493342.08
#Sta/Elev= 30
  3622.3   76.38  3702.3   71.25  3792.3   72.64  3922.3   71.07  4152.3   65.47
  4392.3   61.64  4492.3   62.68  4732.3   61.86  4762.3   62.96  4792.3   61.94
  4932.3   62.11  4968.8   59.57  4970.3   56.57  5029.7   56.57  5031.2   59.57
    5050   62.06    5130   62.59    5640   62.97    5790   61.72    5820   64.31
    5840   62.38    5880   62.15    5940   63.98    5980   66.83    6130   71.09
    6300   70.69    6430   72.51    6470   74.01    6490   76.15  6498.3   75.41
#Mann= 3 ,-1,0
  3622.3     .15       0  4968.8    .045       0  5031.2     .15       0
Bank Sta=4968.8,5031.2
XS Rating Curve= 0 ,0
Exp/Cntr=0.3,0.1

Type RM Length L Ch R = 1 ,53130   ,500,500,500
BEGIN DESCRIPTION:
Indian Field Swamp 106.0
END DESCRIPTION:
XS GIS Cut Line= 3
      2154654.58       492408.23       2153466.1       492636.49
      2151962.65       492884.68
#Sta/Elev= 30
  3789.8   80.16  3879.8    81.9  3959.8   81.79  4079.8   78.78  4179.8    74.4
  4219.8   70.85  4269.8   63.72  4339.8   61.39  4419.8   61.39  4429.8    62.4
  4459.8   61.09  4929.8   62.44  4949.8   61.74  4968.8   59.09  4970.3   56.09
  5029.7   56.09  5031.2   59.09    5170   62.71    5730   62.01    5760   63.21
    5950   61.72    6000   63.31    6020   67.36    6050   67.25    6220   74.77
    6470   76.49    6480   74.01    6490   74.75    6500   77.31  6523.8   77.78
#Mann= 3 ,-1,0
  3789.8     .15       0  4968.8    .045       0  5031.2     .15       0
Bank Sta=4968.8,5031.2
XS Rating Curve= 0 ,0
Exp/Cntr=0.3,0.1

Type RM Length L Ch R = 1 ,52630   ,500,500,500
BEGIN DESCRIPTION:
Indian Field Swamp 105.0
END DESCRIPTION:
XS GIS Cut Line= 3
      2154640.37       491917.46      2153399.53       492140.95
      2151934.01       492393.93
#Sta/Elev= 30
  3739.2    81.4  3909.2      78  4059.2   71.23  4229.2   74.48  4339.2   70.23
  4419.2   63.34  4469.2   61.11  4529.2   61.01  4559.2   64.41  4589.2   61.58
  4749.2   62.06  4968.8    58.9  4970.3    55.9  5029.7    55.9  5031.2    58.9
    5040   61.53    5070   63.01    5080   61.69    5130      63    5180    61.6
    5360   61.47    5390   62.93    5430    61.2    5790   62.02    5920   61.03
    6000   65.57    6010   67.46    6100   71.75    6400   75.78  6487.2   74.86
#Mann= 3 ,-1,0
  3739.2     .15       0  4968.8    .045       0  5031.2     .15       0
Bank Sta=4968.8,5031.2
XS Rating Curve= 0 ,0
Exp/Cntr=0.3,0.1