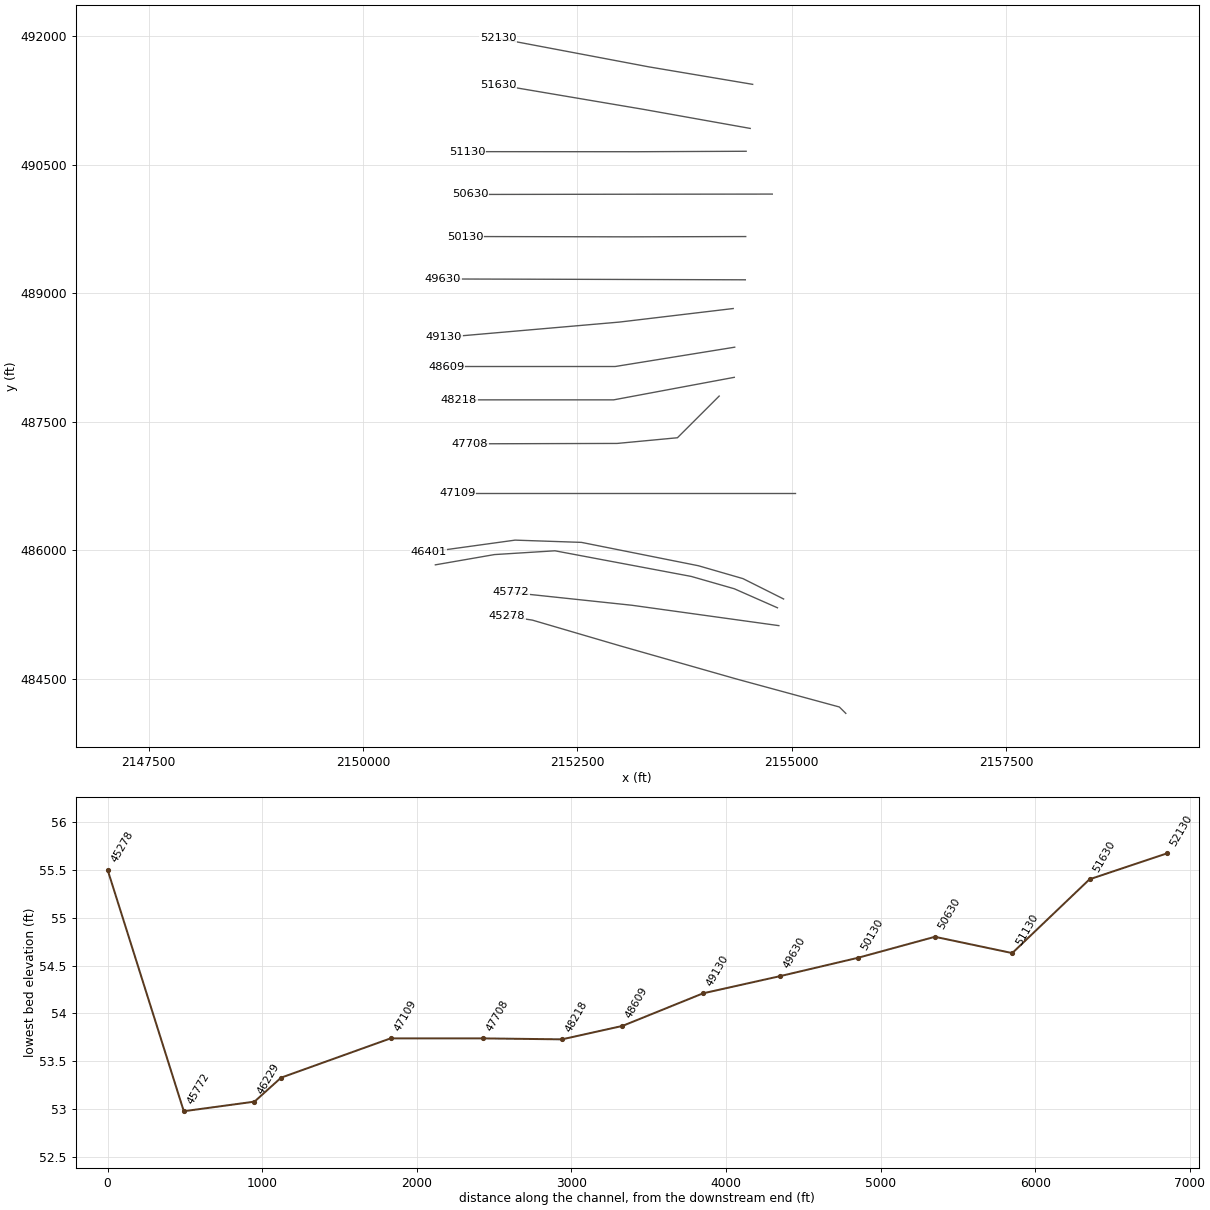
HEC-RAS study IndianFieldsSwamp.prj: S-18-19 over Indian Fields Swamp

--- IndianFieldsSwamp.g14 (geometry) --- (continued)

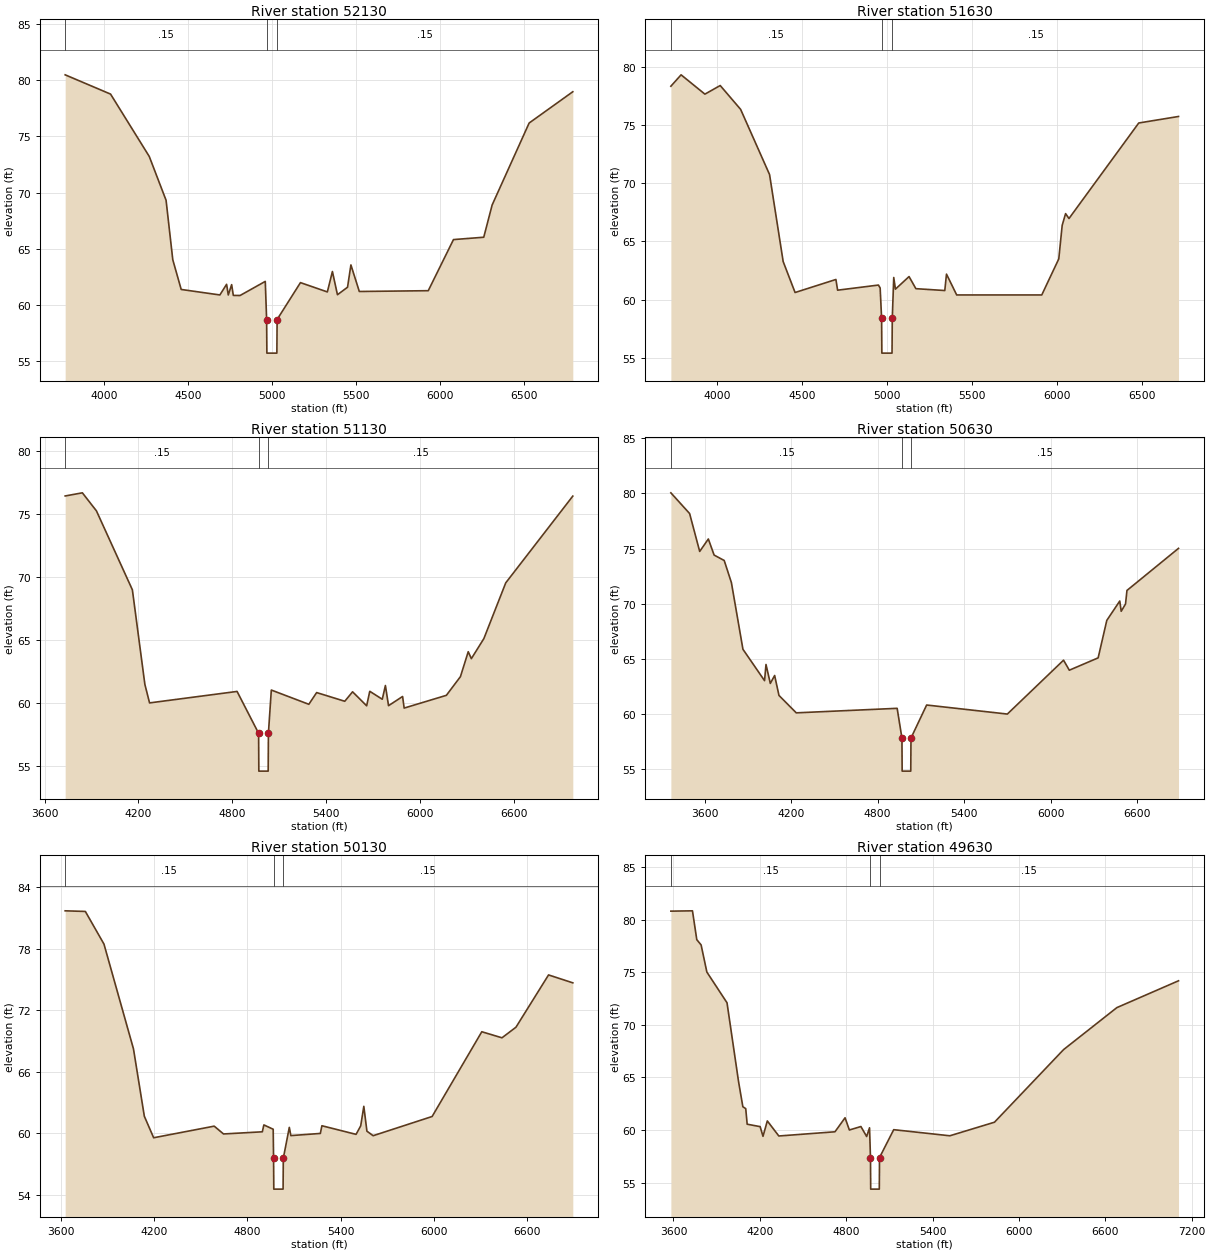
Type RM Length L Ch R = 1 ,52130   ,500,500,500
BEGIN DESCRIPTION:
Indian Field Swamp 104.0
END DESCRIPTION:
XS GIS Cut Line= 3
      2154545.02       491441.01      2153332.93        491645.4
      2151574.57       491978.31
#Sta/Elev= 30
  3770.8    80.5  4040.8   78.78  4270.8   73.22  4370.8   69.31  4410.8      64
  4460.8   61.35  4690.8   60.86  4730.8   61.81  4740.8   60.86  4760.8   61.78
  4770.8   60.82  4810.8   60.81  4960.8   62.07  4968.8   58.67  4970.3   55.67
  5029.7   55.67  5031.2   58.67    5170   61.96    5330   61.13    5360   62.95
    5390   60.88    5450   61.55    5470   63.54    5520   61.17    5930   61.24
    6080    65.8    6260   66.01    6310   68.89    6530    76.2  6789.6   78.99
#Mann= 3 ,-1,0
  3770.8     .15       0  4968.8    .045       0  5031.2     .15       0
Bank Sta=4968.8,5031.2
XS Rating Curve= 0 ,0
Exp/Cntr=0.3,0.1

Type RM Length L Ch R = 1 ,51630   ,500,500,500
BEGIN DESCRIPTION:
Indian Field Swamp 103.0
END DESCRIPTION:
XS GIS Cut Line= 3
      2154516.42       490926.43      2153266.33       491149.86
      2151576.73       491436.23
#Sta/Elev= 30
  3730.1   78.34  3790.1   79.32  3930.1   77.66  4020.1    78.4  4140.1   76.35
  4310.1   70.75  4390.1   63.27  4460.1   60.61  4700.1   61.73  4710.1   60.81
  4950.1   61.25  4960.1      61  4968.6    58.4  4970.1    55.4  5029.9    55.4
  5031.4    58.4    5040    61.9    5050    60.9    5130   61.98    5170   60.94
    5340   60.78    5350   62.19    5410    60.4    5910    60.4    6010    63.5
    6030   66.38    6050   67.39    6070   66.97    6480   75.18  6713.7   75.74
#Mann= 3 ,-1,0
  3730.1     .15       0  4968.6    .045       0  5031.4     .15       0
Bank Sta=4968.6,5031.4
XS Rating Curve= 0 ,0
Exp/Cntr=0.3,0.1

Type RM Length L Ch R = 1 ,51130   ,500,500,500
BEGIN DESCRIPTION:
Indian Field Swamp 102.0
END DESCRIPTION:
XS GIS Cut Line= 3
      2154468.82       490659.61      2153199.73       490654.31
      2151220.63       490655.25
#Sta/Elev= 30
  3730.9   76.45  3840.9    76.7  3930.9   75.27  4160.9   69.01  4240.9   61.51
  4270.9   60.04  4830.9   60.95  4968.6   57.63  4970.1   54.63  5029.9   54.63
  5031.4   57.63    5050   61.06    5290   59.93    5340   60.86    5520   60.17
    5570   60.92    5660   59.81    5680   60.96    5760   60.33    5780   61.42
    5800   59.82    5890   60.55    5900   59.63    6170   60.64    6260   62.12
    6310    64.1    6330   63.55    6410   65.14    6550   69.56  6979.1   76.44
#Mann= 3 ,-1,0
  3730.9     .15       0  4968.6    .045       0  5031.4     .15       0
Bank Sta=4968.6,5031.4
XS Rating Curve= 0 ,0
Exp/Cntr=0.3,0.1

Type RM Length L Ch R = 1 ,50630   ,500,500,500
BEGIN DESCRIPTION:
Indian Field Swamp 101.0
END DESCRIPTION:
XS GIS Cut Line= 3
       2154773.8       490159.66       2153139.2       490158.06
      2151251.61       490155.24
#Sta/Elev= 30
  3365.4   80.06  3495.4   78.18  3565.4   74.74  3625.4   75.87  3665.4   74.41
  3735.4   73.92  3785.4   71.91  3865.4   65.86  4015.4   63.01  4025.4   64.48
  4055.4   62.76  4085.4   63.48  4115.4   61.67  4235.4   60.09  4935.4    60.5
  4968.6    57.8  4970.1    54.8  5029.9    54.8  5031.4    57.8    5140    60.8
    5700   59.98    6090   64.87    6130   63.96    6330   65.08    6390   68.48
    6480   70.24    6490   69.31    6520   69.97    6530    71.2  6887.6   75.02
#Mann= 3 ,-1,0
  3365.4     .15       0  4968.6    .045       0  5031.4     .15       0
Bank Sta=4968.6,5031.4
XS Rating Curve= 0 ,0
Exp/Cntr=0.3,0.1

Type RM Length L Ch R = 1 ,50130   ,500,500,500
BEGIN DESCRIPTION:
Indian Field Swamp 100.0
END DESCRIPTION:
XS GIS Cut Line= 3
      2154464.06       489663.81      2153090.26       489660.46
      2151194.07       489664.07
#Sta/Elev= 30
  3626.2   81.67  3756.2   81.61  3876.2   78.43  4066.2   68.23  4136.2   61.67
  4196.2   59.58  4586.2   60.71  4646.2   59.95  4896.2   60.16  4906.2   60.83
  4966.2   60.41  4968.6   57.58  4970.1   54.58  5029.9   54.58  5031.4   57.58
    5070   60.59    5080   59.79    5270      60    5280   60.75    5500   59.91
    5530   60.74    5550   62.64    5570   60.22    5610   59.78    5990   61.65
    6310    69.9    6440   69.31    6530   70.34    6740   75.43  6896.2   74.66
#Mann= 3 ,-1,0
  3626.2     .15       0  4968.6    .045       0  5031.4     .15       0
Bank Sta=4968.6,5031.4
XS Rating Curve= 0 ,0
Exp/Cntr=0.3,0.1

Type RM Length L Ch R = 1 ,49630   ,500,500,500
BEGIN DESCRIPTION:
Indian Field Swamp 99.0
END DESCRIPTION:
XS GIS Cut Line= 3
      2154459.32       489158.76      2153041.33       489162.86
      2150932.93       489168.48
#Sta/Elev= 30
    3582   80.81    3732   80.84    3762    78.1    3792    77.6    3832   75.02
    3972    72.1    4052   64.62    4082   62.22    4102   62.04    4112   60.56
    4202   60.33    4222   59.41    4252   60.87    4332   59.44    4722   59.84
    4792   61.17    4822   60.01    4902   60.34    4942   59.39    4962   60.22
  4968.6   57.39  4970.1   54.39  5029.9   54.39  5031.4   57.39    5130   60.04
    5520   59.46    5830   60.75    6310   67.65    6680   71.64  7108.4   74.19
#Mann= 3 ,-1,0
    3582     .15       0  4968.6    .045       0  5031.4     .15       0
Bank Sta=4968.6,5031.4
XS Rating Curve= 0 ,0
Exp/Cntr=0.3,0.1

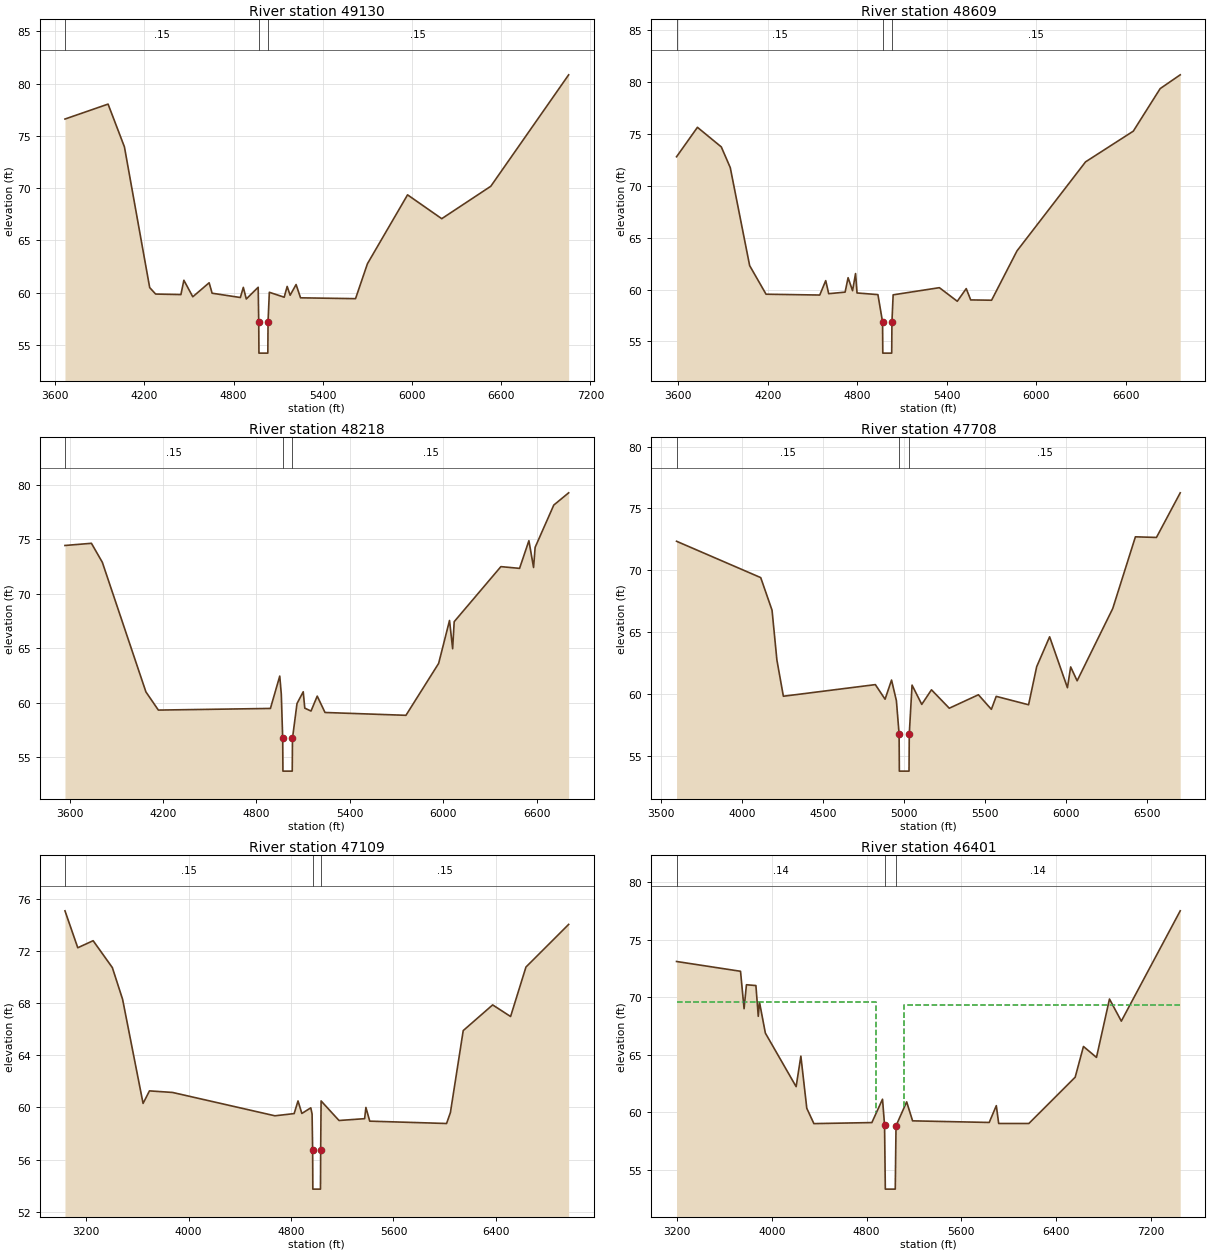
Type RM Length L Ch R = 1 ,49130   ,521,521,521
BEGIN DESCRIPTION:
Indian Field Swamp 98.0
END DESCRIPTION:
XS GIS Cut Line= 3
        2154318.       488823.34      2152992.39       488665.26
      2150946.23       488487.05
#Sta/Elev= 30
    3665    76.6    3955   78.03    4065   73.94    4235   60.48    4275   59.86
    4445   59.81    4465   61.18    4525    59.6    4635   60.94    4655   59.94
    4845   59.53    4865    60.5    4885   59.39    4965   60.51  4968.6   57.21
  4970.1   54.21  5029.9   54.21  5031.4   57.21    5040   60.03    5140   59.56
    5160   60.59    5180   59.75    5220   60.77    5250    59.5    5620   59.42
    5700   62.76    5970   69.35    6200   67.07    6530   70.17  7053.9   80.83
#Mann= 3 ,-1,0
    3665     .15       0  4968.6    .045       0  5031.4     .15       0
Bank Sta=4968.6,5031.4
XS Rating Curve= 0 ,0
Exp/Cntr=0.3,0.1

Type RM Length L Ch R = 1 ,48609   ,391,391,391
BEGIN DESCRIPTION:
Indian Field Swamp 97.0
END DESCRIPTION:
XS GIS Cut Line= 3
       2154335.7       488371.99      2152941.89       488146.33
      2150977.25       488146.33
#Sta/Elev= 30
  3587.5    72.8  3727.5   75.64  3887.5   73.75  3947.5   71.76  4077.5   62.31
  4187.5   59.55  4547.5   59.47  4587.5   60.86  4607.5    59.6  4717.5   59.75
  4737.5   61.14  4767.5   59.89  4787.5   61.54  4797.5   59.67  4937.5   59.51
  4968.6   56.87  4970.1   53.87  5029.9   53.87  5031.4   56.87  5039.5   59.49
  5349.5   60.18  5469.5   58.87  5529.5   60.09  5559.5      59  5699.5   58.97
  5869.5   63.72  6329.5   72.31  6649.5   75.27  6829.5   79.37  6964.1    80.7
#Mann= 3 ,-1,0
  3587.5     .15       0  4968.6    .045       0  5031.4     .15       0
Bank Sta=4968.6,5031.4
XS Rating Curve= 0 ,0
Exp/Cntr=0.3,0.1

Type RM Length L Ch R = 1 ,48218   ,509,509,509
BEGIN DESCRIPTION:
Indian Field Swamp 96.0
END DESCRIPTION:
XS GIS Cut Line= 3
      2154330.63       488020.02      2152924.19       487756.94
      2151118.83       487756.94
#Sta/Elev= 30
  3569.7   74.43  3739.7   74.63  3809.7   72.89  4089.7      61  4169.7   59.33
  4889.7   59.48  4949.7   62.45  4959.7   60.78  4968.6   56.73  4970.1   53.73
  5029.9   53.73  5031.4   56.73  5060.5   59.93  5100.5   61.01  5110.5   59.51
  5150.5   59.24  5190.5   60.61  5240.5   59.11  5760.5   58.85  5970.5   63.61
  6040.5   67.55  6060.5   64.96  6070.5   67.44  6370.5   72.49  6490.5   72.33
  6550.5   74.87  6580.5   72.41  6590.5   74.26  6710.5   78.14  6805.9   79.26
#Mann= 3 ,-1,0
  3569.7     .15       0  4968.6    .045       0  5031.4     .15       0
Bank Sta=4968.6,5031.4
XS Rating Curve= 0 ,0
Exp/Cntr=0.3,0.1

Type RM Length L Ch R = 1 ,47708   ,600,600,600
BEGIN DESCRIPTION:
Indian Field Swamp 95.0
END DESCRIPTION:
XS GIS Cut Line= 4
      2154154.31       487801.18      2153667.58       487314.45
      2152964.01       487248.07      2151247.15       487243.65
#Sta/Elev= 30
  3593.6   72.34  4113.6    69.4  4183.6   66.76  4213.6   62.73  4253.6    59.8
  4821.9   60.74  4881.9   59.56  4921.9   61.11  4951.9   59.44  4968.6   56.74
  4970.1   53.74  5029.9   53.74  5031.4   56.74  5048.6    60.7  5108.6   59.14
  5168.6   60.32  5278.6   58.83  5458.6   59.92  5538.6   58.74  5568.6   59.79
  5768.6   59.11  5818.6   62.19  5898.6   64.61  6008.6   60.49  6028.6   62.17
  6068.6   61.05  6288.6    66.9  6428.6    72.7  6558.6   72.65  6705.5   76.26
#Mann= 3 ,-1,0
  3593.6     .15       0  4968.6    .045       0  5031.4     .15       0
Bank Sta=4968.6,5031.4
XS Rating Curve= 0 ,0
Exp/Cntr=0.3,0.1

Type RM Length L Ch R = 1 ,47109   ,708,708,708
BEGIN DESCRIPTION:
Indian Field Swamp 94.0
END DESCRIPTION:
XS GIS Cut Line= 3
      2155039.33       486663.98      2153079.06       486663.98
      2151105.53       486663.98
#Sta/Elev= 30
  3034.3   75.07  3134.3   72.24  3254.3   72.78  3404.3   70.72  3484.3   68.29
  3644.3   60.31  3694.3   61.27  3874.3   61.15  4674.3   59.36  4824.3   59.53
  4854.3    60.5  4884.3   59.54  4954.3   59.97  4964.3   59.49  4968.6   56.74
  4970.1   53.74  5029.9   53.74  5031.4   56.74  5034.6    60.5  5174.6      59
  5374.6   59.14  5384.6      60  5414.6   58.95  6014.6   58.77  6044.6   59.61
  6144.6   65.89  6374.6   67.86  6514.6   66.97  6634.6   70.76  6968.1   74.03
#Mann= 3 ,-1,0
  3034.3     .15       0  4968.6    .045       0  5031.4     .15       0
Bank Sta=4968.6,5031.4
XS Rating Curve= 0 ,0
Exp/Cntr=0.5,0.3

Type RM Length L Ch R = 1 ,46401   ,172,172,172
BEGIN DESCRIPTION:
Highway 78 at Indian Field - US
END DESCRIPTION:
XS GIS Cut Line= 6
      2154905.63       485431.82       2154431.2       485669.72
      2153912.43       485819.86      2152548.03       486092.77
      2151774.41       486119.06      2150766.09       485979.59
#Sta/Elev= 30
  3193.5    73.1  3734.2   72.25  3764.2      69  3784.2   71.08  3864.2   71.01
  3884.2   68.34  3894.2   69.58  3944.2   66.88  4204.2   62.23  4244.2   64.88
  4294.3   60.35  4354.3   59.02  4844.3   59.11  4934.3   61.14  4951.5   58.89
    4958   53.33    5042   53.33  5048.5   58.83  5138.4   60.91  5188.4   59.26
  5836.1   59.12  5896.1   60.58  5916.1   59.03  6171.1   59.03  6562.6   63.05
  6632.6   65.72  6742.6   64.77  6852.6   69.84  6952.6   67.92  7450.5    77.5
#Mann= 3 ,-1,0
  3193.5     .14       0  4951.5    .045       0  5048.5     .14       0
#XS Ineff= 2 , 0
          4881.5   69.56  5118.5           69.34
Permanent Ineff=
       F       F
Bank Sta=4951.5,5048.5
XS Rating Curve= 0 ,0
Exp/Cntr=0.5,0.3

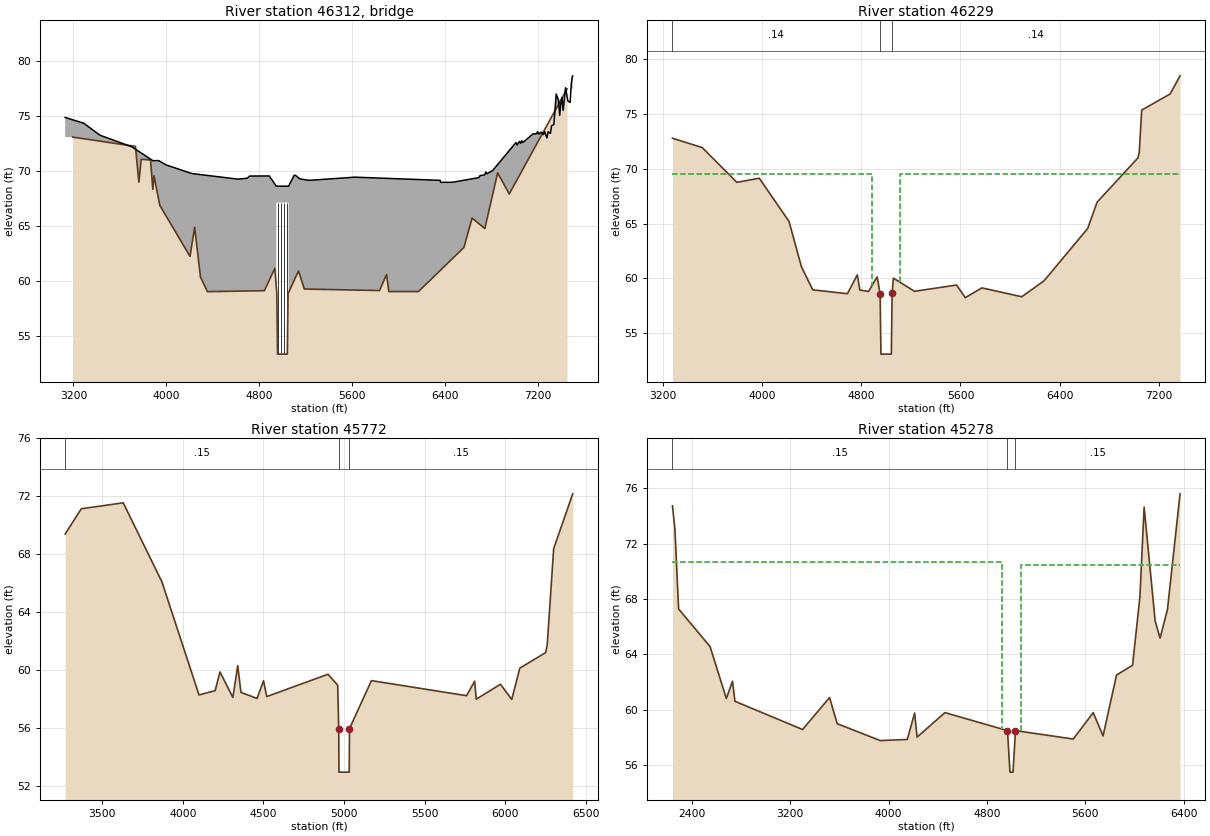
Type RM Length L Ch R = 3 ,46312   ,,,
BEGIN DESCRIPTION:
Highway 78 at Indian Field - TOR
Structure ID: LDS_IFS_03
Approximate Survey Structure
END DESCRIPTION:
Bridge Culvert--1,0,-1,-1, 0
Deck Dist Width WeirC Skew NumUp NumDn MinLoCord MaxHiCord MaxSubmerge Is_Ogee
65.5,47,3,0, 60, 60, , , 0.95, 0, 1,1,,
  3129.4  3289.4  3429.4  3704.2  3884.2  3934.2  3999.6  4219.6  4616.4  4696.4
  4716.4  4886.4    4947    4947    5053    5053  5100.1  5110.1  5150.1  5230.1
  5624.1  6357.8  6362.1  6462.1  6690.7  6700.7  6740.7  6750.7  6760.7  6810.1
  7010.1  7020.1  7040.1  7050.1  7060.1  7070.1  7156.9  7186.9  7196.9  7206.9
  7226.9  7246.9  7256.9  7276.9  7286.9  7306.9  7316.9  7336.9  7356.9  7376.9
  7386.9  7396.9  7406.9  7416.9  7436.9  7456.9  7476.9  7486.9  7496.9  7499.2
   74.89   74.36   73.27   72.21   70.95   70.96   70.56   69.78   69.27   69.35
   69.55   69.56   68.63   68.63   68.63   68.63   69.61   69.63   69.29   69.16
   69.45   69.16   68.98   68.98   69.41   69.59   69.66   69.92   69.76   70.06
    72.6   72.38   72.71   72.54   72.77   72.61   73.39    73.4   73.59   73.37
   73.56   73.33   73.59   73.02   73.58   73.44   74.12   74.25   77.02   76.46
   75.08   76.16   76.71   75.53   77.59    76.4   76.25      78   78.68   78.67
   33.33   33.33   33.33   33.33   33.33   33.33   33.33   33.33   33.33   33.33
   33.33   33.33   33.33   67.13   67.13   33.33   33.33   33.33   33.33   33.33
   33.33   33.33   33.33   33.33   33.33   33.33   33.33   33.33   33.33   33.33
   33.33   33.33   33.33   33.33   33.33   33.33   33.33   33.33   33.33   33.33
   33.33   33.33   33.33   33.33   33.33   33.33   33.33   33.33   33.33   33.33
   33.33   33.33   33.33   33.33   33.33   33.33   33.33   33.33   33.33   33.33
  3129.4  3289.4  3429.4  3704.2  3884.2  3934.2  3999.6  4219.6  4616.4  4696.4
  4716.4  4886.4    4947    4947    5053    5053  5100.1  5110.1  5150.1  5230.1
  5624.1  6357.8  6362.1  6462.1  6690.7  6700.7  6740.7  6750.7  6760.7  6810.1
  7010.1  7020.1  7040.1  7050.1  7060.1  7070.1  7156.9  7186.9  7196.9  7206.9
  7226.9  7246.9  7256.9  7276.9  7286.9  7306.9  7316.9  7336.9  7356.9  7376.9
  7386.9  7396.9  7406.9  7416.9  7436.9  7456.9  7476.9  7486.9  7496.9  7499.2
   74.89   74.36   73.27   72.21   70.95   70.96   70.56   69.78   69.27   69.35
   69.55   69.56   68.63   68.63   68.63   68.63   69.61   69.63   69.29   69.16
   69.45   69.16   68.98   68.98   69.41   69.59   69.66   69.92   69.76   70.06
    72.6   72.38   72.71   72.54   72.77   72.61   73.39    73.4   73.59   73.37
   73.56   73.33   73.59   73.02   73.58   73.44   74.12   74.25   77.02   76.46
   75.08   76.16   76.71   75.53   77.59    76.4   76.25      78   78.68   78.67
   33.33   33.33   33.33   33.33   33.33   33.33   33.33   33.33   33.33   33.33
   33.33   33.33   33.33   67.13   67.13   33.33   33.33   33.33   33.33   33.33
   33.33   33.33   33.33   33.33   33.33   33.33   33.33   33.33   33.33   33.33
   33.33   33.33   33.33   33.33   33.33   33.33   33.33   33.33   33.33   33.33
   33.33   33.33   33.33   33.33   33.33   33.33   33.33   33.33   33.33   33.33
   33.33   33.33   33.33   33.33   33.33   33.33   33.33   33.33   33.33   33.33
Pier Skew, UpSta & Num, DnSta & Num=  ,4960.3, 2 ,4960.3, 2 , 0 , 0 , 0 ,0,0
     1.5     1.5
   53.33   67.13
     1.5     1.5
   53.08   67.13
Pier Skew, UpSta & Num, DnSta & Num=  ,4986.8, 2 ,4986.8, 2 , 0 , 0 , 0 ,0,0
     1.5     1.5
   53.33   67.13
     1.5     1.5
   53.08   67.13
Pier Skew, UpSta & Num, DnSta & Num=  ,5013.3, 2 ,5013.3, 2 , 0 , 0 , 0 ,0,0
     1.5     1.5
   53.33   67.13
     1.5     1.5
   53.08   67.13
Pier Skew, UpSta & Num, DnSta & Num=  ,5039.8, 2 ,5039.8, 2 , 0 , 0 , 0 ,0,0
     1.5     1.5
   53.33   67.13
     1.5     1.5
   53.08   67.13
Abutment Skew #Up #Dn= , 2 , 2
    4947    4958
   67.13   53.33
    4947    4958
   67.13   53.08
Abutment Skew #Up #Dn= , 2 , 2
    5042    5053
   53.33   67.13
    5042    5053
   53.08   67.13
BR Coef=-1 ,-1 , 0 ,1.25, 0 ,,,0.8,0,2,0,
WSPro=,,,, 1 ,,,, 0 ,,,, 0 ,,,,-1 ,-1 ,-1 , 0 , 0 , 0 , 0 , 0
BC Design=,, 0 ,, 0 ,,,,,,
BC HTab HWMax=77.5
BC Use User HTab Curves=0
BC User HTab FreeFlow(D)= 0

Type RM Length L Ch R = 1 ,46229   ,457,457,457
BEGIN DESCRIPTION:
Highway 78 at Indian Field - DS
END DESCRIPTION:
XS GIS Cut Line= 6
      2154834.12       485328.93       2154330.1       485551.29
      2153828.72       485695.17      2152239.22       485994.47
       2151533.5        485950.3      2150844.49       485830.45
#Sta/Elev= 30
    3275    72.8    3515   71.95    3795   68.77  3975.9   69.15  4215.9    65.2
  4315.9   61.07  4407.5   58.95  4687.5    58.6  4767.5   60.32  4787.5   58.94
  4857.5    58.8  4927.5   60.14  4951.5   58.58    4958   53.08    5042   53.08
  5048.5   58.67  5058.8   60.02  5228.8   58.82  5568.8   59.39  5638.8   58.24
  5773.4   59.13    6095   58.32    6275   59.78  6626.9   64.55  6703.3   66.96
  7033.3   71.01  7043.3   71.53  7063.3   75.37  7293.3   76.85  7372.7    78.5
#Mann= 3 ,-1,0
    3275     .14       0  4951.5    .045       0  5048.5     .14       0
#XS Ineff= 2 , 0
          4887.5   69.55  5112.5           69.55
Permanent Ineff=
       F       F
Bank Sta=4951.5,5048.5
XS Rating Curve= 0 ,0
Exp/Cntr=0.5,0.3

Type RM Length L Ch R = 1 ,45772   ,493,493,493
BEGIN DESCRIPTION:
Indian Field Swamp 91.0
END DESCRIPTION:
XS GIS Cut Line= 3
      2154850.26       485120.64      2153137.46       485358.37
       2151727.2       485508.09
#Sta/Elev= 30
  3270.3    69.4  3370.3   71.14  3630.3   71.55  3870.3    66.1  4100.3    58.3
  4200.3    58.6  4230.3   59.89  4310.3   58.13  4340.3   60.32  4360.3   58.48
  4460.3   58.06  4500.3   59.28  4520.3   58.19  4900.3   59.73  4960.3   58.97
  4966.7   55.98  4968.2   52.98  5031.8   52.98  5033.3   55.98  5169.5   59.29
  5759.5   58.25  5809.5   59.25  5819.5   58.01  5969.5   59.04  6039.5   57.99
  6089.5   60.15  6249.5   61.22  6259.5   61.75  6299.5   68.39  6417.7   72.17
#Mann= 3 ,-1,0
  3270.3     .15       0  4966.7    .045       0  5033.3     .15       0
Bank Sta=4966.7,5033.3
XS Rating Curve= 0 ,0
Exp/Cntr=0.5,0.3

Type RM Length L Ch R = 1 ,45278   ,98,98,98
BEGIN DESCRIPTION:
Railroad at Indian Field - US
END DESCRIPTION:
XS GIS Cut Line= 6
      2155631.11       484096.08      2155555.64       484170.72
      2154364.91         484495.      2152998.56       484884.78
      2151975.48       485185.17      2151676.68       485230.47
#Sta/Elev= 30
  2241.7   74.74  2261.7   73.06  2291.7   67.29  2547.8   64.57    2680   60.82
    2730   62.07    2750   60.62    3300   58.58    3520   60.89    3582      59
    3932   57.78    4152   57.86    4212   59.77    4232   58.03  4458.7    59.8
  4967.5    58.5  4987.5    55.5  5012.5    55.5  5032.5    58.5  5502.8   57.89
  5664.9    59.8  5744.9   58.12  5854.9   62.52  5984.9   63.22  6044.9   68.17
  6079.1   74.65  6169.1   66.41  6209.1   65.19  6269.1   67.26  6371.3   75.61
#Mann= 3 ,-1,0
  2241.7     .15       0  4967.5    .045       0  5032.5     .15       0
#XS Ineff= 2 , 0
            4919   70.67    5081           70.49
Permanent Ineff=
       F       F
Bank Sta=4967.5,5032.5
XS Rating Curve= 0 ,0
Exp/Cntr=0.5,0.3