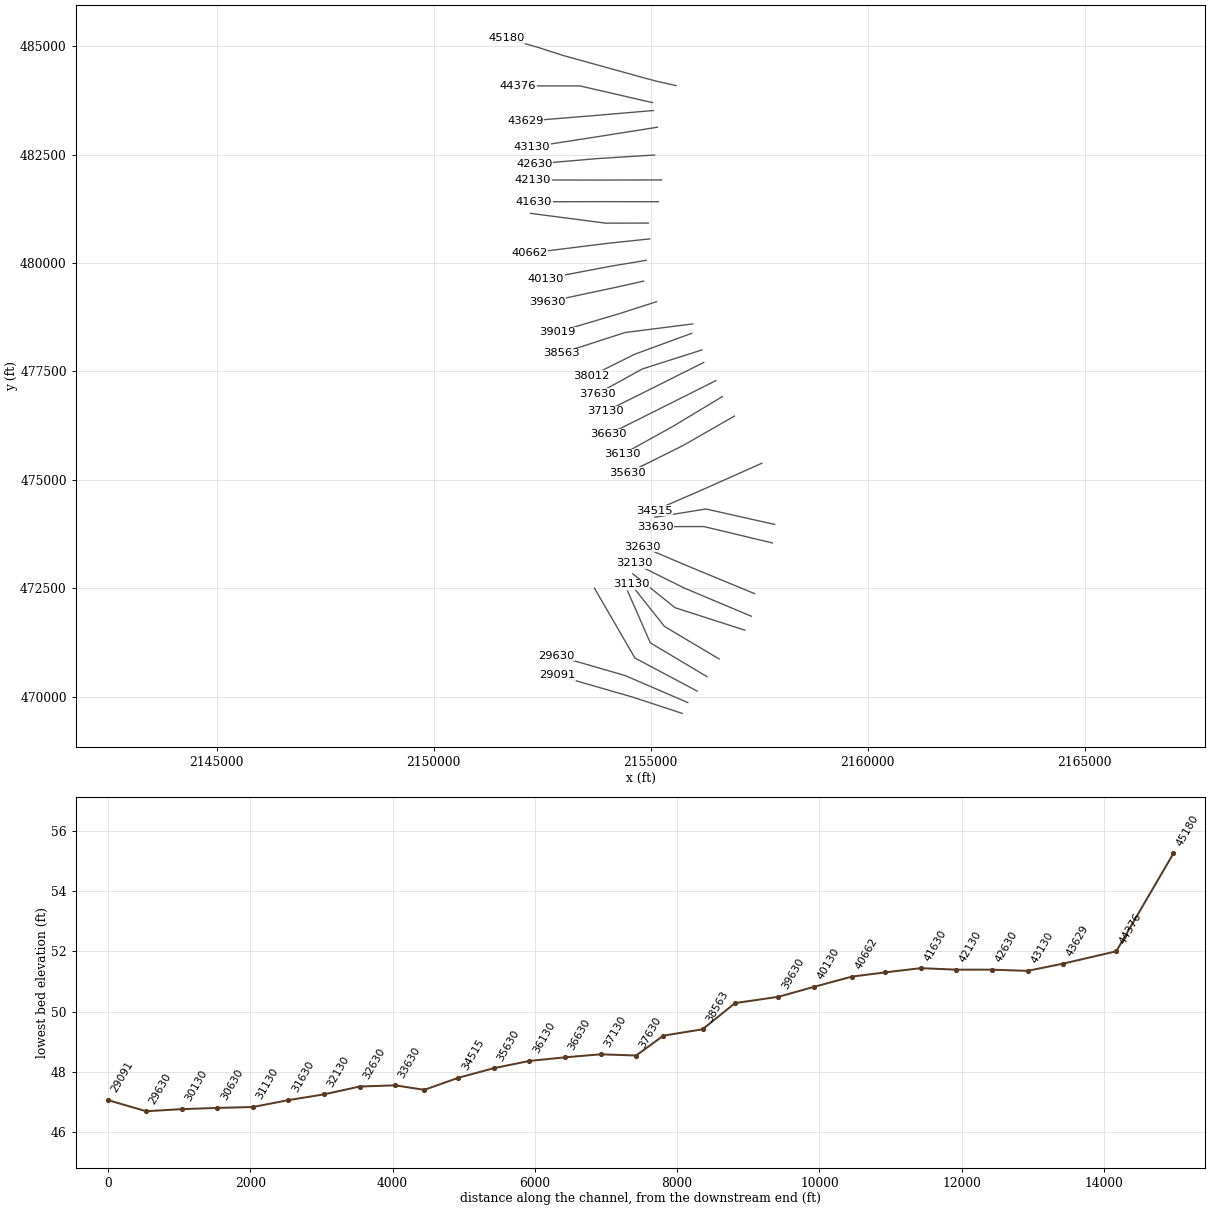
HEC-RAS study IndianFieldsSwamp.prj: S-18-19 over Indian Fields Swamp

--- IndianFieldsSwamp.g14 (geometry) --- (continued)

Type RM Length L Ch R = 3 ,45237   ,,,
BEGIN DESCRIPTION:
Railroad at Indian Field - TOR
Structure ID: LDS_IFS_RR
Approximate Survey Structure
END DESCRIPTION:
Bridge Culvert--1,0,-1,-1, 0
Deck Dist Width WeirC Skew NumUp NumDn MinLoCord MaxHiCord MaxSubmerge Is_Ogee
21,40,3,0, 60, 60, , , 0.95, 0, 1,1,,
    2244  2292.6  2532.6  2642.6  2965.6  3135.6  3155.6  3165.6  3395.6  3465.6
  3475.6  3515.6  3595.6  3755.6  3765.6  3785.6  3805.6  3825.6  3845.6  4055.6
  4075.6  4085.6  4135.6  4145.6  4155.6  4225.6  4284.8  4374.8  4434.8  4931.1
    4940    4940    5060    5060  5289.2  5389.2  5449.2  5469.2  5559.2  5637.1
  5657.1  5707.1  5847.1  5867.1  5887.1  5907.1  5967.1  6007.1  6017.1  6027.1
  6037.1  6130.5  6180.5  6210.5  6230.5  6240.5  6290.5  6310.5  6340.5  6376.8
    74.7    74.7   73.31   73.17   71.12   70.74   70.32   70.68   69.88   69.88
   70.17   69.73   69.95   69.64   69.97   69.61   69.93   69.59   69.88   69.75
   70.04   69.77   69.78   70.05    69.8   69.84   70.22   70.08   70.38   70.77
    70.5    70.5    70.5    70.5   70.76   71.36   71.13   71.48   71.82   71.77
   72.09   72.03   72.72   73.08   72.83    73.2   73.17   73.55   73.33   73.87
   73.55   74.01   73.83   74.57   74.21   74.57   74.67   75.13   74.99   75.32
    35.5    35.5    35.5    35.5    35.5    35.5    35.5    35.5    35.5    35.5
    35.5    35.5    35.5    35.5    35.5    35.5    35.5    35.5    35.5    35.5
    35.5    35.5    35.5    35.5    35.5    35.5    35.5    35.5    35.5    35.5
    35.5    67.5    67.5    35.5    35.5    35.5    35.5    35.5    35.5    35.5
    35.5    35.5    35.5    35.5    35.5    35.5    35.5    35.5    35.5    35.5
    35.5    35.5    35.5    35.5    35.5    35.5    35.5    35.5    35.5    35.5
    2244  2292.6  2532.6  2642.6  2965.6  3135.6  3155.6  3165.6  3395.6  3465.6
  3475.6  3515.6  3595.6  3755.6  3765.6  3785.6  3805.6  3825.6  3845.6  4055.6
  4075.6  4085.6  4135.6  4145.6  4155.6  4225.6  4284.8  4374.8  4434.8  4931.1
    4940    4940    5060    5060  5289.2  5389.2  5449.2  5469.2  5559.2  5637.1
  5657.1  5707.1  5847.1  5867.1  5887.1  5907.1  5967.1  6007.1  6017.1  6027.1
  6037.1  6130.5  6180.5  6210.5  6230.5  6240.5  6290.5  6310.5  6340.5  6376.8
    74.7    74.7   73.31   73.17   71.12   70.74   70.32   70.68   69.88   69.88
   70.17   69.73   69.95   69.64   69.97   69.61   69.93   69.59   69.88   69.75
   70.04   69.77   69.78   70.05    69.8   69.84   70.22   70.08   70.38   70.77
    70.5    70.5    70.5    70.5   70.76   71.36   71.13   71.48   71.82   71.77
   72.09   72.03   72.72   73.08   72.83    73.2   73.17   73.55   73.33   73.87
   73.55   74.01   73.83   74.57   74.21   74.57   74.67   75.13   74.99   75.32
    35.5    35.5    35.5    35.5    35.5    35.5    35.5    35.5    35.5    35.5
    35.5    35.5    35.5    35.5    35.5    35.5    35.5    35.5    35.5    35.5
    35.5    35.5    35.5    35.5    35.5    35.5    35.5    35.5    35.5    35.5
    35.5    67.5    67.5    35.5    35.5    35.5    35.5    35.5    35.5    35.5
    35.5    35.5    35.5    35.5    35.5    35.5    35.5    35.5    35.5    35.5
    35.5    35.5    35.5    35.5    35.5    35.5    35.5    35.5    35.5    35.5
Abutment Skew #Up #Dn= , 2 , 2
    4940    4960
    67.5    58.5
    4940    4960
    67.5    58.4
Abutment Skew #Up #Dn= , 2 , 2
    5040    5060
    58.7    67.5
    5040    5060
    58.3    67.5
BR Coef=-1 ,-1 , 0 ,1.25, 0 ,,,0.8,0,2,0,
WSPro=,,,, 1 ,,,, 0 ,,,, 0 ,,,,-1 ,-1 ,-1 , 0 , 0 , 0 , 0 , 0
BC Design=,, 0 ,, 0 ,,,,,,
BC HTab HWMax=75.61
BC Use User HTab Curves=0
BC User HTab FreeFlow(D)= 0

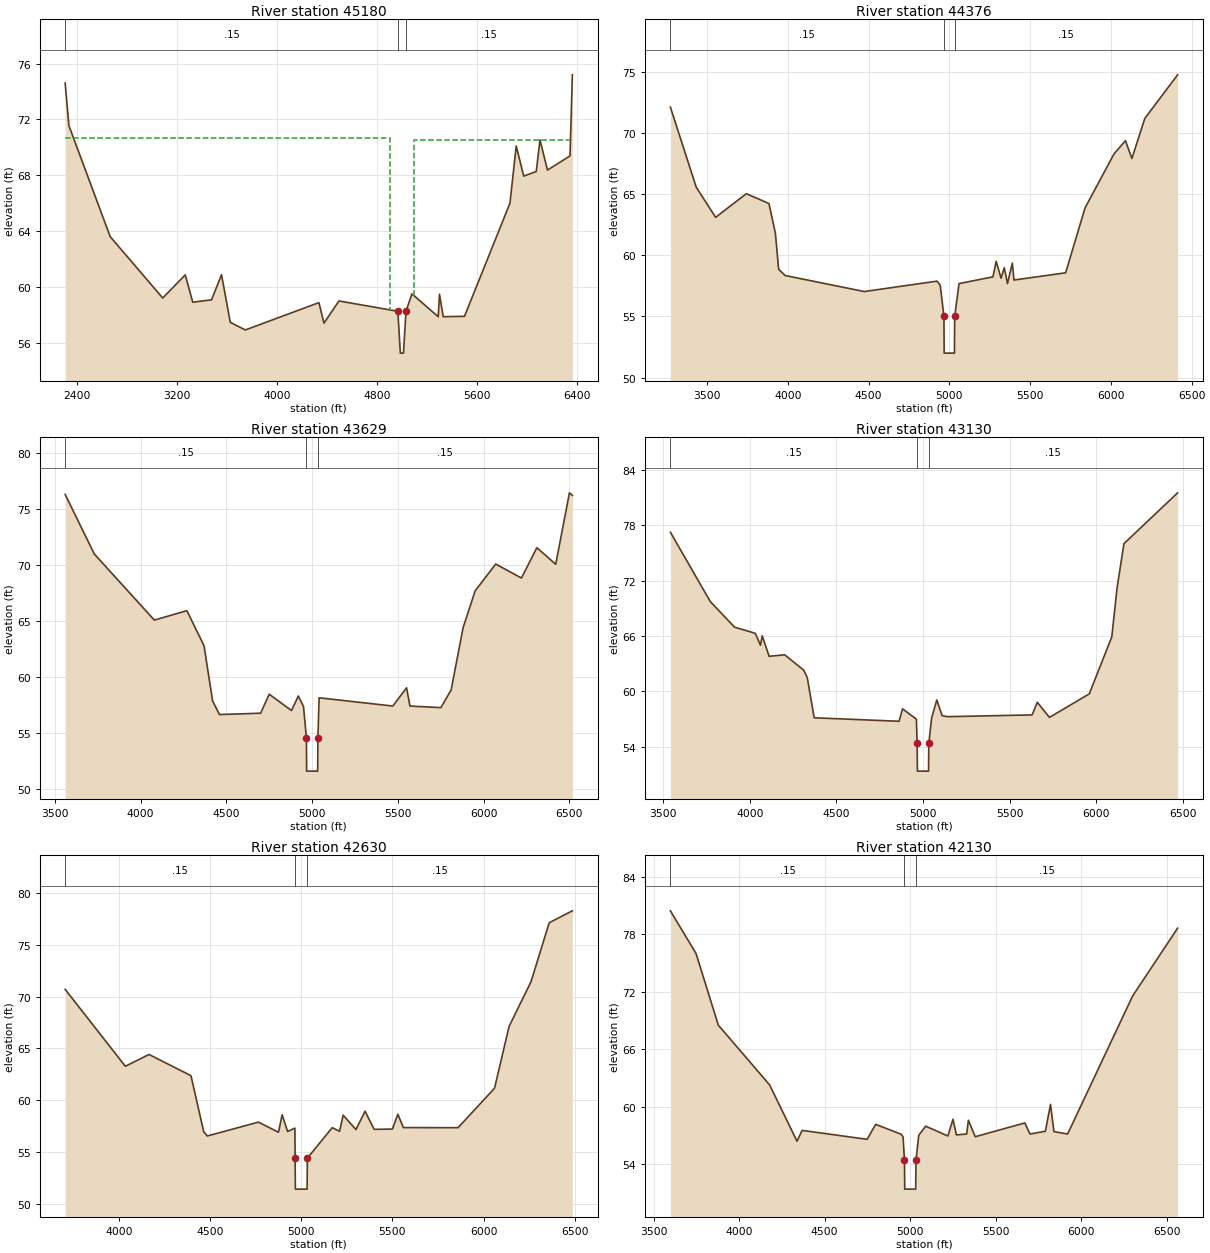
Type RM Length L Ch R = 1 ,45180   ,804,804,804
BEGIN DESCRIPTION:
Railroad at Indian Field - DS
END DESCRIPTION:
XS GIS Cut Line= 6
      2155585.67        484094.2      2155163.49       484187.34
       2154846.8       484271.54      2152984.91       484787.55
      2152429.67       484966.66      2151681.63       485183.31
#Sta/Elev= 30
  2308.2   74.61  2338.2   71.56  2668.2    63.6  3088.2    59.2  3268.2   60.86
  3328.2    58.9  3478.2   59.07  3558.2   60.87  3628.2   57.46  3748.2   56.91
  4336.8   58.87  4376.8    57.4  4496.8   58.99  4967.5   58.25  4987.5   55.25
  5012.5   55.25  5032.5   58.25  5080.3    59.5  5290.3   57.86  5300.3   59.47
  5330.3   57.86  5500.3   57.89  5863.7      66  5913.7    70.1  5973.7   67.94
  6073.7   68.27  6103.7   70.53  6163.7   68.37  6343.7   69.39  6362.5    75.2
#Mann= 3 ,-1,0
  2308.2     .15       0  4967.5    .045       0  5032.5     .15       0
#XS Ineff= 2 , 0
            4903   70.66    5097           70.53
Permanent Ineff=
       F       F
Bank Sta=4967.5,5032.5
XS Rating Curve= 0 ,0
Exp/Cntr=0.5,0.3

Type RM Length L Ch R = 1 ,44376   ,748,748,748
BEGIN DESCRIPTION:
Indian Field Swamp 88.0
END DESCRIPTION:
XS GIS Cut Line= 3
      2155041.14       483700.69      2153368.45       484086.45
      2151945.44       484086.45
#Sta/Elev= 30
  3273.6   72.09  3433.6   65.55  3553.6   63.09  3743.6   65.02  3883.6   64.22
  3923.6   61.78  3943.6   58.85  3983.6   58.34  4473.6   57.03  4923.6   57.88
  4943.6   57.55  4966.7      55  4968.2      52  5031.8      52  5033.3      55
  5060.2   57.68  5270.2   58.23  5290.2    59.5  5320.2   58.12  5340.2   58.98
  5360.2   57.68  5390.2   59.35  5400.2   57.97  5720.2   58.56  5840.2   63.86
  6020.2   68.29  6090.2   69.35  6130.2    67.9  6210.2   71.17  6413.2   74.73
#Mann= 3 ,-1,0
  3273.6     .15       0  4966.7    .045       0  5033.3     .15       0
Bank Sta=4966.7,5033.3
XS Rating Curve= 0 ,0
Exp/Cntr=0.3,0.1

Type RM Length L Ch R = 1 ,43629   ,499,499,499
BEGIN DESCRIPTION:
Indian Field Swamp 87.0
END DESCRIPTION:
XS GIS Cut Line= 3
      2155066.79       483518.94      2153631.03       483396.11
      2152119.01       483273.29
#Sta/Elev= 30
  3559.5   76.34  3729.5   71.01  4079.5    65.1  4269.5   65.94  4369.5    62.8
  4419.5   57.86  4459.5   56.65  4699.5   56.77  4749.5   58.47  4879.5   57.01
  4919.5   58.31  4949.5   57.37  4966.4   54.59  4967.9   51.59  5032.1   51.59
  5033.6   54.59  5040.5   58.15  5470.5   57.41  5550.5   59.04  5570.5   57.41
  5750.5   57.27  5810.5   58.85  5880.5   64.43  5950.5   67.71  6070.5   70.11
  6220.5   68.86  6310.5   71.57  6420.5   70.09  6500.5   76.48  6517.5   76.25
#Mann= 3 ,-1,0
  3559.5     .15       0  4966.4    .045       0  5033.6     .15       0
Bank Sta=4966.4,5033.6
XS Rating Curve= 0 ,0
Exp/Cntr=0.3,0.1

Type RM Length L Ch R = 1 ,43130   ,500,500,500
BEGIN DESCRIPTION:
Indian Field Swamp 86.0
END DESCRIPTION:
XS GIS Cut Line= 3
      2155155.71       483133.53      2153715.76       482904.82
       2152263.1       482680.37
#Sta/Elev= 30
    3542   77.23    3772   69.73    3912   66.95    4032   66.28    4062   64.99
    4072   66.01    4112   63.79    4202   63.95    4312   62.28    4332   61.49
    4372   57.13    4862   56.75    4882    58.1    4962   56.98  4966.4   54.35
  4967.9   51.35  5032.1   51.35  5033.6   54.35    5050   57.11    5080   59.06
    5110   57.37    5140   57.25    5630   57.44    5660   58.81    5730   57.17
    5960   59.72    6090    65.9    6120   71.15    6160   75.99  6469.9    81.5
#Mann= 3 ,-1,0
    3542     .15       0  4966.4    .045       0  5033.6     .15       0
Bank Sta=4966.4,5033.6
XS Rating Curve= 0 ,0
Exp/Cntr=0.3,0.1

Type RM Length L Ch R = 1 ,42630   ,500,500,500
BEGIN DESCRIPTION:
Indian Field Swamp 85.0
END DESCRIPTION:
XS GIS Cut Line= 3
      2155089.99       482492.79      2153797.83       482411.69
      2152316.31       482285.38
#Sta/Elev= 30
  3705.3   70.71  4035.3   63.27  4165.3   64.41  4395.3   62.36  4465.3   56.93
  4485.3   56.53  4765.3   57.87  4875.3   56.89  4895.3   58.58  4925.3   56.96
  4965.3   57.29  4966.4   54.39  4967.9   51.39  5032.1   51.39  5033.6   54.39
    5170   57.33    5210   56.98    5230   58.54    5300   57.15    5350   58.92
    5400   57.17    5500    57.2    5530   58.63    5560   57.34    5860   57.33
    6060   61.14    6140   67.13    6260   71.44    6360   77.15  6486.9    78.3
#Mann= 3 ,-1,0
  3705.3     .15       0  4966.4    .045       0  5033.6     .15       0
Bank Sta=4966.4,5033.6
XS Rating Curve= 0 ,0
Exp/Cntr=0.3,0.1

Type RM Length L Ch R = 1 ,42130   ,500,500,500
BEGIN DESCRIPTION:
Indian Field Swamp 84.0
END DESCRIPTION:
XS GIS Cut Line= 3
      2155248.87       481918.03      2153847.17       481914.13
      2152284.28       481918.03
#Sta/Elev= 30
  3598.3   80.44  3748.3   75.98  3878.3   68.51  4178.3   62.27  4338.3   56.39
  4368.3   57.52  4748.3   56.59  4798.3   58.15  4948.3   57.11  4958.3   56.82
  4966.4   54.39  4967.9   51.39  5032.1   51.39  5033.6   54.39    5050   57.01
    5090   57.96    5220   56.94    5250   58.68    5270   57.05    5330   57.14
    5340   58.58    5380   56.86    5670    58.3    5700   57.14    5790   57.43
    5820   60.24    5840    57.4    5920   57.14    6300   71.55  6562.9   78.63
#Mann= 3 ,-1,0
  3598.3     .15       0  4966.4    .045       0  5033.6     .15       0
Bank Sta=4966.4,5033.6
XS Rating Curve= 0 ,0
Exp/Cntr=0.3,0.1

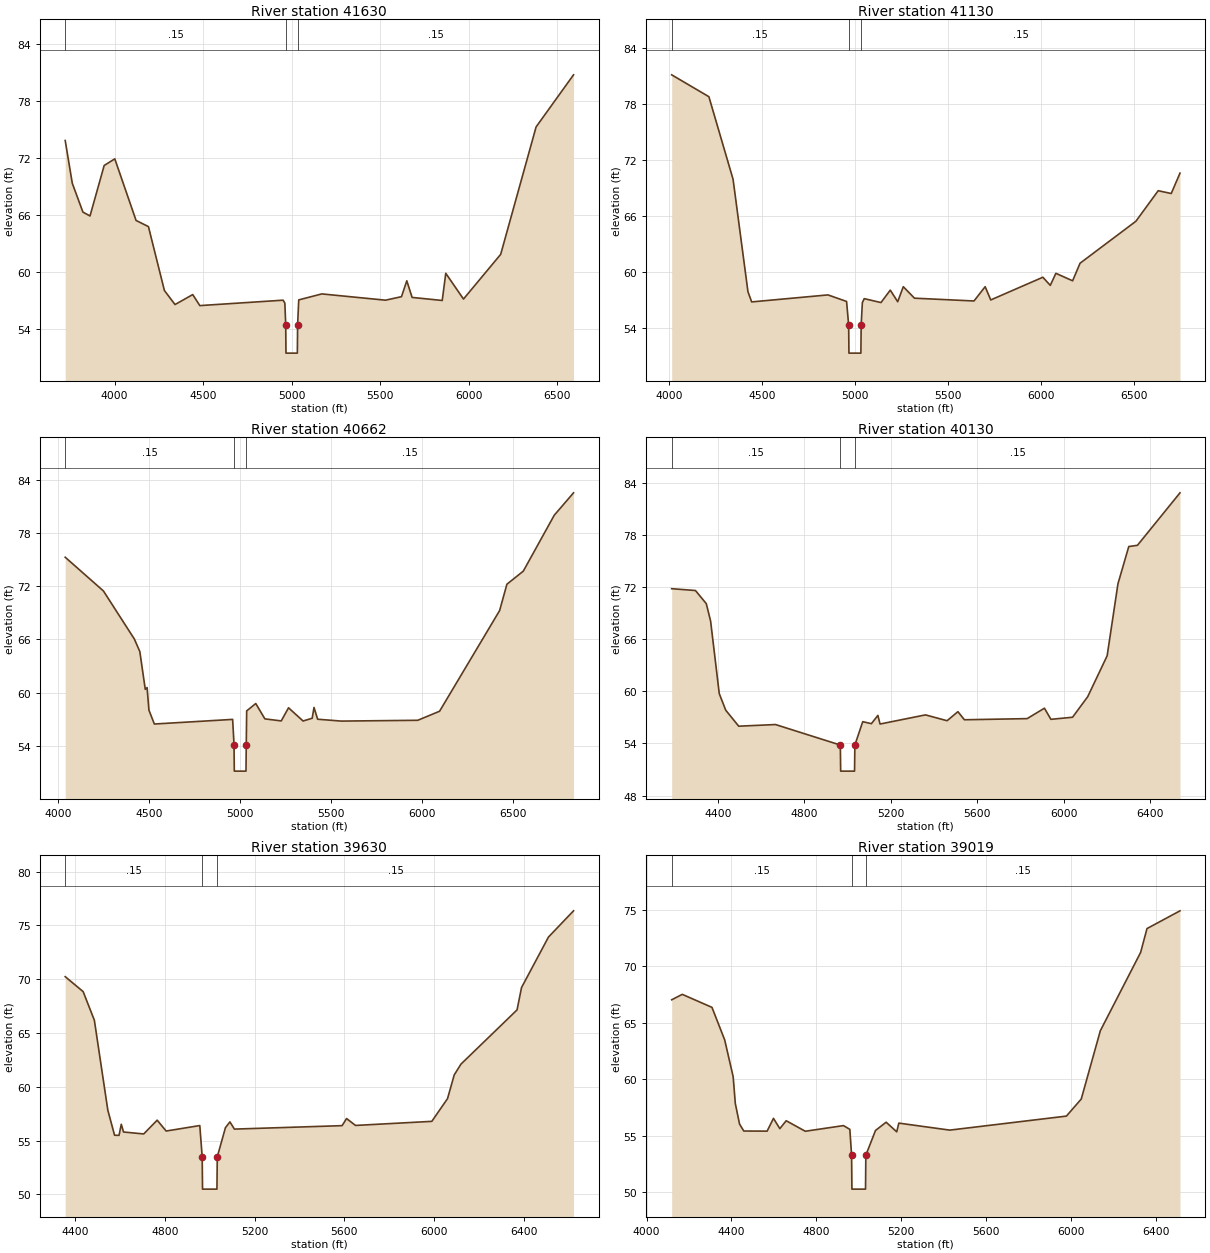
Type RM Length L Ch R = 1 ,41630   ,500,500,500
BEGIN DESCRIPTION:
Indian Field Swamp 83.0
END DESCRIPTION:
XS GIS Cut Line= 3
      2155179.44       481415.05      2153900.94       481417.07
      2152309.64       481414.04
#Sta/Elev= 30
  3721.5   73.81  3761.5   69.31  3821.5   66.28  3861.5   65.87  3941.5   71.18
  4001.5   71.88  4121.5    65.4  4191.5   64.75  4281.5   58.03  4341.5   56.55
  4441.5    57.6  4481.5   56.44  4951.5   57.01  4961.5   56.71  4966.4   54.44
  4967.9   51.44  5032.1   51.44  5033.6   54.44    5040   57.04    5170   57.67
    5530   57.01    5620   57.38    5650   59.05    5680    57.3    5850   56.98
    5870   59.84    5970   57.13    6180   61.83    6380   75.24  6591.3   80.72
#Mann= 3 ,-1,0
  3721.5     .15       0  4966.4    .045       0  5033.6     .15       0
Bank Sta=4966.4,5033.6
XS Rating Curve= 0 ,0
Exp/Cntr=0.3,0.1

Type RM Length L Ch R = 1 ,41130   ,467,467,467
BEGIN DESCRIPTION:
Indian Field Swamp 82.0
END DESCRIPTION:
XS GIS Cut Line= 3
      2154948.16       480922.75      2153963.36       480920.98
       2152230.9       481146.63
#Sta/Elev= 30
  4015.2   81.08  4215.2   78.74  4345.2    69.9  4425.2   57.87  4445.2   56.78
  4855.2   57.53  4955.2   56.83  4966.4    54.3  4967.9    51.3  5032.1    51.3
  5033.6    54.3    5040    56.7    5050   57.13    5140   56.71    5190   58.04
    5230    56.8    5260   58.41    5320   57.18    5640   56.88    5700   58.41
    5730   56.99    6010   59.42    6050   58.55    6080   59.84    6170   59.04
    6210   60.92    6510   65.41    6630   68.68    6700   68.38  6747.1   70.56
#Mann= 3 ,-1,0
  4015.2     .15       0  4966.4    .045       0  5033.6     .15       0
Bank Sta=4966.4,5033.6
XS Rating Curve= 0 ,0
Exp/Cntr=0.3,0.1

Type RM Length L Ch R = 1 ,40662   ,533,533,533
BEGIN DESCRIPTION:
Indian Field Swamp 81.0
END DESCRIPTION:
XS GIS Cut Line= 3
      2154977.81       480557.18      2154025.78       480457.42
      2152203.73       480231.07
#Sta/Elev= 30
  4038.7   75.27  4248.7   71.47  4418.7   66.05  4448.7   64.64  4478.7   60.38
  4488.7   60.58  4498.7   58.04  4528.7   56.47  4958.7   56.99  4966.4   54.16
  4967.9   51.16  5032.1   51.16  5033.6   54.16  5035.9   57.95  5085.9   58.78
  5135.9   57.05  5225.9   56.82  5265.9    58.3  5345.9   56.81  5395.9   57.12
  5405.9   58.34  5425.9   57.01  5555.9    56.8  5975.9   56.89  6095.9   57.91
  6425.9   69.26  6465.9   72.23  6555.9    73.7  6725.9      80    6832   82.53
#Mann= 3 ,-1,0
  4038.7     .15       0  4966.4    .045       0  5033.6     .15       0
Bank Sta=4966.4,5033.6
XS Rating Curve= 0 ,0
Exp/Cntr=0.3,0.1

Type RM Length L Ch R = 1 ,40130   ,500,500,500
BEGIN DESCRIPTION:
Indian Field Swamp 80.0
END DESCRIPTION:
XS GIS Cut Line= 3
      2154897.33         480063.      2154094.88         479930.
      2152584.98       479643.73
#Sta/Elev= 30
  4186.6   71.81  4296.6    71.6  4346.6   70.09  4366.6   68.09  4406.6   59.74
  4436.6   57.83  4496.6   55.99  4666.6   56.18  4966.4   53.82  4967.9   50.82
  5032.1   50.82  5033.6   53.82    5070   56.51    5110   56.28    5140   57.23
    5150   56.24    5360   57.29    5460   56.62    5510   57.66    5540   56.73
    5830   56.86    5910   58.06    5940   56.78    6040   57.02    6110   59.38
    6200   64.09    6250   72.38    6300   76.66    6340    76.8  6536.8   82.84
#Mann= 3 ,-1,0
  4186.6     .15       0  4966.4    .045       0  5033.6     .15       0
Bank Sta=4966.4,5033.6
XS Rating Curve= 0 ,0
Exp/Cntr=0.3,0.1

Type RM Length L Ch R = 1 ,39630   ,610,610,610
BEGIN DESCRIPTION:
Indian Field Swamp 79.0
END DESCRIPTION:
XS GIS Cut Line= 3
      2154838.05       479584.43       2154209.4       479443.29
      2152623.09       479105.86
#Sta/Elev= 30
  4355.7   70.24  4435.7   68.85  4485.7   66.19  4545.7   57.83  4575.7    55.5
  4595.7   55.49  4605.7   56.52  4615.7    55.8  4705.7   55.62  4765.7    56.9
  4805.7   55.89  4955.7    56.4  4966.4   53.49  4967.9   50.49  5032.1   50.49
  5033.6   53.49    5070    56.2    5090   56.74    5110   56.07    5590   56.39
    5610   57.05    5650   56.41    5990   56.79    6060    58.9    6090   61.11
    6120   62.11    6370   67.15    6390   69.23    6510   73.92  6621.8   76.36
#Mann= 3 ,-1,0
  4355.7     .15       0  4966.4    .045       0  5033.6     .15       0
Bank Sta=4966.4,5033.6
XS Rating Curve= 0 ,0
Exp/Cntr=0.3,0.1

Type RM Length L Ch R = 1 ,39019   ,457,457,457
BEGIN DESCRIPTION:
Indian Field Swamp 78.0
END DESCRIPTION:
XS GIS Cut Line= 3
      2155134.69       479109.07      2154295.96       478839.03
      2152843.26       478407.04
#Sta/Elev= 30
  4118.1   67.03  4168.1   67.51  4308.1   66.36  4368.1   63.48  4408.1   60.22
  4418.1   57.86  4438.1   56.04  4458.1   55.42  4568.1   55.41  4598.1   56.54
  4628.1   55.63  4658.1   56.33  4748.1    55.4  4928.1    55.9  4958.1   55.57
  4966.4   53.28  4967.9   50.28  5032.1   50.28  5033.6   53.28  5079.2   55.47
  5129.2    56.2  5179.2   55.35  5189.2   56.12  5429.2    55.5  5979.2   56.74
  6049.2   58.25  6139.2   64.29  6329.2   71.22  6359.2   73.33  6514.8    74.9
#Mann= 3 ,-1,0
  4118.1     .15       0  4966.4    .045       0  5033.6     .15       0
Bank Sta=4966.4,5033.6
XS Rating Curve= 0 ,0
Exp/Cntr=0.3,0.1

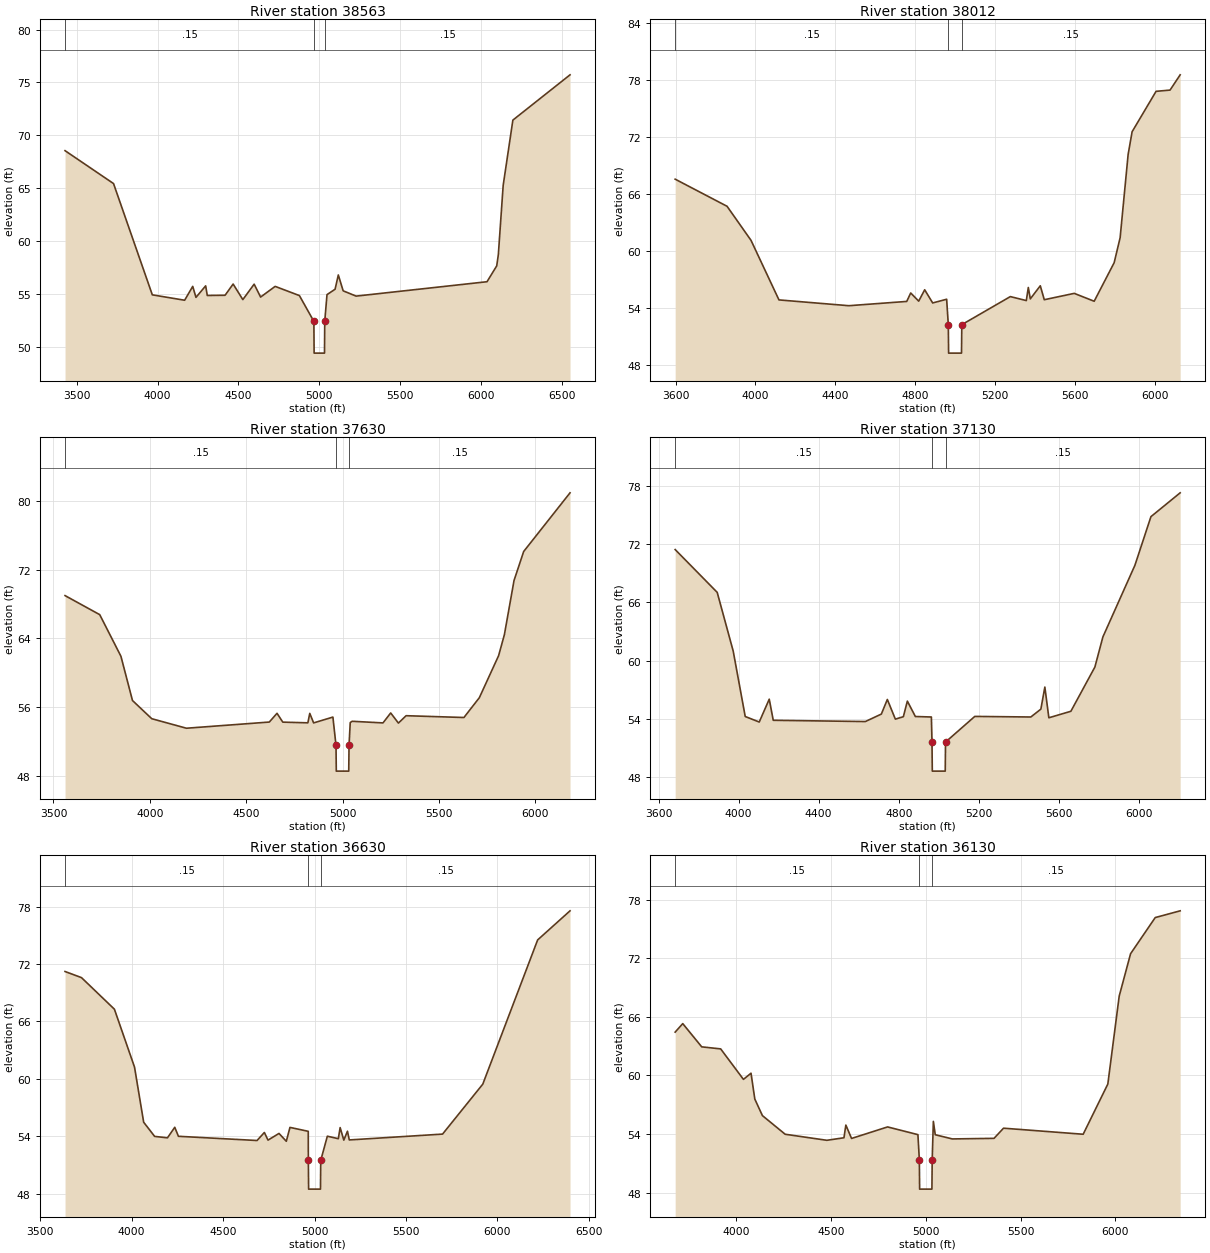
Type RM Length L Ch R = 1 ,38563   ,550,550,550
BEGIN DESCRIPTION:
Indian Field Swamp 77.0
END DESCRIPTION:
XS GIS Cut Line= 3
      2155968.48       478596.65      2154410.31       478398.57
      2152932.26       477920.01
#Sta/Elev= 30
  3426.9   68.55  3726.9   65.44  3966.9   54.92  4166.9   54.41  4216.9   55.72
  4236.9   54.68  4296.9   55.77  4306.9   54.86  4416.9   54.88  4466.9   55.94
  4526.9   54.47  4596.9   55.93  4636.9   54.71  4726.9   55.72  4876.9   54.85
  4966.4   52.41  4967.9   49.41  5032.1   49.41  5033.6   52.41  5047.6   54.94
  5097.6   55.45  5117.6    56.8  5147.6    55.3  5227.6    54.8  6037.6   56.16
  6097.6   57.66  6107.6   58.71  6137.6   65.27  6197.6   71.44  6551.2   75.72
#Mann= 3 ,-1,0
  3426.9     .15       0  4966.4    .045       0  5033.6     .15       0
Bank Sta=4966.4,5033.6
XS Rating Curve= 0 ,0
Exp/Cntr=0.3,0.1

Type RM Length L Ch R = 1 ,38012   ,383,383,383
BEGIN DESCRIPTION:
Indian Field Swamp 76.0
END DESCRIPTION:
XS GIS Cut Line= 3
      2155948.11       478381.09      2154634.77       477898.82
      2153622.59       477394.84
#Sta/Elev= 30
  3597.9   67.54  3857.9   64.68  3977.9   61.09  4117.9   54.81  4467.9    54.2
  4757.9   54.65  4777.9   55.54  4817.9   54.68  4847.9   55.88  4887.9   54.49
  4957.9   54.88  4966.2    52.2  4967.7    49.2  5032.3    49.2  5033.8    52.2
    5277   55.16    5357   54.74    5367   56.12    5377   54.92    5427    56.3
    5447   54.83    5597    55.5    5697   54.67    5797   58.73    5827   61.37
    5867   70.14    5887   72.54    6007    76.8    6077   76.93  6127.7   78.54
#Mann= 3 ,-1,0
  3597.9     .15       0  4966.2    .045       0  5033.8     .15       0
Bank Sta=4966.2,5033.8
XS Rating Curve= 0 ,0
Exp/Cntr=0.3,0.1

Type RM Length L Ch R = 1 ,37630   ,500,500,500
BEGIN DESCRIPTION:
Indian Field Swamp 75.0
END DESCRIPTION:
XS GIS Cut Line= 3
      2156180.59       477996.22      2154808.87        477558.4
      2153775.06       476988.27
#Sta/Elev= 30
  3560.1      69  3740.1   66.78  3850.1   61.93  3910.1   56.77  4010.1   54.65
  4190.1   53.54  4620.1   54.26  4660.1   55.28  4690.1   54.25  4820.1   54.17
  4830.1   55.27  4850.1   54.16  4950.1   54.84  4966.2   51.54  4967.7   48.54
  5032.3   48.54  5033.8   51.54    5040    54.2    5050   54.35    5210   54.16
    5250   55.32    5290   54.14    5330      55    5630   54.79    5710    57.1
    5810      62    5840   64.45    5890   70.76    5940   74.14  6180.6   80.98
#Mann= 3 ,-1,0
  3560.1     .15       0  4966.2    .045       0  5033.8     .15       0
Bank Sta=4966.2,5033.8
XS Rating Curve= 0 ,0
Exp/Cntr=0.3,0.1

Type RM Length L Ch R = 1 ,37130   ,500,500,500
BEGIN DESCRIPTION:
Indian Field Swamp 74.0
END DESCRIPTION:
XS GIS Cut Line= 3
      2156223.02       477708.26      2155045.77       477118.08
      2153965.63       476581.68
#Sta/Elev= 30
  3683.1   71.46  3893.1   67.04  3973.1   60.97  4033.1   54.22  4103.1   53.65
  4153.1   56.01  4173.1   53.83  4633.1    53.7  4713.1   54.47  4743.1   55.98
  4783.1   53.95  4823.1    54.2  4843.1   55.81  4883.1   54.22  4963.1   54.17
  4966.2   51.58  4967.7   48.58  5032.3   48.58  5033.8   51.58    5180   54.23
    5460   54.17    5510   54.98    5530   57.26    5550   54.09    5660   54.76
    5780   59.33    5820   62.44    5980   69.84    6060   74.86    6206   77.32
#Mann= 3 ,-1,0
  3683.1     .15       0  4966.2    .045       0  5033.8     .15       0
Bank Sta=4966.2,5033.8
XS Rating Curve= 0 ,0
Exp/Cntr=0.3,0.1

Type RM Length L Ch R = 1 ,36630   ,500,500,500
BEGIN DESCRIPTION:
Indian Field Swamp 73.0
END DESCRIPTION:
XS GIS Cut Line= 3
      2156502.52       477288.96      2155282.67       476677.77
       2154033.4       476052.28
#Sta/Elev= 30
  3635.6   71.22  3725.6   70.58  3905.6   67.28  4015.6   61.23  4065.6   55.47
  4125.6   53.99  4195.6   53.84  4235.6   54.94  4255.6      54  4685.6   53.56
  4725.6    54.4  4745.6    53.6  4805.6    54.3  4845.6   53.48  4865.6   54.93
  4965.6   54.52  4966.1   51.48  4967.6   48.48  5032.4   48.48  5033.9   51.48
    5070   54.01    5130   53.75    5140   54.91    5160    53.6    5180   54.53
    5190   53.62    5700   54.23    5920   59.45    6220   74.52  6397.1   77.56
#Mann= 3 ,-1,0
  3635.6     .15       0  4966.1    .045       0  5033.9     .15       0
Bank Sta=4966.1,5033.9
XS Rating Curve= 0 ,0
Exp/Cntr=0.3,0.1

Type RM Length L Ch R = 1 ,36130   ,500,500,500
BEGIN DESCRIPTION:
Indian Field Swamp 72.0
END DESCRIPTION:
XS GIS Cut Line= 3
      2156650.74       476920.49      2155519.57       476237.45
      2154346.76       475586.39
#Sta/Elev= 30
  3678.6   64.44  3718.6   65.31  3818.6   62.93  3918.6   62.72  4038.6    59.6
  4078.6   60.23  4098.6   57.58  4138.6   55.89  4258.6   53.98  4478.6   53.36
  4568.6   53.62  4578.6   54.92  4608.6   53.55  4798.6   54.73  4958.6   53.94
  4966.1   51.36  4967.6   48.36  5032.4   48.36  5033.9   51.36    5040    55.3
    5050   53.93    5140    53.5    5360   53.56    5410    54.6    5830   53.98
    5960   59.12    6020   68.13    6080   72.47    6210   76.17  6341.4   76.86
#Mann= 3 ,-1,0
  3678.6     .15       0  4966.1    .045       0  5033.9     .15       0
Bank Sta=4966.1,5033.9
XS Rating Curve= 0 ,0
Exp/Cntr=0.3,0.1

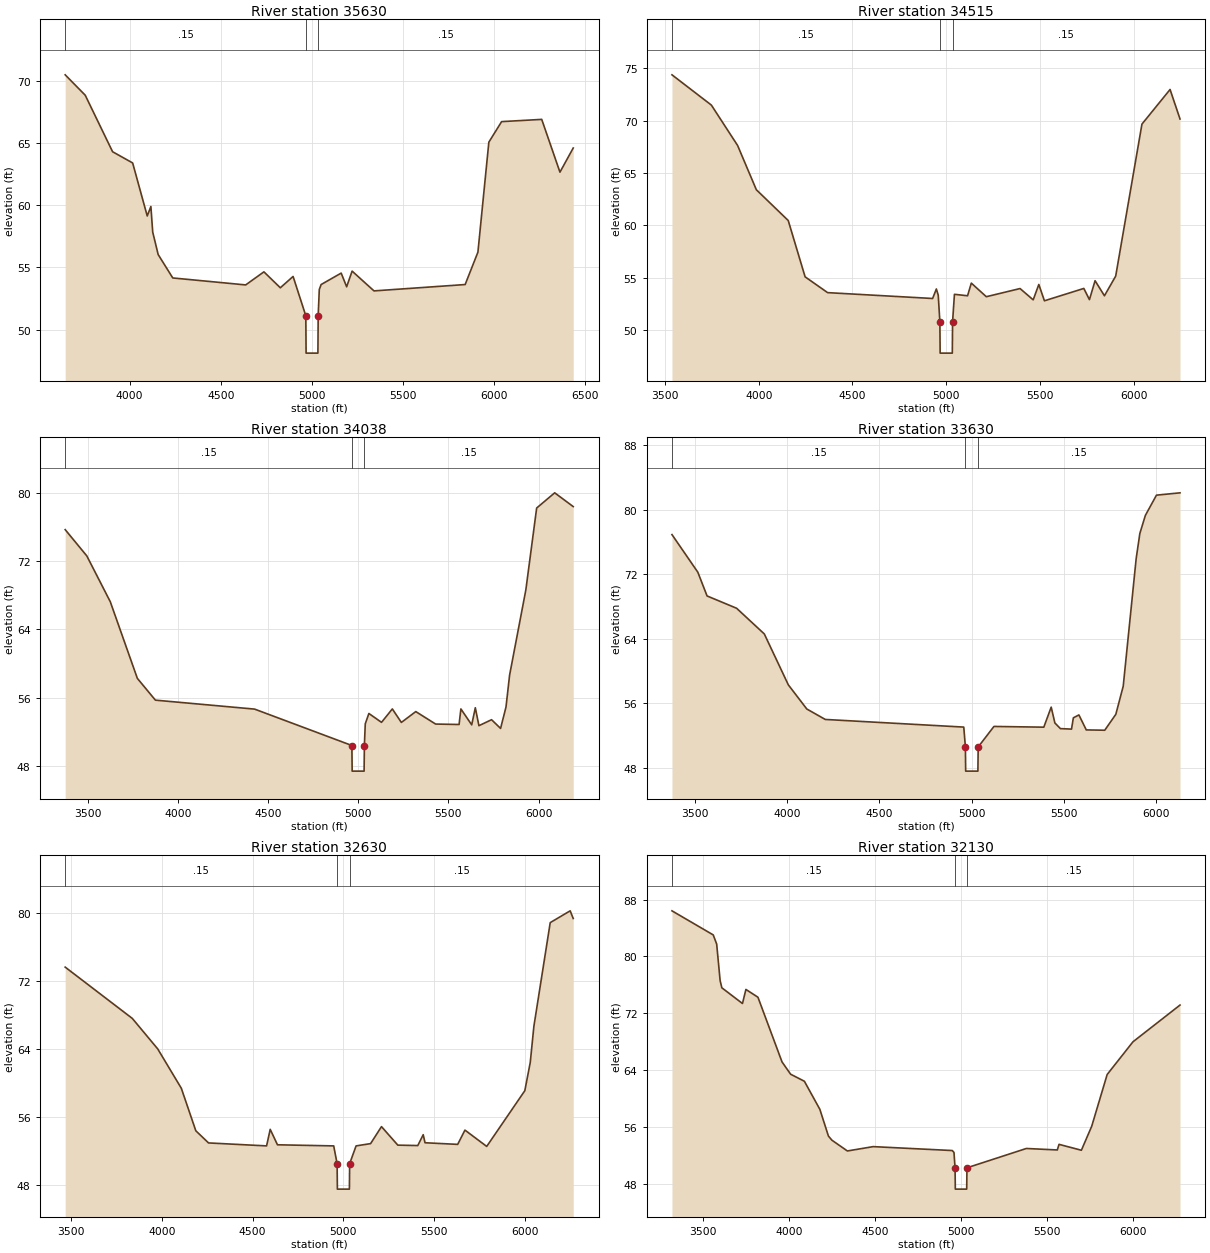
Type RM Length L Ch R = 1 ,35630   ,500,500,500
BEGIN DESCRIPTION:
Indian Field Swamp 71.0
END DESCRIPTION:
XS GIS Cut Line= 3
      2156930.21       476471.53      2155756.47       475797.13
       2154473.8       475158.62
#Sta/Elev= 30
  3646.3   70.48  3756.3   68.84  3906.3    64.3  4016.3    63.4  4096.3   59.14
  4116.3    59.9  4126.3   57.85  4156.3   56.04  4236.3   54.16  4636.3    53.6
  4736.3   54.65  4826.3   53.37  4896.3   54.28  4966.1   51.12  4967.6   48.12
  5032.4   48.12  5033.9   51.12    5040   53.23    5050   53.63    5160   54.55
    5190   53.45    5220   54.71    5340   53.12    5840   53.63    5910   56.23
    5970   65.07    6040   66.72    6260    66.9    6360   62.66  6432.8    64.6
#Mann= 3 ,-1,0
  3646.3     .15       0  4966.1    .045       0  5033.9     .15       0
Bank Sta=4966.1,5033.9
XS Rating Curve= 0 ,0
Exp/Cntr=0.3,0.1

Type RM Length L Ch R = 1 ,34515   ,477,477,477
BEGIN DESCRIPTION:
Indian Field Swamp 69.0
END DESCRIPTION:
XS GIS Cut Line= 3
      2157562.66       475383.73       2156232.8       474789.97
      2155083.68       474290.41
#Sta/Elev= 30
  3537.4   74.39  3747.4    71.5  3887.4   67.64  3987.4   63.41  4157.4   60.47
  4247.4   55.09  4367.4   53.58  4927.4   53.02  4947.4   53.93  4957.4   53.34
  4966.1    50.8  4967.6    47.8  5032.4    47.8  5033.9    50.8  5043.8   53.42
  5113.8   53.28  5133.8   54.49  5213.8   53.19  5393.8   53.97  5463.8   52.89
  5493.8   54.36  5523.8    52.8  5733.8   53.98  5763.8   52.91  5793.8   54.72
  5843.8   53.28  5903.8   55.16  6043.8   69.68  6193.8   72.99  6246.8   70.17
#Mann= 3 ,-1,0
  3537.4     .15       0  4966.1    .045       0  5033.9     .15       0
Bank Sta=4966.1,5033.9
XS Rating Curve= 0 ,0
Exp/Cntr=0.3,0.1

Type RM Length L Ch R = 1 ,34038   ,409,409,409
BEGIN DESCRIPTION:
Indian Field Swamp 68.0
END DESCRIPTION:
XS GIS Cut Line= 3
      2157857.73       473972.79       2156273.8       474328.54
      2155096.41       474137.96
#Sta/Elev= 30
  3376.2   75.67  3496.2   72.59  3626.2   67.23  3776.2   58.26  3876.2   55.71
  4426.2   54.66  4965.4    50.4  4966.9    47.4  5033.1    47.4  5034.6    50.4
  5039.6   52.94  5059.6   54.15  5129.6   53.11  5189.6   54.68  5239.6    53.1
  5319.6   54.37  5429.6   52.91  5559.6   52.86  5569.6   54.68  5629.6   52.82
  5649.6   54.82  5669.6   52.72  5739.6   53.42  5789.6    52.4  5819.6    54.9
  5839.6   58.64  5929.6   68.61  5989.6    78.2  6089.6   79.98  6192.3   78.37
#Mann= 3 ,-1,0
  3376.2     .15       0  4965.4    .045       0  5034.6     .15       0
Bank Sta=4965.4,5034.6
XS Rating Curve= 0 ,0
Exp/Cntr=0.3,0.1

Type RM Length L Ch R = 1 ,33630   ,500,500,500
BEGIN DESCRIPTION:
Indian Field Swamp 67.0
END DESCRIPTION:
XS GIS Cut Line= 3
      2157806.93       473545.03      2156228.11       473922.83
      2155100.61       473921.96
#Sta/Elev= 30
  3376.6   76.93  3516.6   72.26  3566.6   69.31  3726.6   67.78  3876.6   64.59
  4006.6   58.27  4106.6   55.27  4206.6   53.97  4956.6   53.02  4965.4   50.55
  4966.9   47.55  5033.1   47.55  5034.6   50.55    5120    53.1    5390   53.01
    5430    55.5    5450   53.53    5480   52.83    5540   52.77    5550   54.17
    5580   54.53    5620   52.67    5720   52.63    5780   54.61    5820    58.1
    5890   73.93    5910   77.07    5940   79.32    6000   81.83  6127.5   82.12
#Mann= 3 ,-1,0
  3376.6     .15       0  4965.4    .045       0  5034.6     .15       0
Bank Sta=4965.4,5034.6
XS Rating Curve= 0 ,0
Exp/Cntr=0.3,0.1

Type RM Length L Ch R = 1 ,32630   ,500,500,500
BEGIN DESCRIPTION:
Indian Field Swamp 65.0
END DESCRIPTION:
XS GIS Cut Line= 3
       2157396.1       472376.12      2155978.79       472961.14
      2154812.67       473456.08
#Sta/Elev= 30
  3466.7   73.65  3836.7   67.61  3976.7   64.02  4106.7   59.39  4186.7   54.38
  4256.7   52.95  4576.7    52.6  4596.7   54.55  4636.7   52.73  4946.7    52.6
  4965.4   50.51  4966.9   47.51  5033.1   47.51  5034.6   50.51    5070    52.6
    5150   52.87    5210   54.87    5300   52.69    5410   52.64    5440   53.92
    5450   52.97    5630   52.78    5670   54.46    5790   52.54    6000    59.1
    6030   62.43    6050   66.69    6140   78.89    6250   80.28  6266.8   79.38
#Mann= 3 ,-1,0
  3466.7     .15       0  4965.4    .045       0  5034.6     .15       0
Bank Sta=4965.4,5034.6
XS Rating Curve= 0 ,0
Exp/Cntr=0.3,0.1

Type RM Length L Ch R = 1 ,32130   ,500,500,500
BEGIN DESCRIPTION:
Indian Field Swamp 64.0
END DESCRIPTION:
XS GIS Cut Line= 3
       2157319.9       471855.18      2155770.38       472506.65
      2154630.58        473074.9
#Sta/Elev= 30
  3319.1   86.41  3559.1   83.02  3579.1   81.73  3599.1    76.6  3609.1   75.58
  3729.1   73.37  3749.1   75.35  3819.1   74.25  3959.1   65.15  4009.1   63.42
  4089.1   62.43  4179.1   58.48  4229.1   54.71  4249.1   54.14  4339.1   52.62
  4489.1   53.23  4949.1   52.68  4959.1   52.41  4965.4   50.25  4966.9   47.25
  5033.1   47.25  5034.6   50.25    5380   52.97    5560   52.76    5570   53.55
    5700   52.72    5760   56.09    5850   63.38    6000   67.98  6273.6   73.15
#Mann= 3 ,-1,0
  3319.1     .15       0  4965.4    .045       0  5034.6     .15       0
Bank Sta=4965.4,5034.6
XS Rating Curve= 0 ,0
Exp/Cntr=0.3,0.1

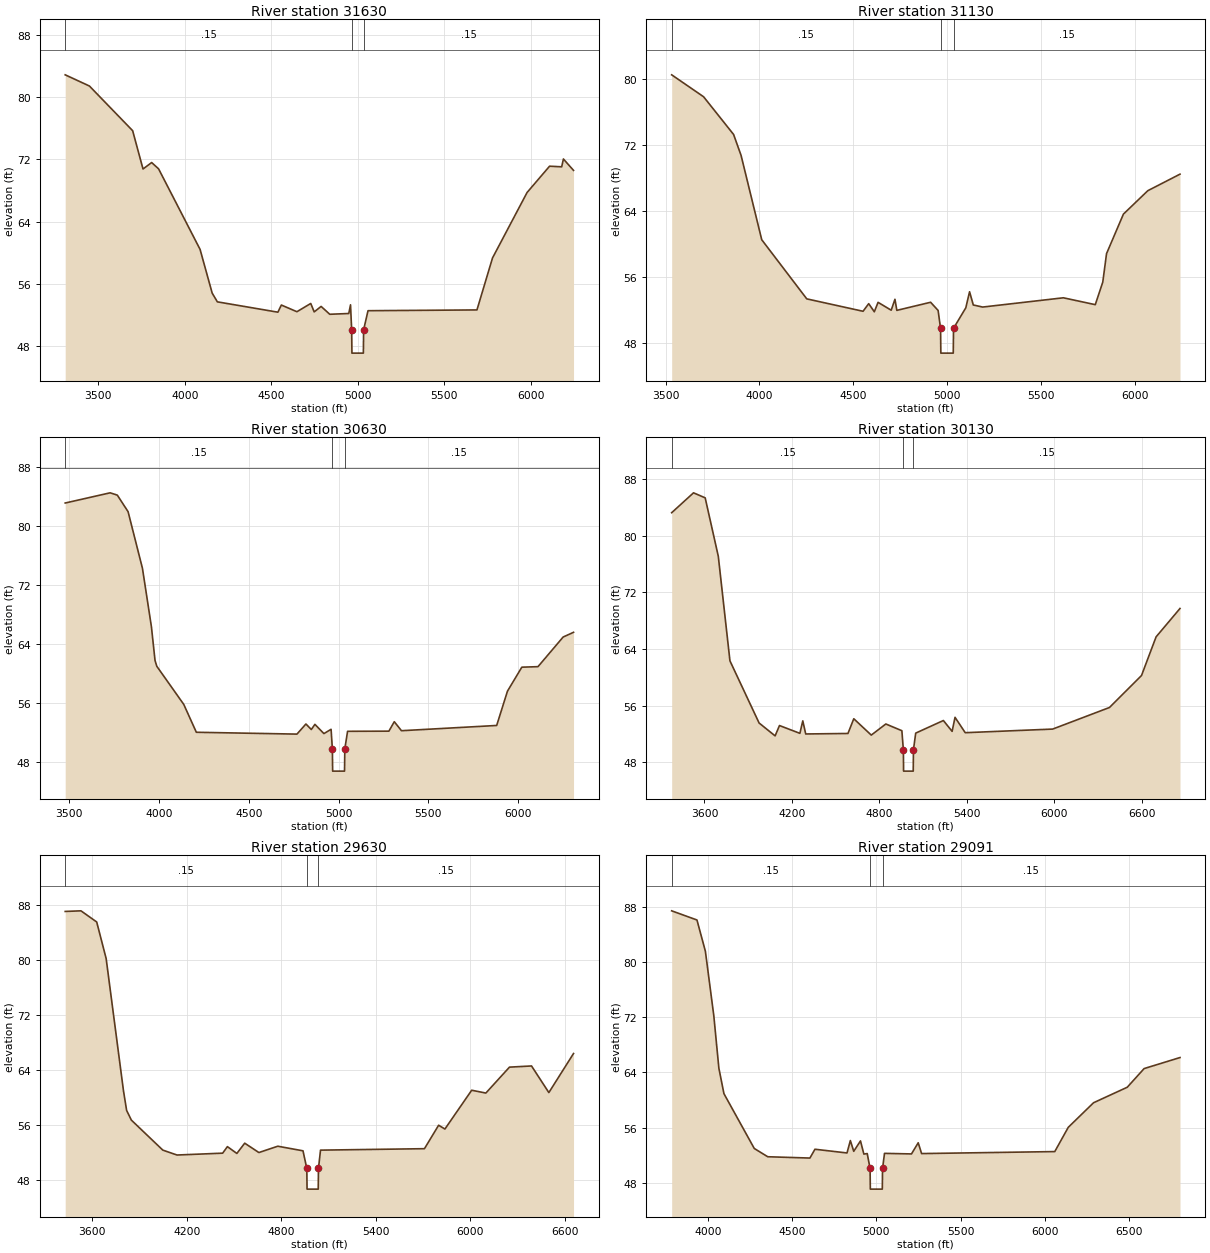
Type RM Length L Ch R = 1 ,31630   ,500,500,500
BEGIN DESCRIPTION:
Indian Field Swamp 63.0
END DESCRIPTION:
XS GIS Cut Line= 3
      2157171.62       471533.32      2155561.97       472052.15
      2154588.19       472833.51
#Sta/Elev= 30
  3308.8   82.88  3448.8   81.44  3698.8   75.69  3758.8   70.76  3808.8   71.59
  3848.8   70.78  4088.8   60.41  4158.8   54.78  4188.8   53.66  4538.8   52.33
  4558.8   53.25  4648.8   52.39  4728.8   53.45  4748.8   52.37  4788.8   53.07
  4838.8   52.06  4948.8   52.16  4958.8   53.28  4965.4   50.06  4966.9   47.06
  5033.1   47.06  5034.6   50.06    5060   52.52    5690   52.62    5780   59.31
    5980   67.74    6110   71.12    6180   71.04    6190   72.05  6248.5   70.58
#Mann= 3 ,-1,0
  3308.8     .15       0  4965.4    .045       0  5034.6     .15       0
Bank Sta=4965.4,5034.6
XS Rating Curve= 0 ,0
Exp/Cntr=0.3,0.1

Type RM Length L Ch R = 1 ,31130   ,500,500,500
BEGIN DESCRIPTION:
Indian Field Swamp 62.0
END DESCRIPTION:
XS GIS Cut Line= 3
      2156578.73       470868.38      2155318.35       471620.24
      2154545.83       472592.11
#Sta/Elev= 30
  3532.4   80.48  3702.4   77.83  3862.4   73.27  3902.4   70.73  4012.4   60.54
  4252.4   53.39  4552.4   51.89  4582.4   52.81  4612.4   51.83  4632.4   52.97
  4702.4   52.02  4722.4   53.34  4732.4      52  4912.4   52.98  4952.4   51.99
  4965.4   49.83  4966.9   46.83  5033.1   46.83  5034.6   49.83    5100   52.31
    5120   54.25    5140   52.65    5190    52.4    5620   53.52    5790   52.69
    5830   55.42    5850   58.86    5940   63.64    6070   66.47  6241.5   68.47
#Mann= 3 ,-1,0
  3532.4     .15       0  4965.4    .045       0  5034.6     .15       0
Bank Sta=4965.4,5034.6
XS Rating Curve= 0 ,0
Exp/Cntr=0.3,0.1

Type RM Length L Ch R = 1 ,30630   ,500,500,500
BEGIN DESCRIPTION:
Indian Field Swamp 61.0
END DESCRIPTION:
XS GIS Cut Line= 3
      2156299.23       470461.79      2154992.21       471241.25
      2154467.73       472439.28
#Sta/Elev= 30
  3478.2   83.09  3728.2   84.47  3768.2   84.16  3828.2   81.92  3908.2   74.25
  3958.2   66.33  3978.2   61.78  3988.2   60.99  4138.2   55.83  4208.2   52.06
  4768.2   51.81  4818.2   53.18  4848.2   52.43  4868.2   53.13  4918.2   51.88
  4958.2   52.46  4965.4    49.8  4966.9    46.8  5033.1    46.8  5034.6    49.8
    5050   52.19    5280   52.21    5310   53.49    5350   52.27    5880   52.98
    5940   57.62    6020   60.87    6110   60.94    6250   64.95  6307.8   65.59
#Mann= 3 ,-1,0
  3478.2     .15       0  4965.4    .045       0  5034.6     .15       0
Bank Sta=4965.4,5034.6
XS Rating Curve= 0 ,0
Exp/Cntr=0.3,0.1

Type RM Length L Ch R = 1 ,30130   ,500,500,500
BEGIN DESCRIPTION:
Indian Field Swamp 60.0
END DESCRIPTION:
XS GIS Cut Line= 3
      2156072.21       470128.79      2154637.23       470891.11
      2153703.17        472504.3
#Sta/Elev= 30
  3375.1   83.27  3525.1   86.08  3605.1   85.37  3695.1   77.12  3775.1   62.34
  3975.1   53.56  4085.1   51.74  4115.1    53.2  4255.1    52.1  4275.1   53.86
  4295.1   52.01  4585.1   52.08  4625.1   54.16  4745.1   51.85  4845.1   53.42
  4955.1   52.47  4965.4   49.76  4966.9   46.76  5033.1   46.76  5034.6   49.76
    5050   52.13    5240   53.91    5300   52.38    5320   54.36    5390   52.19
    5990    52.7    6380   55.75    6600   60.27    6700   65.73  6864.1   69.74
#Mann= 3 ,-1,0
  3375.1     .15       0  4965.4    .045       0  5034.6     .15       0
Bank Sta=4965.4,5034.6
XS Rating Curve= 0 ,0
Exp/Cntr=0.3,0.1

Type RM Length L Ch R = 1 ,29630   ,538,538,538
BEGIN DESCRIPTION:
Indian Field Swamp 59.0
END DESCRIPTION:
XS GIS Cut Line= 3
      2155853.86       469864.95      2154411.07       470487.33
       2152819.6       470947.63
#Sta/Elev= 30
  3428.7   87.07  3528.7   87.16  3628.7   85.54  3688.7   80.22  3798.7      61
  3818.7   58.14  3848.7   56.73  4048.7   52.36  4138.7   51.65  4428.7   51.92
  4458.7   52.87  4518.7   51.88  4568.7   53.37  4658.7   52.01  4778.7   52.93
  4938.7   52.26    4963   49.69  4964.5   46.69  5035.5   46.69    5037   49.69
    5050   52.36    5710   52.57    5800   55.98    5840   55.43    6010   61.07
    6100   60.66    6250   64.43    6390    64.6    6500   60.73  6656.7   66.41
#Mann= 3 ,-1,0
  3428.7     .15       0    4963    .045       0    5037     .15       0
Bank Sta=4963,5037
XS Rating Curve= 0 ,0
Exp/Cntr=0.3,0.1

Type RM Length L Ch R = 1 ,29091   ,462,462,462
BEGIN DESCRIPTION:
Indian Field Swamp 58.0
END DESCRIPTION:
XS GIS Cut Line= 3
      2155726.52       469614.74      2154564.99       469995.96
      2152842.37       470492.72
#Sta/Elev= 30
  3786.1   87.46  3936.1   86.13  3986.1   81.59  4036.1   72.22  4066.1   64.61
  4096.1   60.92  4276.1   52.96  4356.1   51.76  4606.1   51.57  4636.1   52.85
  4826.1   52.31  4846.1   54.11  4866.1   52.55  4906.1   54.06  4926.1   52.15
  4946.1   52.22    4963   50.06  4964.5   47.06  5035.5   47.06    5037   50.06
  5048.6   52.25  5208.6   52.17  5248.6   53.79  5268.6   52.22  6058.6   52.51
  6138.6   56.03  6288.6    59.6  6488.6   61.85  6588.6   64.56  6801.4   66.16
#Mann= 3 ,-1,0
  3786.1     .15       0    4963    .045       0    5037     .15       0
Bank Sta=4963,5037
XS Rating Curve= 0 ,0
Exp/Cntr=0.3,0.1