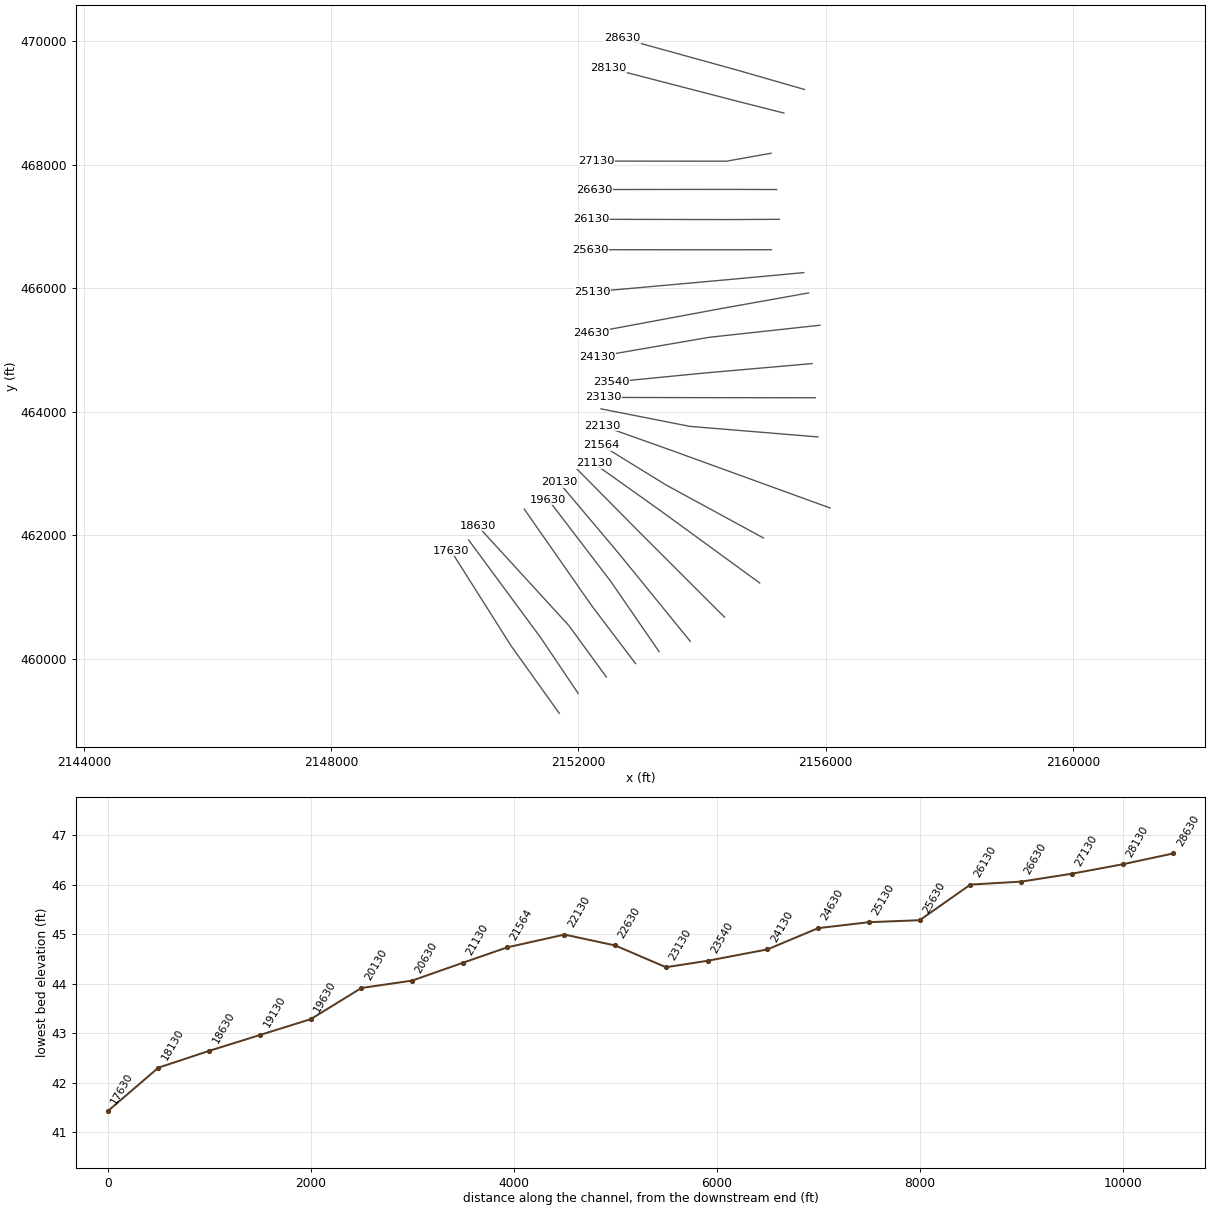
HEC-RAS study IndianFieldsSwamp.prj: S-18-19 over Indian Fields Swamp

--- IndianFieldsSwamp.g14 (geometry) --- (continued)

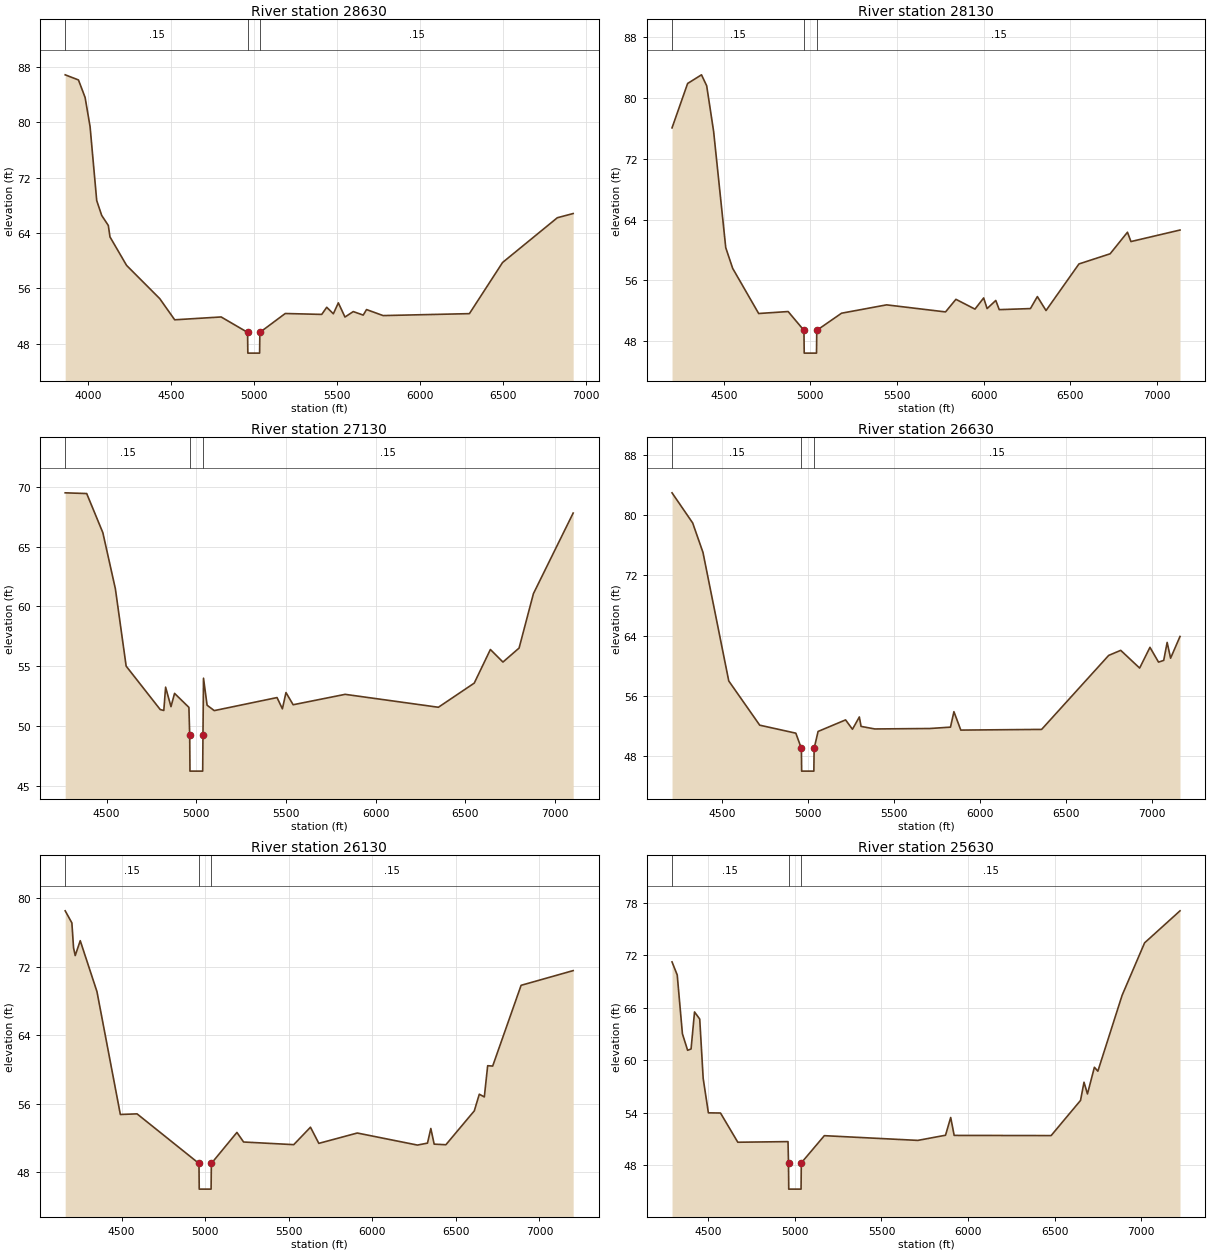
Type RM Length L Ch R = 1 ,28630   ,500,500,500
BEGIN DESCRIPTION:
Indian Field Swamp 57.0
END DESCRIPTION:
XS GIS Cut Line= 3
      2155658.26       469218.98      2154566.25       469533.51
      2152710.46       470046.91
#Sta/Elev= 30
  3863.6   86.88  3943.6   86.14  3983.6   83.61  4013.6   79.39  4053.6    68.7
  4083.6   66.55  4123.6   65.09  4133.6   63.44  4233.6   59.32  4433.6   54.51
  4523.6   51.45  4803.6   51.86    4963   49.63  4964.5   46.63  5035.5   46.63
    5037   49.63    5190   52.36    5410   52.23    5440   53.26    5480   52.32
    5510    53.9    5550   51.85    5600   52.64    5660   52.13    5680   52.93
    5780   52.06    6300   52.34    6500   59.74    6830   66.21  6925.5   66.82
#Mann= 3 ,-1,0
  3863.6     .15       0    4963    .045       0    5037     .15       0
Bank Sta=4963,5037
XS Rating Curve= 0 ,0
Exp/Cntr=0.3,0.1

Type RM Length L Ch R = 1 ,28130   ,500,500,500
BEGIN DESCRIPTION:
Indian Field Swamp 56.0
END DESCRIPTION:
XS GIS Cut Line= 3
      2155326.13       468836.87      2154552.49       469033.73
       2152487.6       469569.25
#Sta/Elev= 30
  4201.7   76.09  4291.7   81.94  4371.7   83.08  4401.7   81.64  4441.7   75.63
  4511.7   60.31  4551.7   57.58  4701.7   51.63  4871.7   51.89    4963   49.41
  4964.5   46.41  5035.5   46.41    5037   49.41    5180   51.67    5440   52.77
    5780   51.84    5840    53.5    5950   52.21    6000   53.68    6020   52.28
    6070   53.35    6090   52.14    6270   52.28    6310   53.86    6360   52.02
    6550   58.16    6730    59.5    6830   62.34    6850   61.11  7133.2   62.63
#Mann= 3 ,-1,0
  4201.7     .15       0    4963    .045       0    5037     .15       0
Bank Sta=4963,5037
XS Rating Curve= 0 ,0
Exp/Cntr=0.3,0.1

Type RM Length L Ch R = 1 ,27130   ,500,500,500
BEGIN DESCRIPTION:
Indian Field Swamp 54.0
END DESCRIPTION:
XS GIS Cut Line= 3
      2155118.16       468186.44      2154398.15        468057.9
      2152296.45       468059.38
#Sta/Elev= 30
  4268.6   69.49  4388.6   69.43  4478.6   66.16  4548.6   61.46  4608.6      55
  4798.6   51.37  4818.6   51.29  4828.6   53.24  4858.6   51.61  4878.6   52.72
  4958.6   51.55    4963   49.22  4964.5   46.22  5035.5   46.22    5037   49.22
    5040   53.99    5060   51.73    5100   51.28    5450   52.37    5480   51.43
    5500   52.79    5540   51.77    5830   52.64    6350   51.56    6550   53.58
    6640   56.39    6710   55.34    6800   56.51    6880   61.06  7101.7    67.8
#Mann= 3 ,-1,0
  4268.6     .15       0    4963    .045       0    5037     .15       0
Bank Sta=4963,5037
XS Rating Curve= 0 ,0
Exp/Cntr=0.3,0.1

Type RM Length L Ch R = 1 ,26630   ,500,500,500
BEGIN DESCRIPTION:
Indian Field Swamp 53.0
END DESCRIPTION:
XS GIS Cut Line= 3
      2155208.16        467598.8      2154418.86       467601.35
      2152254.06        467598.8
#Sta/Elev= 30
  4210.7   82.95  4330.7   78.96  4390.7   75.05  4540.7   58.01  4720.7   52.15
  4930.7   51.09    4963   49.06  4964.5   46.06  5035.5   46.06    5037   49.06
    5060   51.32    5220   52.85    5260   51.61    5300   53.24    5310   51.99
    5390   51.65    5710   51.71    5830   51.89    5850   53.94    5890    51.5
    6360   51.59    6750    61.4    6820   62.07    6930   59.72    6990   62.47
    7040   60.51    7070   60.74    7090   63.12    7110   61.03  7164.8   63.91
#Mann= 3 ,-1,0
  4210.7     .15       0    4963    .045       0    5037     .15       0
Bank Sta=4963,5037
XS Rating Curve= 0 ,0
Exp/Cntr=0.3,0.1

Type RM Length L Ch R = 1 ,26130   ,500,500,500
BEGIN DESCRIPTION:
Indian Field Swamp 52.0
END DESCRIPTION:
XS GIS Cut Line= 3
      2155250.46       467117.04      2154413.18       467112.48
      2152211.68       467117.04
#Sta/Elev= 30
  4162.7   78.54  4202.7   77.13  4212.7   74.22  4222.7   73.31  4252.7   75.05
  4352.7    69.1  4492.7   54.73  4592.7    54.8    4963      49  4964.5      46
  5035.5      46    5037      49    5190   52.63    5230   51.51    5530    51.2
    5630   53.24    5680   51.35    5910   52.56    6270   51.15    6330   51.38
    6350   53.09    6370   51.26    6440   51.19    6610   55.15    6640    57.1
    6670   56.78    6690   60.43    6720   60.39    6890   69.83  7201.5   71.55
#Mann= 3 ,-1,0
  4162.7     .15       0    4963    .045       0    5037     .15       0
Bank Sta=4963,5037
XS Rating Curve= 0 ,0
Exp/Cntr=0.3,0.1

Type RM Length L Ch R = 1 ,25630   ,500,500,500
BEGIN DESCRIPTION:
Indian Field Swamp 51.0
END DESCRIPTION:
XS GIS Cut Line= 3
      2155124.97         466625.      2154415.17       466623.58
      2152190.57        466624.7
#Sta/Elev= 30
  4290.2   71.25  4320.2   69.76  4350.2   63.04  4380.2   61.15  4400.2    61.3
  4420.2   65.53  4450.2   64.72  4470.2   57.93  4500.2      54  4570.2   53.98
  4670.2   50.64  4960.2   50.71    4963   48.28  4964.5   45.28  5035.5   45.28
    5037   48.28    5170   51.39    5710   50.85    5870   51.44    5900   53.47
    5920   51.42    6480    51.4    6650   55.42    6670    57.5    6690   56.16
    6730   59.21    6750   58.76    6890   67.43    7020   73.43  7224.6   77.09
#Mann= 3 ,-1,0
  4290.2     .15       0    4963    .045       0    5037     .15       0
Bank Sta=4963,5037
XS Rating Curve= 0 ,0
Exp/Cntr=0.3,0.1

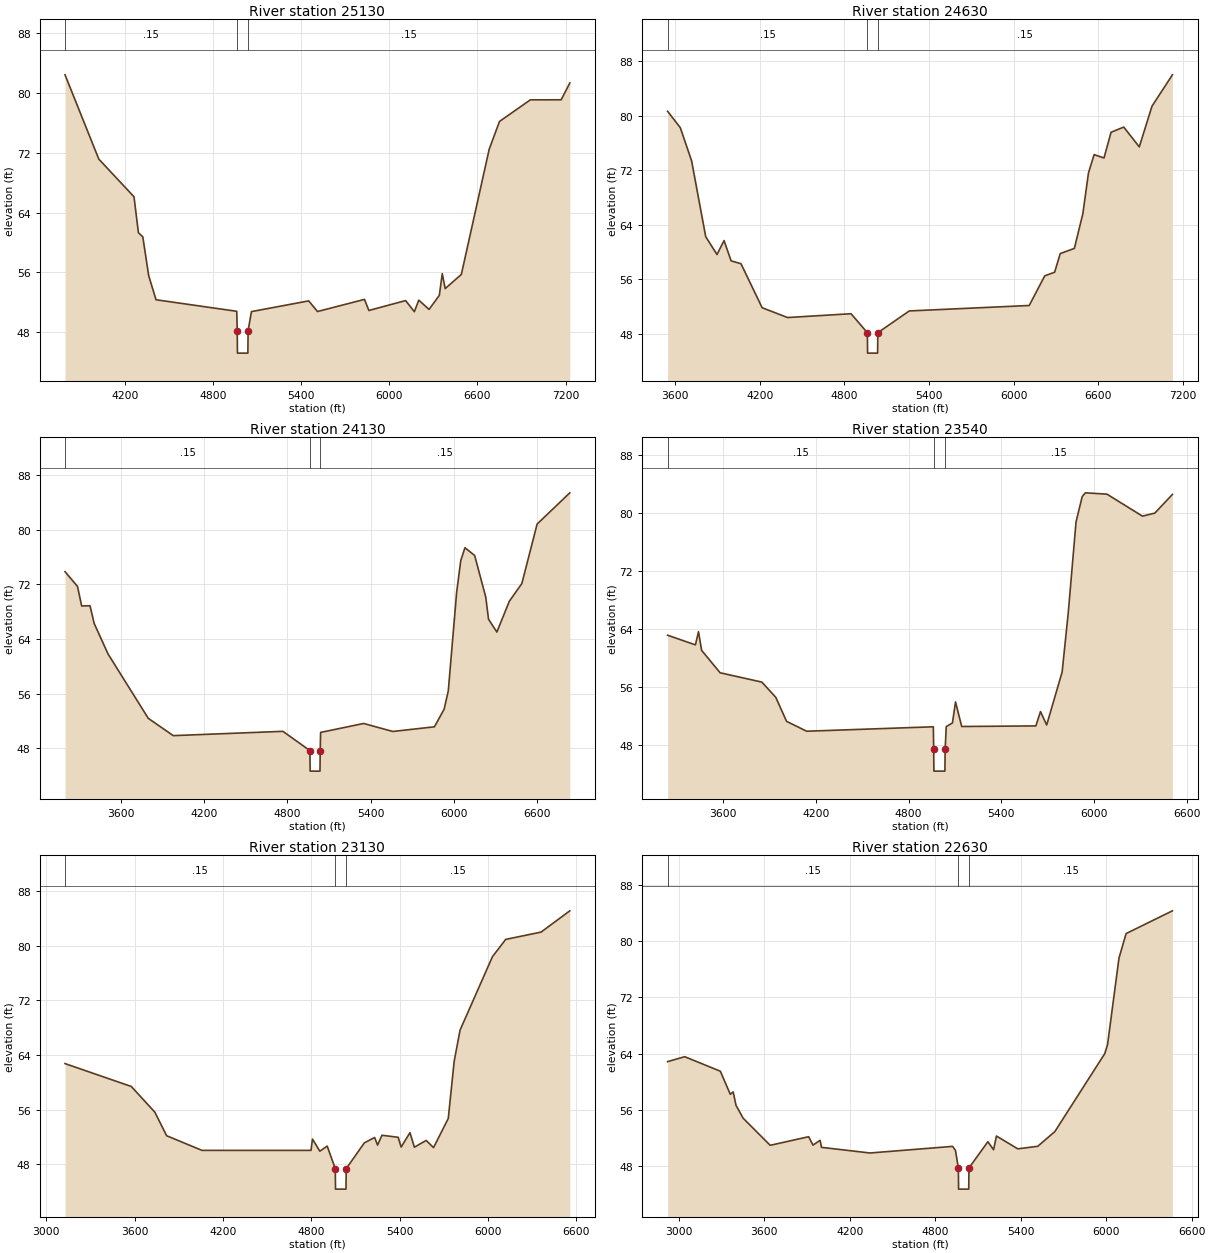
Type RM Length L Ch R = 1 ,25130   ,500,500,500
BEGIN DESCRIPTION:
Indian Field Swamp 50.0
END DESCRIPTION:
XS GIS Cut Line= 3
      2155647.51       466254.12      2154442.42       466141.91
      2152222.32       465941.78
#Sta/Elev= 30
  3789.7   82.37  4019.7   71.13  4259.7    66.1  4289.7   61.31  4319.7   60.75
  4359.7   55.58  4409.7   52.36  4959.7   50.82    4963   48.24  4964.5   45.24
  5035.5   45.24    5037   48.24    5060   50.78    5450   52.21    5510   50.79
    5830   52.41    5860   50.93    6110   52.25    6170   50.77    6200   52.31
    6270   51.07    6340   52.95    6360   55.84    6380   53.85    6490   55.74
    6680   72.46    6750   76.15    6960   79.03    7170   79.04  7229.1   81.28
#Mann= 3 ,-1,0
  3789.7     .15       0    4963    .045       0    5037     .15       0
Bank Sta=4963,5037
XS Rating Curve= 0 ,0
Exp/Cntr=0.3,0.1

Type RM Length L Ch R = 1 ,24630   ,500,500,500
BEGIN DESCRIPTION:
Indian Field Swamp 49.0
END DESCRIPTION:
XS GIS Cut Line= 3
      2155725.04       465925.01      2154295.15       465669.15
      2152206.39       465280.02
#Sta/Elev= 30
  3547.4   80.66  3637.4   78.25  3717.4   73.38  3817.4   62.24  3897.4   59.61
  3947.4   61.66  3997.4   58.68  4067.4   58.26  4217.4   51.79  4397.4   50.35
  4847.4   50.91    4963   48.12  4964.5   45.12  5035.5   45.12    5037   48.12
    5260   51.32    6110   52.12    6220   56.48    6290   57.01    6330   59.75
    6430   60.51    6490   65.61    6530   71.61    6570   74.29    6640    73.8
    6690   77.58    6780   78.34    6890   75.43    6980   81.41  7124.7   86.02
#Mann= 3 ,-1,0
  3547.4     .15       0    4963    .045       0    5037     .15       0
Bank Sta=4963,5037
XS Rating Curve= 0 ,0
Exp/Cntr=0.3,0.1

Type RM Length L Ch R = 1 ,24130   ,590,590,590
BEGIN DESCRIPTION:
Indian Field Swamp 48.0
END DESCRIPTION:
XS GIS Cut Line= 3
      2155906.93       465401.79      2154115.86       465206.39
      2152307.01       464893.56
#Sta/Elev= 30
  3198.3   73.86  3288.3    71.7  3318.3   68.84  3378.3   68.88  3408.3   66.29
  3508.3   61.82  3798.3   52.41  3978.3   49.88  4768.3   50.51    4963   47.69
  4964.5   44.69  5035.5   44.69    5037   47.69    5040   50.35    5350   51.66
    5560   50.49    5860   51.17    5930   53.75    5960   56.43    6020   70.81
    6050   75.49    6080   77.36    6150   76.23    6230   70.14    6250    66.9
    6310   65.03    6400   69.54    6490   72.12    6600   80.82  6835.7   85.39
#Mann= 3 ,-1,0
  3198.3     .15       0    4963    .045       0    5037     .15       0
Bank Sta=4963,5037
XS Rating Curve= 0 ,0
Exp/Cntr=0.3,0.1

Type RM Length L Ch R = 1 ,23540   ,410,410,410
BEGIN DESCRIPTION:
Indian Field Swamp 47.0
END DESCRIPTION:
XS GIS Cut Line= 3
      2155781.32       464781.17      2154024.44       464626.63
      2152527.75       464480.22
#Sta/Elev= 30
  3240.7   63.16  3420.7   61.83  3440.7   63.65  3460.7   61.08  3580.7   57.99
  3850.7   56.71  3940.7   54.62  4010.7   51.31  4140.7   49.95  4960.7   50.56
  4962.9   47.46  4964.4   44.46  5035.6   44.46  5037.1   47.46  5044.4   50.59
  5084.4   51.09  5104.4   53.98  5144.4    50.6  5624.4   50.68  5654.4   52.65
  5694.4   50.81  5794.4   58.09  5834.4   66.32  5884.4   78.75  5924.4   82.23
  5944.4   82.75  6084.4   82.57  6314.4   79.54  6394.4   79.96  6508.2   82.53
#Mann= 3 ,-1,0
  3240.7     .15       0  4962.9    .045       0  5037.1     .15       0
Bank Sta=4962.9,5037.1
XS Rating Curve= 0 ,0
Exp/Cntr=0.3,0.1

Type RM Length L Ch R = 1 ,23130   ,500,500,500
BEGIN DESCRIPTION:
Indian Field Swamp 46.0
END DESCRIPTION:
XS GIS Cut Line= 3
      2155834.21       464228.07      2153962.22       464229.75
      2152406.92       464233.13
#Sta/Elev= 30
    3128   62.74    3578   59.38    3738   55.61    3818   52.16    4058   50.01
    4798   50.01    4808   51.67    4858   49.89    4908   50.64  4962.9   47.33
  4964.4   44.33  5035.6   44.33  5037.1   47.33    5160   51.11    5230    51.9
    5250   50.79    5280   52.23    5390   51.93    5410    50.5    5470   52.61
    5500   50.48    5580   51.47    5630   50.42    5730   54.69    5770   63.06
    5810   67.64    6030   78.42    6120   80.95    6360   82.02  6555.3   85.14
#Mann= 3 ,-1,0
    3128     .15       0  4962.9    .045       0  5037.1     .15       0
Bank Sta=4962.9,5037.1
XS Rating Curve= 0 ,0
Exp/Cntr=0.3,0.1

Type RM Length L Ch R = 1 ,22630   ,500,500,500
BEGIN DESCRIPTION:
Indian Field Swamp 45.0
END DESCRIPTION:
XS GIS Cut Line= 3
      2155874.92       463593.63      2153804.46       463764.54
      2152367.22       464047.84
#Sta/Elev= 30
  2922.5   62.87  3042.5   63.57  3292.5   61.51  3362.5   58.23  3382.5   58.57
  3402.5   56.67  3452.5   54.84  3642.5   50.99  3912.5   52.21  3942.5   51.02
  3992.5    51.7  4002.5    50.7  4342.5    49.9  4922.5   50.84  4942.5   50.27
  4962.9   47.77  4964.4   44.77  5035.6   44.77  5037.1   47.77    5170    51.5
    5210   50.36    5230   52.31    5380   50.49    5520   50.85    5640   52.94
    5990      64    6010   65.31    6090   77.57    6140   81.05  6464.9   84.28
#Mann= 3 ,-1,0
  2922.5     .15       0  4962.9    .045       0  5037.1     .15       0
Bank Sta=4962.9,5037.1
XS Rating Curve= 0 ,0
Exp/Cntr=0.3,0.1

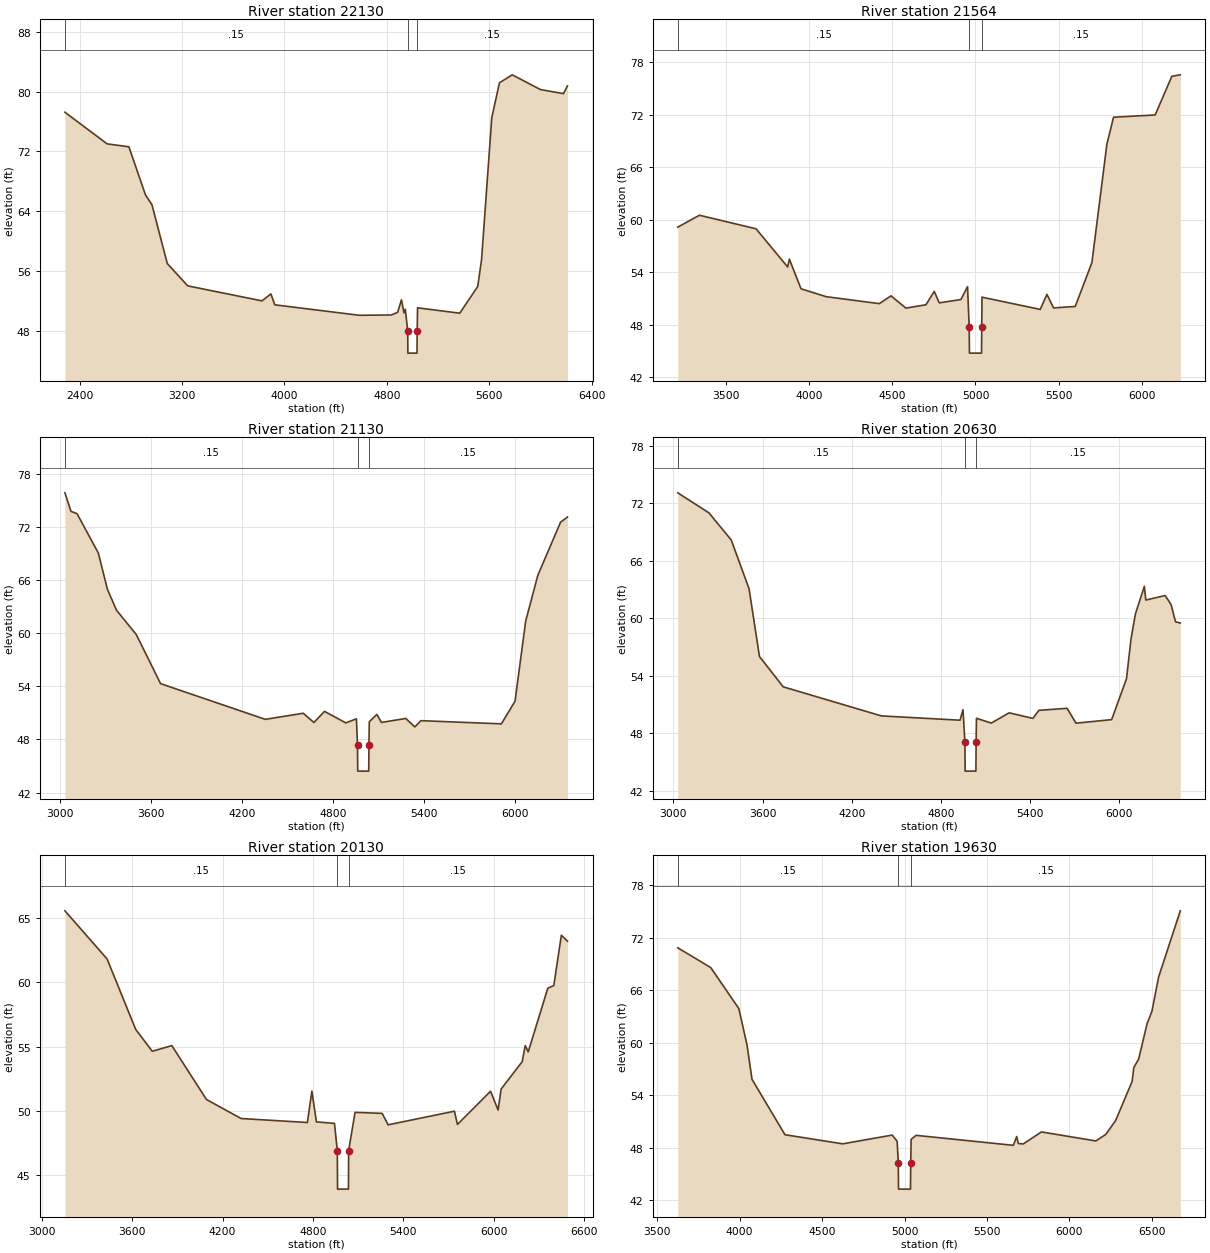
Type RM Length L Ch R = 1 ,22130   ,566,566,566
BEGIN DESCRIPTION:
Indian Field Swamp 44.0
END DESCRIPTION:
XS GIS Cut Line= 3
      2156074.19       462442.67      2153521.64       463370.36
      2152380.47       463776.52
#Sta/Elev= 30
  2284.1   77.26  2614.1   73.02  2784.1   72.63  2914.1   66.17  2964.1   64.88
  3084.1   56.99  3244.1      54  3824.1   51.99  3894.1   52.92  3924.1   51.46
  4584.1   50.06  4834.1    50.1  4884.1   50.45  4914.1   52.13  4934.1   50.38
  4944.1   50.87  4962.9   47.99  4964.4   44.99  5035.6   44.99  5037.1   47.99
    5040   51.06    5370   50.34    5510   53.91    5540   57.48    5620   76.52
    5680    81.2    5780   82.27    6000    80.3    6180   79.75  6211.3   80.78
#Mann= 3 ,-1,0
  2284.1     .15       0  4962.9    .045       0  5037.1     .15       0
Bank Sta=4962.9,5037.1
XS Rating Curve= 0 ,0
Exp/Cntr=0.3,0.1

Type RM Length L Ch R = 1 ,21564   ,434,434,434
BEGIN DESCRIPTION:
Indian Field Swamp 43.0
END DESCRIPTION:
XS GIS Cut Line= 3
      2154994.07       461958.15      2153424.99       462812.21
      2152377.11        463457.9
#Sta/Elev= 30
  3212.5   59.14  3342.5    60.5  3682.5   58.95  3872.5   54.58  3882.5   55.48
  3952.5   52.09  4102.5   51.19  4422.5   50.39  4492.5   51.28  4582.5   49.88
  4702.5   50.26  4752.5   51.79  4782.5   50.48  4912.5   50.86  4952.5   52.33
  4962.3   47.73  4963.8   44.73  5036.2   44.73  5037.7   47.73    5039   51.13
    5389   49.73    5429   51.45    5469    49.9    5599   50.07    5699   55.07
    5789   68.62    5829   71.71    6079   71.97    6179   76.39  6229.8   76.56
#Mann= 3 ,-1,0
  3212.5     .15       0  4962.3    .045       0  5037.7     .15       0
Bank Sta=4962.3,5037.7
XS Rating Curve= 0 ,0
Exp/Cntr=0.3,0.1

Type RM Length L Ch R = 1 ,21130   ,500,500,500
BEGIN DESCRIPTION:
Indian Field Swamp 42.0
END DESCRIPTION:
XS GIS Cut Line= 3
      2154934.79        461228.8      2153346.99       462386.44
      2152251.24        463166.6
#Sta/Elev= 30
    3035   75.91    3075   73.81    3115   73.55    3255    69.1    3315      65
    3375   62.62    3505   59.88    3665   54.32    4355   50.28    4605   50.97
    4675   49.92    4745   51.18    4885   49.88    4955   50.34  4962.3   47.42
  4963.8   44.42  5036.2   44.42  5037.7   47.42    5040   50.01    5090   50.84
    5120   49.93    5280   50.38    5340   49.42    5380   50.13    5910   49.77
    6000   52.33    6070   61.39    6150   66.57    6300   72.59  6345.1   73.17
#Mann= 3 ,-1,0
    3035     .15       0  4962.3    .045       0  5037.7     .15       0
Bank Sta=4962.3,5037.7
XS Rating Curve= 0 ,0
Exp/Cntr=0.3,0.1

Type RM Length L Ch R = 1 ,20630   ,500,500,500
BEGIN DESCRIPTION:
Indian Field Swamp 41.0
END DESCRIPTION:
XS GIS Cut Line= 3
      2154365.02       460675.61      2152971.31       462068.75
      2151978.77       463073.05
#Sta/Elev= 30
  3029.4   73.08  3239.4   70.99  3389.4   68.16  3509.4   63.07  3579.4   56.01
  3739.4   52.85  4399.4   49.82  4929.4   49.37  4949.4   50.47  4962.3   47.06
  4963.8   44.06  5036.2   44.06  5037.7   47.06    5040   49.57    5140   49.07
    5260   50.14    5420   49.56    5460    50.4    5650   50.61    5710   49.06
    5950   49.43    6050    53.7    6080    57.8    6110   60.45    6170   63.33
    6180    61.9    6310   62.37    6350   61.43    6380   59.63    6412    59.5
#Mann= 3 ,-1,0
  3029.4     .15       0  4962.3    .045       0  5037.7     .15       0
Bank Sta=4962.3,5037.7
XS Rating Curve= 0 ,0
Exp/Cntr=0.3,0.1

Type RM Length L Ch R = 1 ,20130   ,500,500,500
BEGIN DESCRIPTION:
Indian Field Swamp 40.0
END DESCRIPTION:
XS GIS Cut Line= 3
       2153810.9       460284.17      2152646.04       461717.01
      2151685.62       462856.69
#Sta/Elev= 30
  3153.4   65.55  3433.4   61.81  3623.4   56.33  3733.4   54.63  3863.4   55.07
  4093.4   50.88  4323.4    49.4  4763.4   49.09  4793.4   51.53  4823.4   49.14
  4943.4   49.02  4962.3   46.91  4963.8   43.91  5036.2   43.91  5037.7   46.91
    5080   49.88    5260    49.8    5300   48.91    5740   49.97    5760   48.94
    5980   51.52    6030   50.06    6050   51.69    6190   53.82    6210   55.07
    6230   54.58    6360   59.53    6400   59.74    6450   63.65  6490.4   63.19
#Mann= 3 ,-1,0
  3153.4     .15       0  4962.3    .045       0  5037.7     .15       0
Bank Sta=4962.3,5037.7
XS Rating Curve= 0 ,0
Exp/Cntr=0.3,0.1

Type RM Length L Ch R = 1 ,19630   ,500,500,500
BEGIN DESCRIPTION:
Indian Field Swamp 39.0
END DESCRIPTION:
XS GIS Cut Line= 3
      2153306.91       460117.03      2152527.78       461249.62
      2151513.56       462578.75
#Sta/Elev= 30
  3625.3   70.83  3825.3   68.57  3995.3    63.9  4045.3   59.73  4075.3   55.82
  4275.3   49.49  4625.3   48.45  4925.3   49.45  4955.3   48.75  4962.3   46.28
  4963.8   43.28  5036.2   43.28  5037.7   46.28    5040   48.96    5070   49.42
    5660   48.28    5680   49.28    5690   48.48    5720   48.44    5830   49.81
    6160   48.78    6220   49.52    6280   51.11    6380   55.58    6390   57.14
    6420   58.16    6470   62.13    6500   63.58    6540   67.46  6671.9   75.05
#Mann= 3 ,-1,0
  3625.3     .15       0  4962.3    .045       0  5037.7     .15       0
Bank Sta=4962.3,5037.7
XS Rating Curve= 0 ,0
Exp/Cntr=0.3,0.1

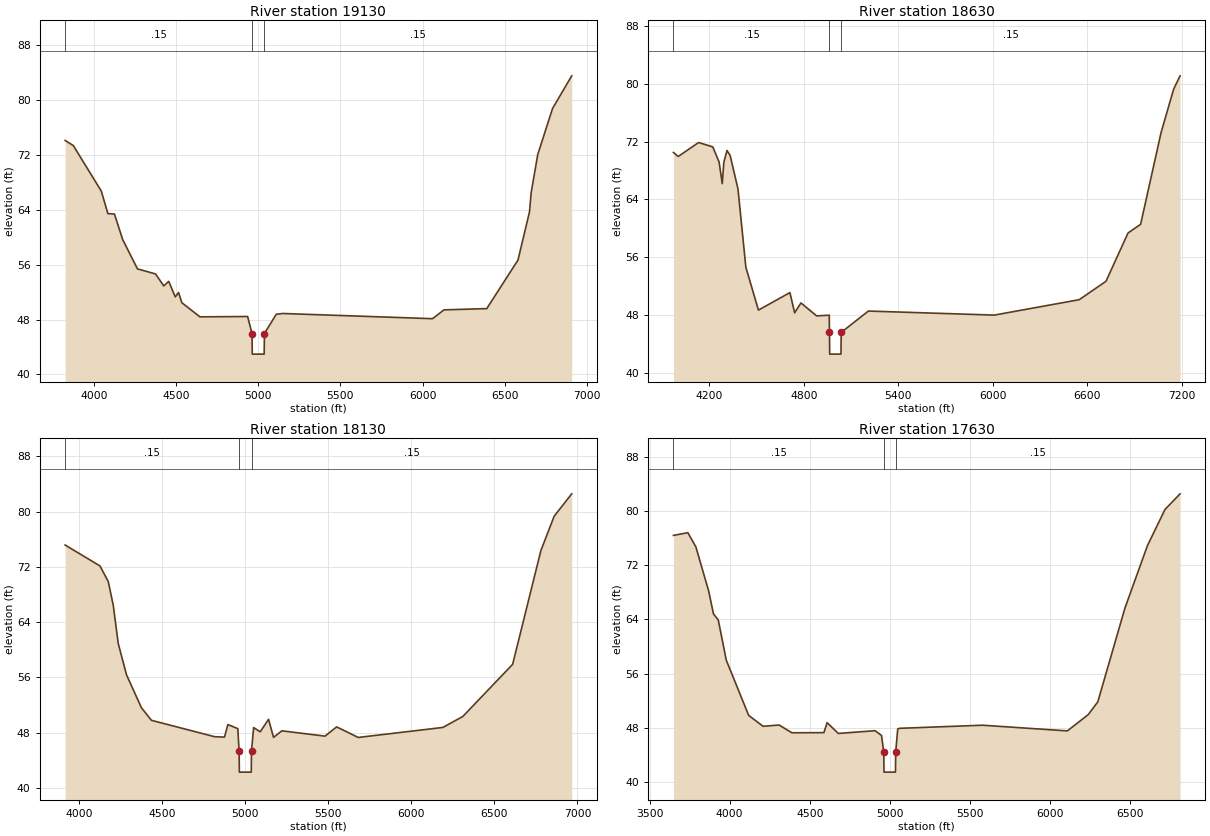
Type RM Length L Ch R = 1 ,19130   ,500,500,500
BEGIN DESCRIPTION:
Indian Field Swamp 38.0
END DESCRIPTION:
XS GIS Cut Line= 3
      2152925.02       459924.98      2152216.05       460861.24
      2151124.98       462425.03
#Sta/Elev= 30
  3825.6   74.14  3875.6   73.39  4045.6   66.75  4085.6   63.47  4125.6    63.4
  4175.6   59.68  4265.6    55.4  4375.6   54.66  4425.6   52.91  4455.6   53.58
  4495.6   51.31  4515.6   51.96  4535.6   50.46  4645.6    48.4  4935.6   48.45
  4962.3   45.96  4963.8   42.96  5036.2   42.96  5037.7   45.96    5110   48.78
    5150   48.89    6060   48.13    6130   49.42    6390    49.6    6580   56.69
    6650   63.73    6660   66.52    6700   72.07    6790    78.8  6906.8   83.57
#Mann= 3 ,-1,0
  3825.6     .15       0  4962.3    .045       0  5037.7     .15       0
Bank Sta=4962.3,5037.7
XS Rating Curve= 0 ,0
Exp/Cntr=0.3,0.1

Type RM Length L Ch R = 1 ,18630   ,500,500,500
BEGIN DESCRIPTION:
Indian Field Swamp 37.0
END DESCRIPTION:
XS GIS Cut Line= 3
      2152453.27       459706.72      2151847.76       460538.21
      2150369.29       462154.91
#Sta/Elev= 30
  3971.4   70.49  4001.4   69.94  4131.4   71.87  4221.4   71.26  4261.4   69.17
  4281.4   66.19  4291.4   69.12  4311.4   70.77  4331.4   70.09  4381.4   65.46
  4431.4   54.64  4511.4   48.72  4711.4   51.14  4741.4   48.34  4781.4   49.71
  4881.4   47.92  4961.4   48.02  4962.7   45.64  4964.2   42.64  5035.8   42.64
  5037.3   45.64    5210   48.59    6010   48.03    6550   50.16    6720    52.7
    6860   59.37    6940   60.57    7070   73.24    7150   79.25  7190.8   81.08
#Mann= 3 ,-1,0
  3971.4     .15       0  4962.7    .045       0  5037.3     .15       0
Bank Sta=4962.7,5037.3
XS Rating Curve= 0 ,0
Exp/Cntr=0.3,0.1

Type RM Length L Ch R = 1 ,18130   ,500,500,500
BEGIN DESCRIPTION:
Indian Field Swamp 36.0
END DESCRIPTION:
XS GIS Cut Line= 3
      2151996.65       459442.03      2151391.47        460342.7
        2150225.       461925.01
#Sta/Elev= 30
  3914.9   75.18  4124.9   72.15  4174.9   69.87  4204.9   66.45  4234.9   60.91
  4284.9   56.37  4374.9    51.6  4434.9    49.8  4814.9   47.43  4874.9   47.37
  4894.9   49.19  4954.9   48.59  4962.7    45.3  4964.2    42.3  5035.8    42.3
  5037.3    45.3    5050   48.75    5090   48.14    5140   49.95    5170   47.33
    5220   48.28    5480   47.51    5550   48.85    5680   47.32    6190   48.77
    6310   50.36    6610   57.91    6780   74.37    6860   79.35  6965.8   82.59
#Mann= 3 ,-1,0
  3914.9     .15       0  4962.7    .045       0  5037.3     .15       0
Bank Sta=4962.7,5037.3
XS Rating Curve= 0 ,0
Exp/Cntr=0.3,0.1

Type RM Length L Ch R = 1 ,17630   ,500,500,500
BEGIN DESCRIPTION:
Indian Field Swamp 35.0
END DESCRIPTION:
XS GIS Cut Line= 3
      2151692.23       459117.81      2150907.61       460217.86
      2149938.58       461751.58
#Sta/Elev= 30
  3648.8   76.44  3738.8   76.84  3788.8   74.74  3868.8   68.21  3898.8   64.82
  3928.8   63.93  3978.8   57.98  4118.8   49.81  4208.8    48.2  4308.8   48.39
  4388.8   47.24  4588.8   47.26  4608.8   48.74  4678.8   47.14  4908.8   47.55
  4948.8   46.84  4962.7   44.42  4964.2   41.42  5035.8   41.42  5037.3   44.42
    5050    47.8    5060    47.9    5580   48.36    6110   47.52    6240   49.92
    6300   51.81    6470   65.71    6610   74.91    6720   80.28  6814.2   82.59
#Mann= 3 ,-1,0
  3648.8     .15       0  4962.7    .045       0  5037.3     .15       0
Bank Sta=4962.7,5037.3
XS Rating Curve= 0 ,0
Exp/Cntr=0.3,0.1