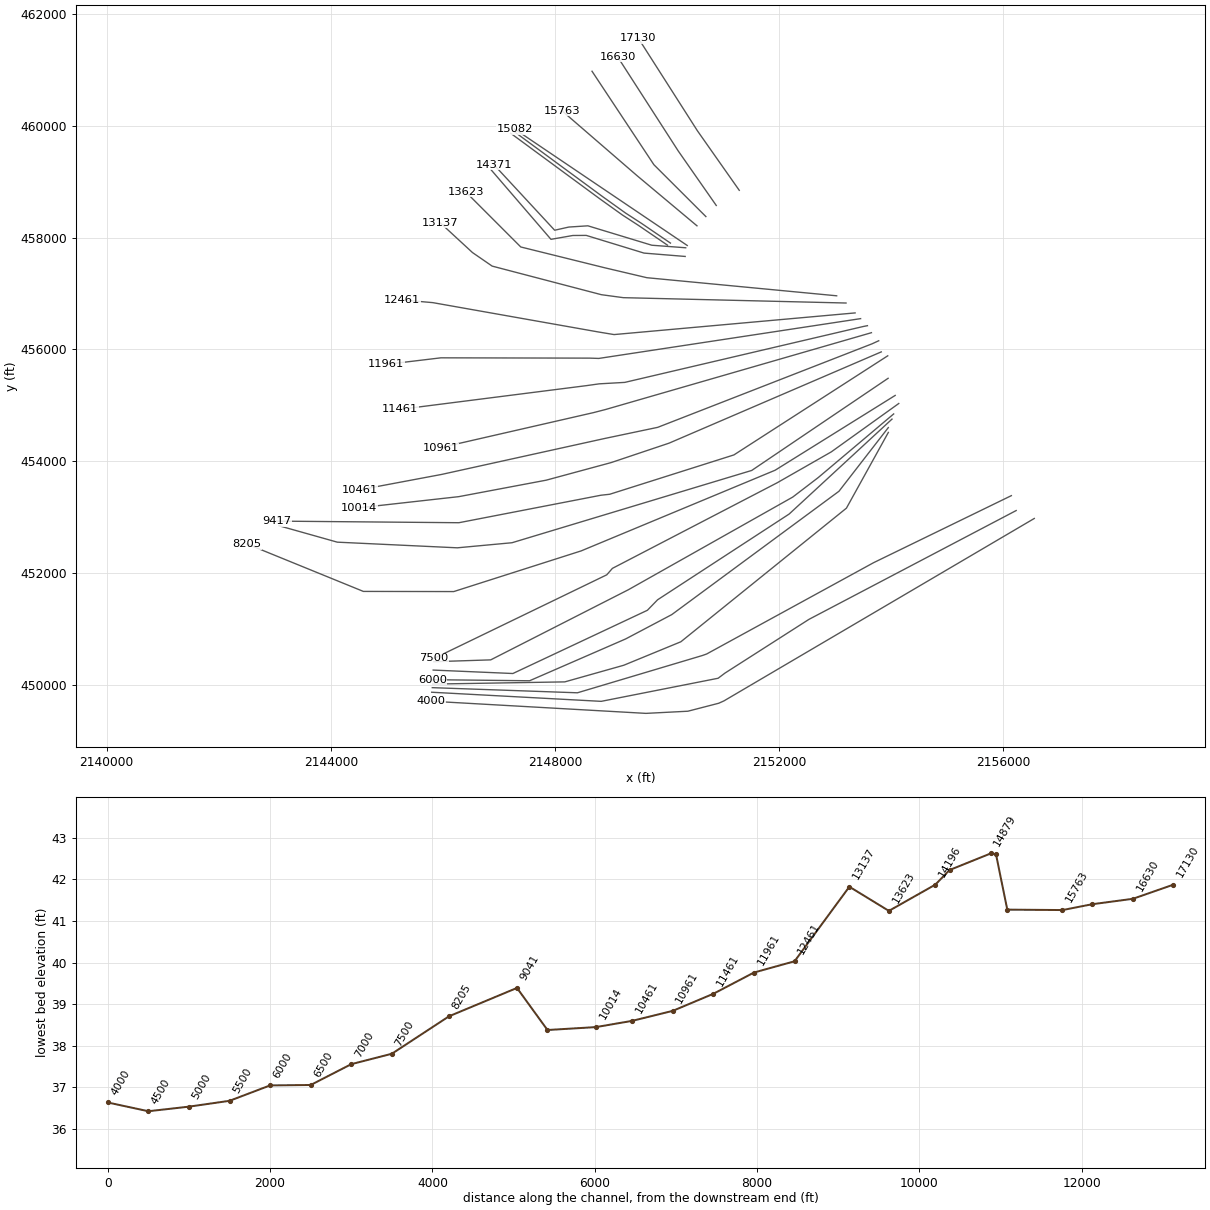
HEC-RAS study IndianFieldsSwamp.prj: S-18-19 over Indian Fields Swamp

--- IndianFieldsSwamp.g14 (geometry) --- (continued)

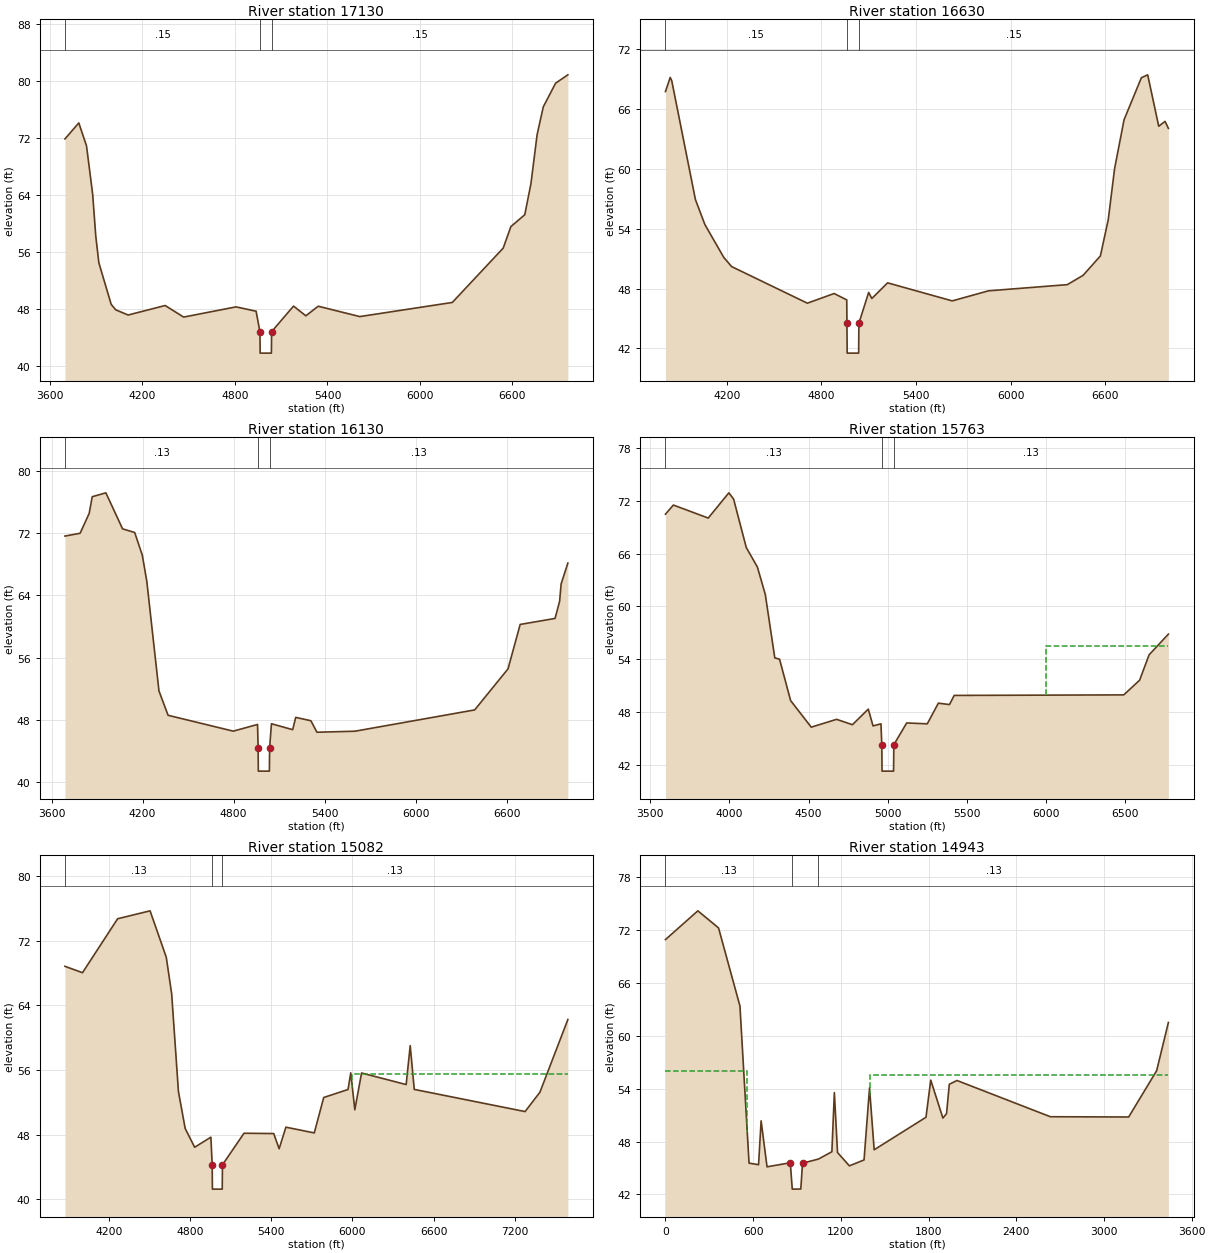
Type RM Length L Ch R = 1 ,17130   ,500,500,500
BEGIN DESCRIPTION:
Indian Field Swamp 34.0
END DESCRIPTION:
XS GIS Cut Line= 3
      2151288.56       458846.49      2150540.91       459913.29
      2149488.61       461566.26
#Sta/Elev= 30
  3697.3   71.88  3787.3   74.12  3837.3   70.91  3877.3   64.11  3897.3   58.27
  3917.3   54.53  3997.3    48.7  4027.3   47.93  4107.3   47.21  4347.3   48.54
  4467.3   46.92  4807.3   48.35  4937.3   47.74  4962.1   44.87  4963.6   41.87
  5036.4   41.87  5037.9   44.87    5180   48.46    5260    47.1    5340   48.44
    5610   46.99    6210   48.97    6540   56.58    6590    59.6    6680   61.26
    6720   65.61    6760   72.47    6800   76.37    6880   79.69  6959.5   80.86
#Mann= 3 ,-1,0
  3697.3     .15       0  4962.1    .045       0  5037.9     .15       0
Bank Sta=4962.1,5037.9
XS Rating Curve= 0 ,0
Exp/Cntr=0.3,0.1

Type RM Length L Ch R = 1 ,16630   ,500,500,500
BEGIN DESCRIPTION:
Indian Field Swamp 33.0
END DESCRIPTION:
XS GIS Cut Line= 3
      2150878.26       458575.19      2150199.24       459551.36
        2149118.       461235.44
#Sta/Elev= 30
  3810.9   67.77  3840.9   69.19  3850.9   68.85  4000.9   56.94  4060.9   54.43
  4180.9   51.13  4230.9   50.21  4710.9   46.54  4880.9   47.51  4960.9   46.87
  4962.1   44.53  4963.6   41.53  5036.4   41.53  5037.9   44.53    5100   47.62
    5120   47.01    5220   48.58    5630   46.77    5860   47.78    6360    48.4
    6460   49.33    6570   51.28    6620   54.94    6660   60.04    6720   64.94
    6830   69.16    6870   69.45    6940   64.29    6980   64.78  7001.3   64.08
#Mann= 3 ,-1,0
  3810.9     .15       0  4962.1    .045       0  5037.9     .15       0
Bank Sta=4962.1,5037.9
XS Rating Curve= 0 ,0
Exp/Cntr=0.3,0.1

Type RM Length L Ch R = 1 ,16130   ,367,367,367
BEGIN DESCRIPTION:
Indian Field Swamp 32.0
END DESCRIPTION:
XS GIS Cut Line= 3
      2150692.96       458376.67       2149765.7       459304.44
      2148661.41       460977.33
#Sta/Elev= 30
  3688.3   71.62  3788.3   71.98  3848.3   74.54  3868.3   76.68  3958.3   77.18
  4068.3   72.55  4148.3   72.08  4198.3   69.17  4228.3   65.79  4308.3   51.71
  4368.3   48.58  4798.3   46.54  4958.3    47.4  4962.1    44.4  4963.6    41.4
  5036.4    41.4  5037.9    44.4    5050   47.49    5190   46.73    5210   48.31
    5310   47.88    5350    46.4    5600   46.53    6390   49.27    6610   54.55
    6690   60.26    6920   61.03    6950   63.22    6960   65.46  7004.5   68.15
#Mann= 3 ,-1,0
  3688.3     .13       0  4962.1    .045       0  5037.9     .13       0
Bank Sta=4962.1,5037.9
XS Rating Curve= 0 ,0
Exp/Cntr=0.5,0.3

Type RM Length L Ch R = 1 ,15763   ,680,680,680
BEGIN DESCRIPTION:
Indian Field Swamp 31.0
END DESCRIPTION:
XS GIS Cut Line= 3
      2150534.17        458211.2      2149460.04       459112.86
      2148121.44       460273.48
#Sta/Elev= 30
  3596.7   70.48  3646.7   71.52  3866.7   70.04  3996.7   72.91  4026.7    72.2
  4106.7   66.69  4176.7   64.48  4226.7   61.36  4286.7   54.14  4316.7   53.99
  4386.7   49.28  4516.7   46.26  4676.7   47.15  4776.7   46.54  4876.7   48.31
  4906.7    46.4  4956.7   46.64  4962.1   44.26  4963.6   41.26  5036.4   41.26
  5037.9   44.26  5119.1   46.74  5249.1   46.64  5319.1   48.99  5389.1   48.83
  5419.1   49.87  6489.1   49.93  6589.1    51.6  6649.1   54.49  6770.8   56.84
#Mann= 3 ,-1,0
  3596.7     .13       0  4962.1    .045       0  5037.9     .13       0
#XS Ineff= 2 , 0
                            6000            55.5
Permanent Ineff=
       F       F
Bank Sta=4962.1,5037.9
XS Rating Curve= 0 ,0
Exp/Cntr=0.5,0.3

Type RM Length L Ch R = 1 ,15082   ,139.3,139.3,139.3
BEGIN DESCRIPTION:
Indian Field Swamp 30.0
END DESCRIPTION:
XS GIS Cut Line= 3
      2150360.93       457859.09      2149428.78       458489.37
      2147278.39       459944.87
#Sta/Elev= 30
  3872.3   68.82  4002.3   68.03  4262.3    74.7  4502.3   75.68  4622.3   69.94
  4662.3    65.4  4712.3   53.33  4762.3   48.76  4832.3   46.45  4952.3   47.69
  4962.1   44.27  4963.6   41.27  5036.4   41.27  5037.9   44.27  5197.5   48.18
  5417.5   48.14  5457.5   46.26  5507.5   48.93  5717.5   48.22  5787.5    52.6
  5967.5   53.59  5987.5   55.65  6017.5   51.08  6067.5   55.63  6397.5    54.2
  6427.5   59.01  6457.5    53.6  7277.5   50.86  7387.5   53.25  7594.2   62.24
#Mann= 3 ,-1,0
  3872.3     .13       0  4962.1    .045       0  5037.9     .13       0
#XS Ineff= 2 , 0
                            6000            55.5
Permanent Ineff=
       F       F
Bank Sta=4962.1,5037.9
XS Rating Curve= 0 ,0
Exp/Cntr=0.5,0.3

Type RM Length L Ch R = 1 ,14943   ,63.9,63.9,63.9
XS GIS Cut Line= 6
2150060.73179075457902.3452848622149544.11541243458255.135346235
2149361.73382409458373.7998231982149258.87973167458440.417532982
2148855.42888635458729.9528455062147263.22773477459904.409083364
#Sta/Elev= 30
       0    70.9   221.7   74.16   363.2   72.22   509.6   63.36  571.83   45.55
   636.9   45.37   654.4   50.34   694.9   45.13     854   45.59  867.56    42.6
  925.91   42.61  937.66   45.54  1046.8   46.01  1138.5   46.84 1155.49   53.55
 1177.18   46.75  1258.3   45.24 1358.59   45.91 1396.06   54.08  1427.9   47.06
  1782.3   50.75    1815   54.96  1898.1   50.66    1923   51.16  1941.8   54.49
  1994.4   54.92  2633.3   50.81  3169.1   50.78  3360.4   56.03  3440.8    61.5
#Mann= 3 ,-1,0
       0     .13       0  867.56    .045       0  1046.8     .13       0
#XS Ineff= 2 , 0
             560      56    1400            55.5
Permanent Ineff=
       F       F
Bank Sta=854,937.66
XS Rating Curve= 0 ,0
Exp/Cntr(USF)=0,0
Exp/Cntr=0.5,0.3

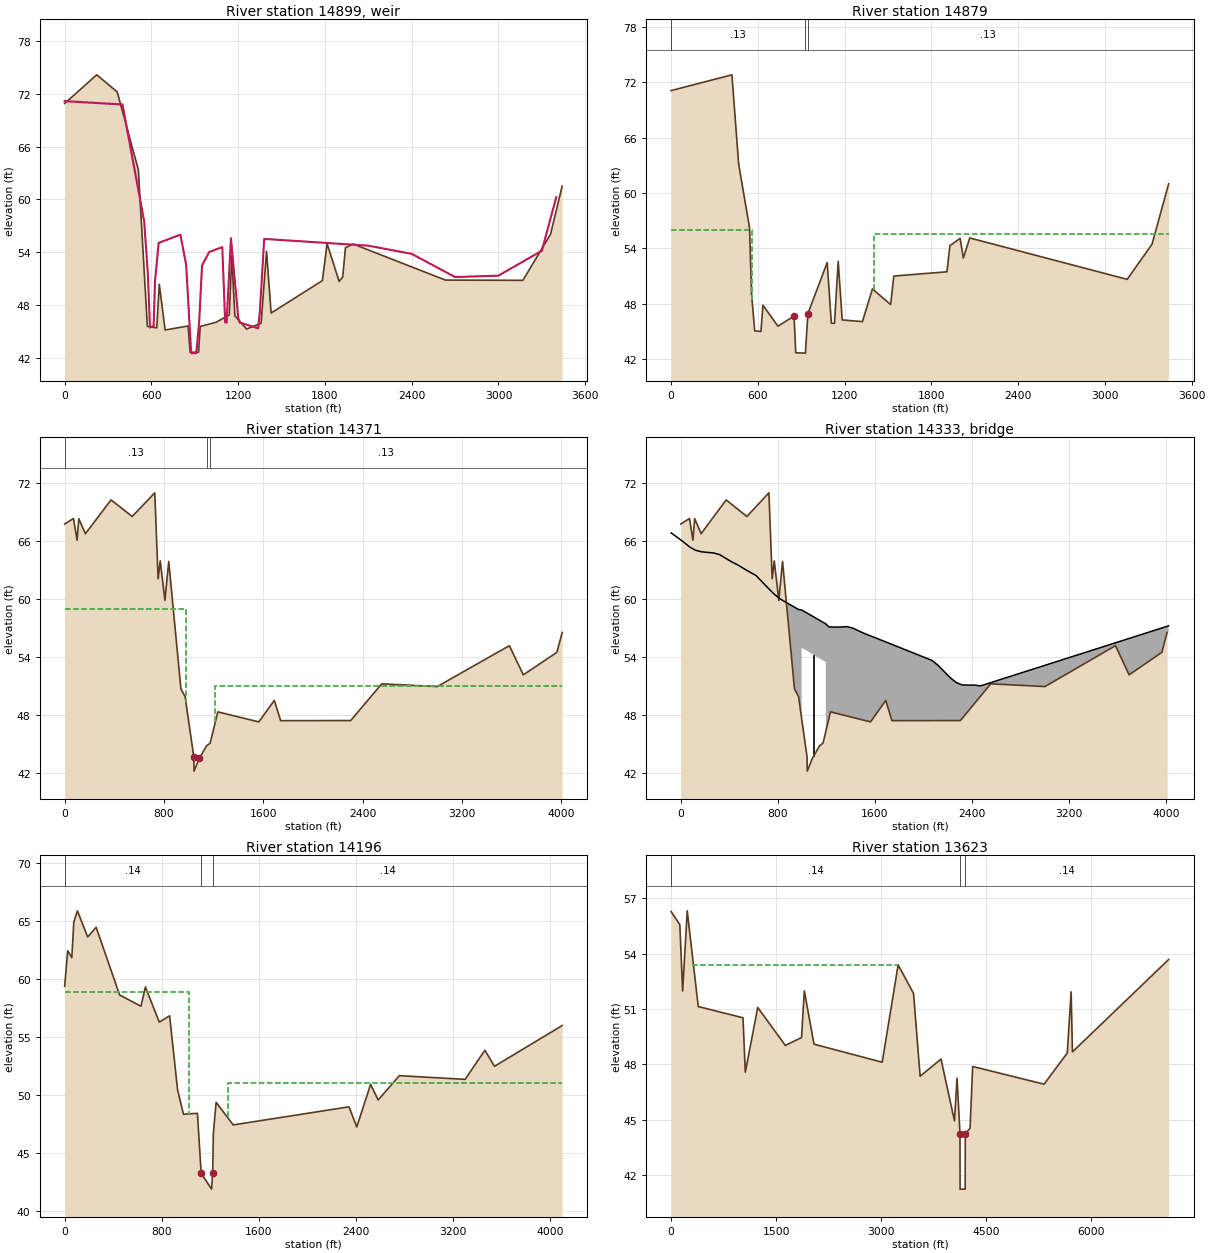
Type RM Length L Ch R = 5 ,14899   ,,,
BEGIN DESCRIPTION:
Floodplain Fill U/S of S-18-19
END DESCRIPTION:
IW Pilot Flow=0
#Inline Weir SE= 30
       0  71.164     400  70.785     550  57.459     575  51.576     590   45.42
     615  45.559     625  50.712     650  55.035     800  55.983     840  52.584
     875    42.5     910    42.5     930      46     950  52.465    1000  54.013
    1090  54.557    1110      46    1120      46    1150  55.566    1200  46.542
    1210  45.983    1338  45.328    1350  47.223    1380  55.492    2100  54.726
    2400  53.795    2700  51.156    3000  51.315    3300  54.144    3400   60.24
IW Dist,WD,Coef,Skew,MaxSub,Min_El,Is_Ogee,SpillHt,DesHd
35,8,2.6,0,0.98,, 0 ,,,2,2,
Inline Weir Flap Gates= 0
IW Outlet Rating Curve= 0 ,False,,

Type RM Length L Ch R = 1 ,14879   ,508.8,508.8,508.8
XS GIS Cut Line= 6
 2150007.2416423457865.5172508032149490.62526397458218.307312176
2149308.24367563458336.9717891392149205.38958322458403.589498923
2148801.93873789458693.1248114472147209.73758631459867.581049305
#Sta/Elev= 30
       0   71.09   420.4    72.8   466.9   63.14   542.3   56.21  556.06   49.06
   578.1   45.03  621.13   44.97  634.93   47.82   738.4   45.54   850.1   46.64
  861.69   42.66  928.73   42.62  945.89    46.9  1079.3   52.44    1108   45.85
 1129.86   45.86 1155.49   52.57  1183.1   46.22  1323.1   46.04  1392.3   49.58
  1517.9   47.89  1540.3   50.98  1907.5   51.44  1927.9   54.27  1998.8   55.07
  2020.9   52.94  2065.2   55.11  3154.2   50.62  3326.1   54.44  3440.8   60.98
#Mann= 3 ,-1,0
       0     .13       0  928.73    .045       0  945.89     .13       0
#XS Ineff= 2 , 0
             560      56    1400            55.5
Permanent Ineff=
       F       F
Bank Sta=850.1,945.89
XS Rating Curve= 0 ,0
Exp/Cntr(USF)=0,0
Exp/Cntr=0.5,0.3

Type RM Length L Ch R = 1 ,14371   ,174.7,174.7,174.7
BEGIN DESCRIPTION:
Wire Road at Indian Field - US
END DESCRIPTION:
XS GIS Cut Line= 6
2150333.42248984  457818.40776572149728.21248984  457863.8777657
2148587.55000415458211.3003852132148247.66440599  458189.1377657
 2147994.4660008458132.4137917952146909.49685185459306.712552653
#Sta/Elev= 30
       0   67.73    71.3    68.3    99.9   66.06     114   68.28   167.1   66.73
   373.6   70.22   544.1   68.51   725.8   70.95   752.8   62.08   769.9   63.93
   807.5   59.85   838.2   63.87   936.4    50.7   970.1   49.91    1040  43.698
  1041.9   42.22    1085  43.563 1143.66   44.84 1171.83   45.11  1233.5   48.34
  1563.5    47.3  1688.6   49.52  1739.8   47.43  2303.6   47.44  2553.8   51.23
  3000.9   50.95  3581.9   55.17  3694.1   52.16  3964.3   54.48  4007.2   56.53
#Mann= 3 ,-1,0
       0     .13       0 1143.66    .045       0 1171.83     .13       0
#XS Ineff= 2 , 0
       0     976   58.91    1214       0   51.02
Permanent Ineff=
       F       F
Bank Sta=1040,1085
XS Rating Curve= 0 ,0
Exp/Cntr=0.5,0.3

Type RM Length L Ch R = 3 ,14333   ,,,
BEGIN DESCRIPTION:
S-18-19 (Wire Rd) over Indian Fields  Swamp
END DESCRIPTION:
Bridge Culvert--1,0,-1,-1, 0
Deck Dist Width WeirC Skew NumUp NumDn MinLoCord MaxHiCord MaxSubmerge Is_Ogee
19,36,3,0, 83, 83, , , 0.95, 0, 2,2,,
     -80     -30      20      70     120     170     220     270     320     370
     420     470     520     570     620     670     720     770     820     870
     920     970  994.99     995    1195 1195.01    1220    1270    1320    1370
    1420    1470    1520    1570    1620    1670    1720    1770    1820    1870
    1920    1970    2020    2070    2120    2170    2220    2270    2320    2370
    2420    2470    2520    2570    2620    2670    2720    2770    2820    2870
    2920    2970    3020    3070    3120    3170    3220    3270    3320    3370
    3420    3470    3520    3570    3620    3670    3720    3770    3820    3870
    3920    3970    4020
   66.81   66.36    65.9  65.383  65.023   64.86    64.8   64.74   64.57   64.19
   63.82    63.5   63.12   62.76   62.41   61.75   61.11   60.48  59.984  59.624
  59.265  58.905  58.861  58.861  57.419  57.422  57.105   57.09    57.1   57.14
   56.97   56.67   56.39   56.15  55.903   55.65  55.403   55.15    54.9   54.65
  54.403   54.15  53.903   53.65  53.139  52.503  51.866  51.361  51.111  51.105
    51.1   51.02   51.22   51.42   51.62   51.82   52.02   52.22   52.42   52.62
   52.82   53.02   53.22   53.42   53.62   53.82   54.02   54.22   54.42   54.62
   54.82   55.02   55.22   55.42   55.62   55.82   56.02   56.22   56.42   56.62
   56.82   57.02   57.22
                                                                                
                                                                                
                           54.96   53.48
                                                                                
                                                                                
                                                                                
                                                                                
                                                                                
                        
       8      58     108     158     208     258     308     358     408     458
     508     558     608     658     708     758     808     858     908     958
    1008    1058 1082.99    1083    1283 1283.01    1308    1358    1408    1458
    1508    1558    1608    1658    1708    1758    1808    1858    1908    1958
    2008    2058    2108    2158    2208    2258    2308    2358    2408    2458
    2508    2558    2608    2658    2708    2758    2808    2858    2908    2958
    3008    3058    3108    3158    3208    3258    3308    3358    3408    3458
    3508    3558    3608    3658    3708    3758    3808    3858    3908    3958
    4008    4058    4108
   66.81   66.36    65.9  65.383  65.023   64.86    64.8   64.74   64.57   64.19
   63.82    63.5   63.12   62.76   62.41   61.75   61.11   60.48  59.984  59.624
  59.265  58.905  58.861  58.861  57.419  57.422  57.105   57.09    57.1   57.14
   56.97   56.67   56.39   56.15  55.903   55.65  55.403   55.15    54.9   54.65
  54.403   54.15  53.903   53.65  53.139  52.503  51.866  51.361  51.111  51.105
    51.1   51.02   51.22   51.42   51.62   51.82   52.02   52.22   52.42   52.62
   52.82   53.02   53.22   53.42   53.62   53.82   54.02   54.22   54.42   54.62
   54.82   55.02   55.22   55.42   55.62   55.82   56.02   56.22   56.42   56.62
   56.82   57.02   57.22
                                                                                
                                                                                
                           54.96   53.48
                                                                                
                                                                                
                                                                                
                                                                                
                                                                                
                        
Pier Skew, UpSta & Num, DnSta & Num=  ,1095, 2 ,1183, 2 , 0 , 0 , 0 ,,
       4       4
   41.87   55.11
       4       4
   41.87   55.11
Abutment Skew #Up #Dn= , 3 , 3
  994.99  996.99 1009.37
   53.11   53.11   46.92
 1082.01 1084.01 1093.41
   53.11   53.11   48.41
Abutment Skew #Up #Dn= , 3 , 3
 1180.13 1193.01 1195.01
   45.23   51.67   51.67
 1274.71 1281.01 1283.01
   48.52   51.67   51.67
BR Coef=-1 , 0 , 0 ,, 0 ,,,0.8,0,,0,
WSPro=,,,, 1 ,,,, 0 ,,,, 0 ,,,,-1 ,-1 ,-1 , 0 , 0 , 0 , 0 , 0
BC Design=,, 0 ,, 0 ,,,,,,
BC Use User HTab Curves=0
BC User HTab FreeFlow(D)= 0

Type RM Length L Ch R = 1 ,14196   ,572.1,572.1,572.1
BEGIN DESCRIPTION:
Wire Road at Indian Field - DS
END DESCRIPTION:
XS GIS Cut Line= 6
2150323.70635095457663.0944824492149589.22826132457723.219142731
2148557.91016933458039.7280789072148319.53207461458038.226249793
2147928.73818492457969.4063180592146859.36653229459215.052239341
#Sta/Elev= 30
       0   59.37      25   62.44      59   61.84    75.3   64.92   104.9   65.88
     190   63.62   259.3   64.46   453.1   58.62   628.7   57.65   665.4   59.31
   779.9   56.28     865   56.82   930.8   50.42   979.3   48.33  1094.2   48.41
    1125  43.235    1211   41.87 1219.69   43.27  1225.5   46.66  1248.1   49.36
  1389.4   47.41  2343.6   48.97  2407.3   47.23  2521.4   50.91  2583.8   49.56
  2758.3   51.66  3300.5   51.34  3463.4   53.85  3542.6   52.47  4100.4   55.98
#Mann= 3 ,-1,0
       0     .14       0    1125    .045       0 1219.69     .14       0
#XS Ineff= 2 , 0
       0 1023.15   58.91 1342.85       0   51.02
Permanent Ineff=
       F       F
Bank Sta=1125,1219.69
XS Rating Curve= 0 ,0
Exp/Cntr=0.5,0.3

Type RM Length L Ch R = 1 ,13623   ,486.9,486.9,486.9
BEGIN DESCRIPTION:
Indian Field Swamp 27.0
END DESCRIPTION:
XS GIS Cut Line= 6
2153026.94091169456958.8776026612149640.35532849457282.732547319
      2148897.04       457458.24      2147390.32       457832.55
2146490.42060964458735.3635665482146405.30738219458821.212308733
#Sta/Elev= 30
       0   56.29   124.5   55.58   164.6   51.98   230.2   56.33     388   51.14
  1027.5   50.53  1060.5   47.58  1238.5   51.09  1633.5   49.03  1864.8   49.46
  1904.4   51.99  2042.8    49.1  3018.5   48.12    3246    53.4  3466.2   51.85
  3560.2   47.36    3859   48.29  4051.7   44.94  4088.1   47.26  4130.3   44.24
  4131.8   41.24  4204.6   41.24  4206.1   44.24  4274.5   44.54  4311.7   47.89
  5332.9   46.93  5664.3   48.62  5719.7   51.94  5738.2   48.68  7113.9   53.69
#Mann= 3 ,-1,0
       0     .14       0  4130.3    .045       0  4206.1     .14       0
#XS Ineff= 1 ,-1
  292.96 3245.07   53.41
Permanent Ineff=
       F
Bank Sta=4130.3,4206.1
XS Rating Curve= 0 ,0
Exp/Cntr=0.3,0.1

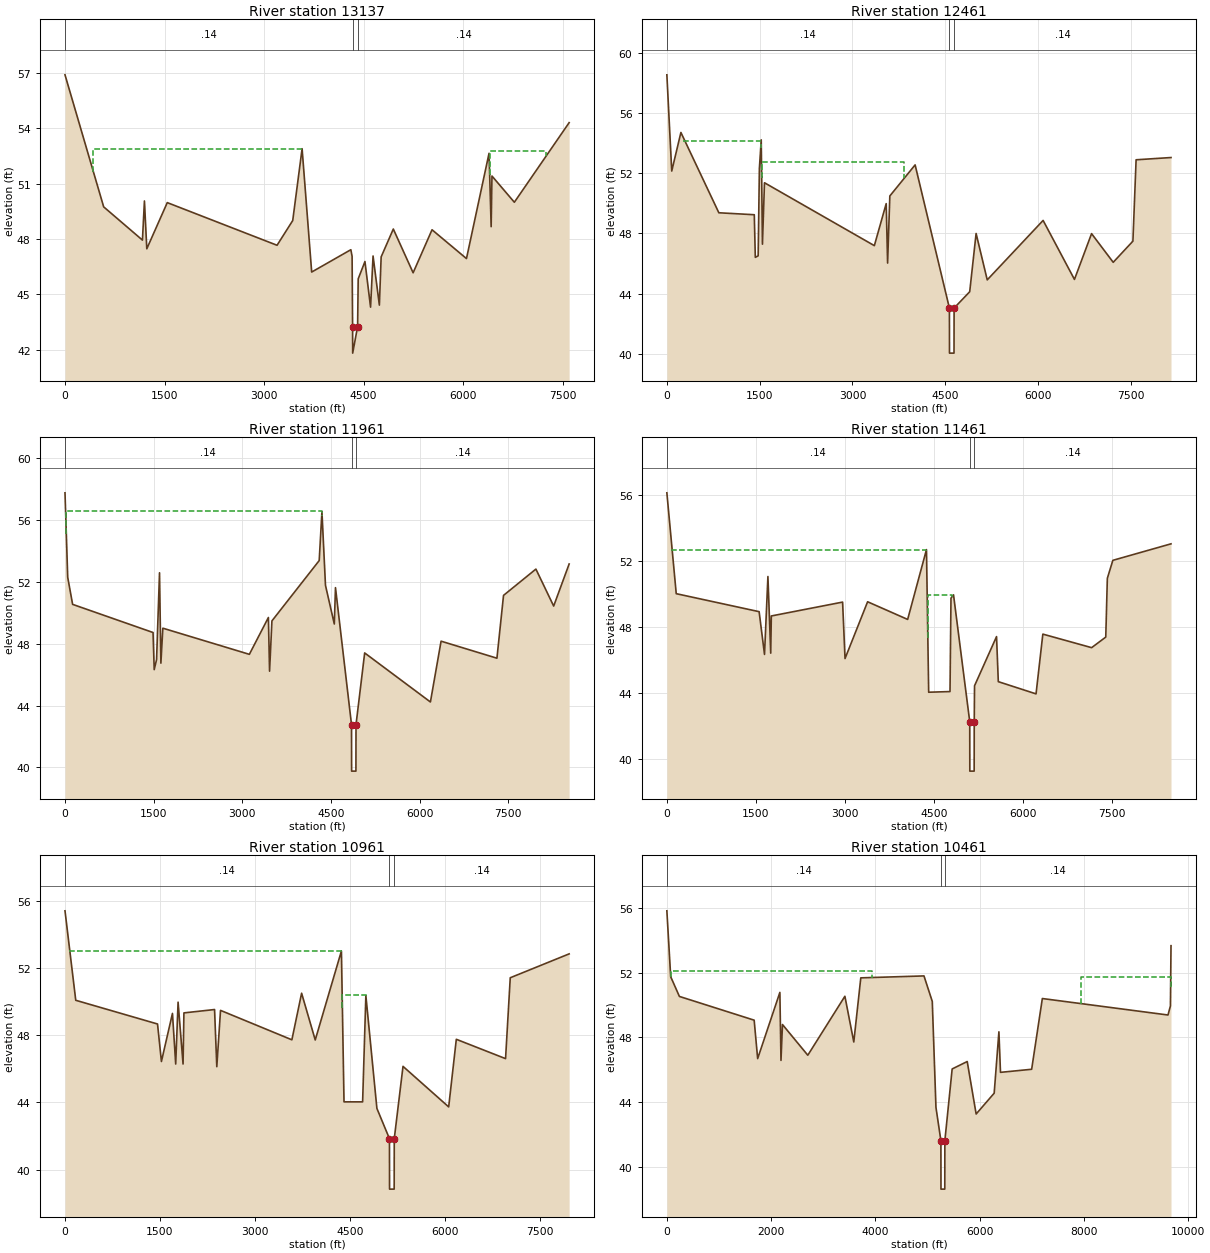
Type RM Length L Ch R = 1 ,13137   ,675.3,675.3,675.3
BEGIN DESCRIPTION:
Indian Field Swamp 26.0
END DESCRIPTION:
XS GIS Cut Line= 6
2153193.98305362456829.7243368632149219.85134404456925.526007935
      2148828.96       456978.58      2146879.49       457490.28
2146528.26540239457732.7604837892145951.50791298458266.435678448
#Sta/Elev= 30
       0   56.89   582.9   49.74  1167.2   47.94  1197.1   50.06  1232.9   47.47
  1541.4   49.97  3195.8   47.66  3432.2      49  3573.3   52.89  3717.7   46.21
    4308   47.42  4326.9   47.06  4334.2   43.26  4335.7   41.82    4410   43.26
  4418.7   45.84  4520.5   46.78  4605.3   44.31  4642.7   47.08  4737.9   44.42
  4764.7   47.03    4948   48.54  5246.6   46.17  5531.6    48.5  6050.6   46.94
  6390.7   52.64  6422.6   48.67  6434.8   51.41  6772.1   49.99  7597.9    54.3
#Mann= 3 ,-1,0
       0     .14       0  4334.2    .045       0    4410     .14       0
#XS Ineff= 2 ,-1
  428.17 3574.08   52.86    6400 7251.83   52.75
Permanent Ineff=
       F       F
Bank Sta=4334.2,4410
XS Rating Curve= 0 ,0
Exp/Cntr=0.3,0.1

Type RM Length L Ch R = 1 ,12461   ,500,500,500
BEGIN DESCRIPTION:
Indian Field Swamp 25.0
END DESCRIPTION:
XS GIS Cut Line= 5
2153355.76653627456652.5683167752149054.62479691456265.017761422
      2148772.28       456312.12      2145819.84        456836.6
      2145276.23       456884.77
#Sta/Elev= 30
       0   58.57    78.7   52.16     227   54.73   840.3   49.38  1413.1   49.25
  1429.6   46.41  1475.7   46.51  1495.5   52.33  1525.2   54.24  1544.9   47.29
  1577.9   51.38  3353.8   47.19  3545.4   49.99    3568   46.03  3604.2    50.5
  4012.8   52.57    4567   43.03  4568.5   40.03  4641.5   40.03    4643   43.03
  4895.3   44.12  4998.6      48  5178.6   44.91  6081.8   48.87  6588.4   44.94
    6865   47.99    7215   46.08  7533.4   47.49  7584.9   52.91  8149.2   53.06
#Mann= 3 ,-1,0
       0     .14       0    4567    .045       0    4643     .14       0
#XS Ineff= 2 ,-1
  253.52 1526.76   54.16 1532.39 3836.62   52.79
Permanent Ineff=
       F       F
Bank Sta=4567,4643
XS Rating Curve= 0 ,0
Exp/Cntr=0.3,0.1

Type RM Length L Ch R = 1 ,11961   ,500,500,500
BEGIN DESCRIPTION:
Indian Field Swamp 24.0
END DESCRIPTION:
XS GIS Cut Line= 5
2153454.00214837 456550.407318942148782.00816594455838.109285711
      2148621.93       455843.532145964.16472259455848.908397644
2144984.25500473455731.088779589
#Sta/Elev= 30
       0   57.75    45.9   52.29   129.1   50.54  1489.9   48.72  1509.8   46.32
  1549.6   46.97  1599.4   52.58  1622.6   46.74  1655.8      49  3119.7   47.31
  3441.7   49.69  3461.6   46.22  3501.5   49.47  4301.5   53.37  4347.9   56.53
  4407.7   51.77  4557.1   49.27    4577   51.62  4848.4   42.76  4849.9   39.76
  4922.9   39.76  4924.4   42.76    5071    47.4  6183.4   44.23  6363.9   48.16
    7309   47.06  7420.6   51.12  7968.4   52.82  8269.1   50.43  8530.9   53.15
#Mann= 3 ,-1,0
       0     .14       0  4848.4    .045       0  4924.4     .14       0
#XS Ineff= 1 ,-1
   22.54 4343.6656.54378
Permanent Ineff=
       F
Bank Sta=4848.4,4924.4
XS Rating Curve= 0 ,0
Exp/Cntr=0.3,0.1

Type RM Length L Ch R = 1 ,11461   ,500,500,500
BEGIN DESCRIPTION:
Indian Field Swamp 23.0
END DESCRIPTION:
XS GIS Cut Line= 6
2153575.86235239456424.2245724832153497.24787566456408.621997945
2149245.38052075455409.3169573782148790.26196032455383.495812448
       2148558.5       455350.842145234.18343578454926.580070615
#Sta/Elev= 30
       0   56.11   157.7      50  1553.5   48.91  1644.3   46.32  1701.6   51.04
  1748.8    46.4  1758.9   48.65  2959.1   49.49  3000.1   46.07  3380.3   49.51
  4054.5   48.44  4371.4   52.67  4408.5   44.03  4767.7   44.07  4784.2   49.73
  4826.9   49.93  5099.8   42.25  5101.3   39.25  5174.3   39.25  5175.8   42.25
  5180.8   44.42  5551.2    47.4    5581   44.67  6216.4   43.93  6330.9   47.55
  7152.2   46.73  7390.4   47.37    7417   50.93  7509.5   52.02  8489.1   53.02
#Mann= 3 ,-1,0
       0     .14       0  5099.8    .045       0  5175.8     .14       0
#XS Ineff= 2 ,-1
   67.61  4366.2   52.67 4394.37    4800    49.9
Permanent Ineff=
       F       F
Bank Sta=5099.8,5175.8
XS Rating Curve= 0 ,0
Exp/Cntr=0.3,0.1

Type RM Length L Ch R = 1 ,10961   ,500,500,500
BEGIN DESCRIPTION:
Indian Field Swamp 22.0
END DESCRIPTION:
XS GIS Cut Line= 5
2153647.26973931456298.7466817292148906.49626126454925.196586679
      2148687.49        454868.42146127.84336886454280.440940538
2145961.70293878454230.971129256
#Sta/Elev= 30
       0   55.39   169.9   50.07  1461.3   48.66  1522.8   46.43  1697.1   49.29
  1748.3   46.28  1785.9   49.96  1864.5   46.28  1878.1   49.32  2361.9   49.52
  2397.3   46.12  2456.2   49.47    3583   47.72  3736.7   50.49  3951.9   47.71
  4365.3      53  4406.3   44.03  4700.2   44.03  4751.4   50.35  4925.7   43.64
    5124   41.84  5125.5   38.84  5198.5   38.84    5200   41.84  5338.1   46.14
  6059.3   43.73  6179.8   47.75  6957.6    46.6  7031.7   51.41  7961.7   52.83
#Mann= 3 ,-1,0
       0     .14       0    5124     .05       0    5200     .14       0
#XS Ineff= 2 ,-1
   58.59 4362.82   53.01 4380.85 4754.93    50.4
Permanent Ineff=
       F       F
Bank Sta=5124,5200
XS Rating Curve= 0 ,0
Exp/Cntr=0.3,0.1

Type RM Length L Ch R = 1 ,10461   ,447,447,447
BEGIN DESCRIPTION:
Indian Field Swamp 21.0
END DESCRIPTION:
XS GIS Cut Line= 6
2153777.13749733 456154.587791242153657.57829643456099.430525263
2149833.56232464454605.0034819372148881.54431168454404.353945574
2145976.86490591453762.1764121592144517.65246701453487.342626834
#Sta/Elev= 30
       0   55.83    73.4   51.75   240.4   50.53  1674.4   49.06  1741.5   46.68
  2167.6   50.78  2188.8   46.57  2217.6   48.79  2703.2   46.89  3414.8   50.54
  3585.5   47.71  3719.8   51.68  4931.6    51.8    5091   50.22  5161.4   43.66
  5256.2    41.6  5257.7    38.6  5330.7    38.6  5332.2    41.6  5472.2   46.04
  5761.1    46.5  5932.3   43.25  6278.3   44.54    6369   48.34  6399.2   45.83
  6997.1   46.02    7202    50.4  9612.1   49.38  9658.8   49.94  9670.1   53.67
#Mann= 3 ,-1,0
       0     .14       0  5256.2     .05       0  5332.2     .14       0
#XS Ineff= 2 ,-1
   73.24 3938.03   52.12 7943.66 9661.97   51.75
Permanent Ineff=
       F       F
Bank Sta=5256.2,5332.2
XS Rating Curve= 0 ,0
Exp/Cntr=0.3,0.1

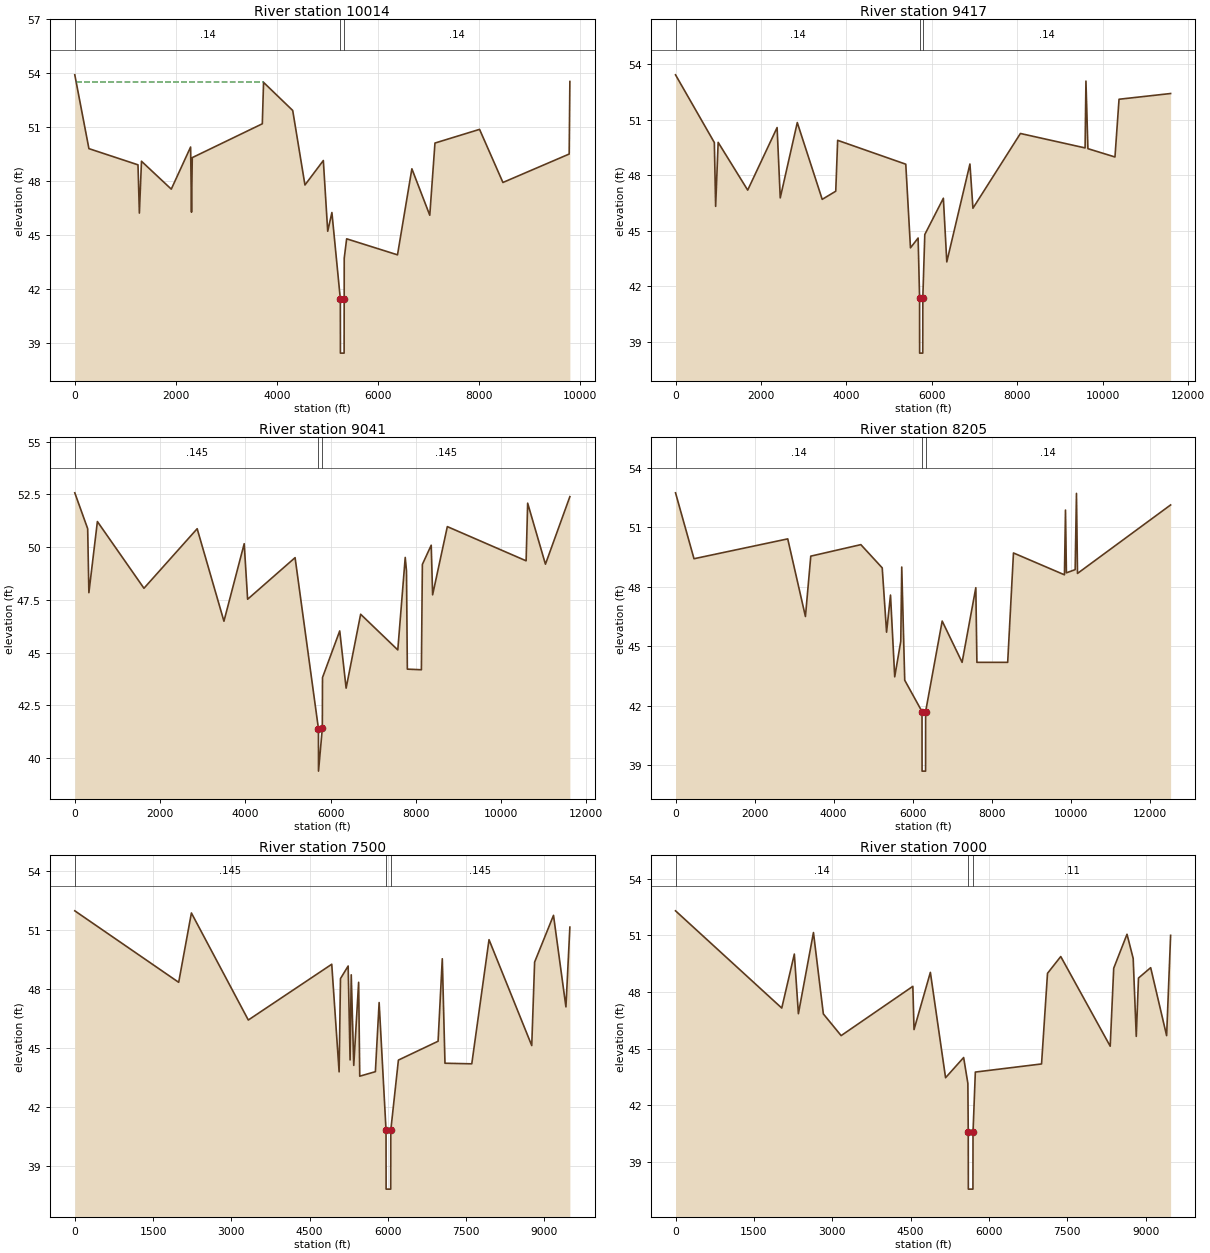
Type RM Length L Ch R = 1 ,10014   ,597,597,597
BEGIN DESCRIPTION:
Indian Field Swamp 20.0
END DESCRIPTION:
XS GIS Cut Line= 6
2153822.74700523455955.3394419582150036.31714903454322.172402214
2149002.03882653453974.1065252442147843.39257349453659.448709178
2146284.17914738453364.8152268952144501.88520685453165.008168157
#Sta/Elev= 30
       0   53.91   279.5   49.81  1250.5   48.91    1278   46.23  1319.4   49.11
  1909.1   47.56  2291.5    49.9  2309.4   46.28  2324.2   49.31  3710.3   51.19
  3734.9   53.49  4311.8   51.93  4554.1   47.79  4917.7   49.15  5004.3   45.22
  5087.3   46.26  5254.3   41.45  5255.8   38.45  5328.8   38.45  5330.3   41.45
    5331   43.72  5379.1    44.8  6385.3   43.91  6669.7   48.69  7023.7   46.11
  7126.5   50.12  8008.8   50.88  8471.1   47.93    9782   49.51  9795.9   53.54
#Mann= 3 ,-1,0
       0     .14       0  5254.3     .05       0  5330.3     .14       0
#XS Ineff= 1 ,-1
   22.54 3735.21   53.49
Permanent Ineff=
       F
Bank Sta=5254.3,5330.3
XS Rating Curve= 0 ,0
Exp/Cntr=0.3,0.1

Type RM Length L Ch R = 1 ,9417    ,375.8,375.8,375.8
BEGIN DESCRIPTION:
Indian Field Swamp 18.0
END DESCRIPTION:
XS GIS Cut Line= 6
2153938.09291933455885.0788300322151193.01645256454111.450668085
2148976.89385052453407.433819369       2148820.4       453390.12
       2146285.9       452898.232143031.98348843452926.832117093
#Sta/Elev= 30
       0   53.42   908.5   49.76   938.7   46.31   997.6   49.77  1689.1   47.19
  2377.2   50.57    2451   46.77  2849.5   50.84  3432.9   46.69  3749.7   47.13
  3794.4   49.88  5388.6   48.59  5498.6   44.07  5677.7    44.6  5711.6   41.38
  5713.1   38.38  5786.1   38.38  5787.6   41.38  5833.9   44.79  6268.4   46.75
  6348.6   43.31  6890.2    48.6  6960.4   46.21  8071.7   50.25  9585.2   49.47
  9605.2   53.08  9651.2   49.43 10284.6   48.98 10379.8    52.1 11586.8   52.41
#Mann= 3 ,-1,0
       0     .14       0  5711.6     .05       0  5787.6     .14       0
Bank Sta=5711.6,5787.6
XS Rating Curve= 0 ,0
Exp/Cntr=0.3,0.1

Type RM Length L Ch R = 1 ,9041    ,836.7,836.7,836.7
BEGIN DESCRIPTION:
Indian Field Swamp 17.0
END DESCRIPTION:
XS GIS Cut Line= 6
2153944.79961031455482.6505247032151511.13574511453833.723967058
      2147233.49       452539.972146257.60577354452449.151477224
2144116.09504544452550.2326525022143076.91274964452843.658707209
#Sta/Elev= 30
       0   52.57   302.4   50.87   330.6   47.84   530.1   51.21  1622.8   48.05
  2870.9   50.87    3499   46.49  3974.3   50.16  4054.3   47.53  5167.9    49.5
  5715.8    41.4  5717.3   39.39    5807   41.42  5810.9   43.82  6215.2   46.03
  6365.2   43.32  6705.8   46.82  7577.2   45.13  7751.9   49.51  7781.5   48.87
  7801.3   44.22  8130.9   44.19    8154   49.18  8361.5   50.09  8394.5   47.74
  8739.5   50.97 10587.7   49.35 10624.1   52.08 11041.3   49.19 11614.4   52.39
#Mann= 3 ,-1,0
       0    .145       0  5715.8    .045       0    5807    .145       0
Bank Sta=5715.8,5807
XS Rating Curve= 0 ,0
Exp/Cntr=0.3,0.1

Type RM Length L Ch R = 1 ,8205    ,704.9,704.9,704.9
BEGIN DESCRIPTION:
Indian Field Swamp 16.0
END DESCRIPTION:
XS GIS Cut Line= 6
2154070.84598054455176.0659308592151928.91807812453837.618865749
      2148467.83       452393.97      2146194.13       451666.13
2144581.44899013451668.8873124112142503.57243857452518.391337847
#Sta/Elev= 30
       0   52.73   467.5   49.41  2838.9   50.41  3286.9    46.5    3422   49.54
  4688.9   50.12  5229.6   48.95  5339.6   45.71  5439.2   47.58  5545.8   43.46
  5698.9   45.25  5723.6   48.99  5799.1   43.29  6236.7   41.71  6238.2   38.71
  6326.4   38.71  6327.9   41.71  6746.8   46.27  7250.7   44.19  7597.9   47.95
  7625.4   44.19  8404.2   44.19  8550.5    49.7  9840.2    48.6  9866.6   51.86
  9889.8    48.7 10111.1   48.86 10144.2    52.7 10170.6   48.67 12526.4   52.12
#Mann= 3 ,-1,0
       0     .14       0  6236.7     .05       0  6327.9     .14       0
Bank Sta=6236.7,6327.9
XS Rating Curve= 0 ,0
Exp/Cntr=0.3,0.1

Type RM Length L Ch R = 1 ,7500    ,500,500,500
BEGIN DESCRIPTION:
Indian Field Swamp 15.0
END DESCRIPTION:
XS GIS Cut Line= 6
2154134.84503504455031.6724256412152930.91302671454166.026778041
2151967.39927639453614.2867224542149025.45629518452081.501278751
2148924.23875212451965.8240866832145843.75054098450470.828567666
#Sta/Elev= 30
       0   51.98  1991.2   48.34    2235   51.87  3325.5   46.42  4924.7   49.26
    5066   43.78  5092.3   48.53  5239.3   49.17  5276.3   44.39  5298.5   48.72
  5346.6   44.11  5440.2   48.34  5461.3   43.56    5761   43.79    5833   47.31
  5965.2   40.81  5966.7   37.81  6054.9   37.81  6056.4   40.81  6202.3   44.38
  6962.8   45.34  7043.5   49.54  7094.9   44.22  7608.6   44.19  7939.2   50.51
  8757.9   45.12  8813.1   49.37    9175   51.75  9413.2   47.09  9488.8   51.15
#Mann= 3 ,-1,0
       0    .145       0  5965.2    .045       0  6056.4    .145       0
Bank Sta=5965.2,6056.4
XS Rating Curve= 0 ,0
Exp/Cntr=0.3,0.1

Type RM Length L Ch R = 1 ,7000    ,500,500,500
BEGIN DESCRIPTION:
Indian Field Swamp 14.0
END DESCRIPTION:
XS GIS Cut Line= 6
2154043.94929509454844.8378634452152696.42365759453705.049323866
2152243.14562754453357.333242748 2149312.5580929451700.294985268
2146853.67890433450443.8554862412145839.32351643450410.925263244
#Sta/Elev= 30
       0    52.3    2034   47.15  2274.9   50.01  2352.5   46.85  2640.9   51.15
  2830.3   46.84    3171   45.69  4543.8    48.3  4566.5   46.01  4879.5   49.04
  5170.4   43.46  5516.5   44.53  5597.4   43.16  5604.8   40.56  5606.3   37.56
  5694.5   37.56    5696   40.56  5740.4   43.76  7008.1   44.19  7122.3   48.99
  7375.9   49.88  8322.7   45.13    8390   49.26  8644.4   51.06  8762.6   49.78
  8821.7   45.65  8864.4   48.74  9097.5   49.29  9402.9   45.69  9479.3      51
#Mann= 3 ,-1,0
       0     .14       0  5604.8    .045       0    5696     .11       0
Bank Sta=5604.8,5696
XS Rating Curve= 0 ,0
Exp/Cntr=0.3,0.1

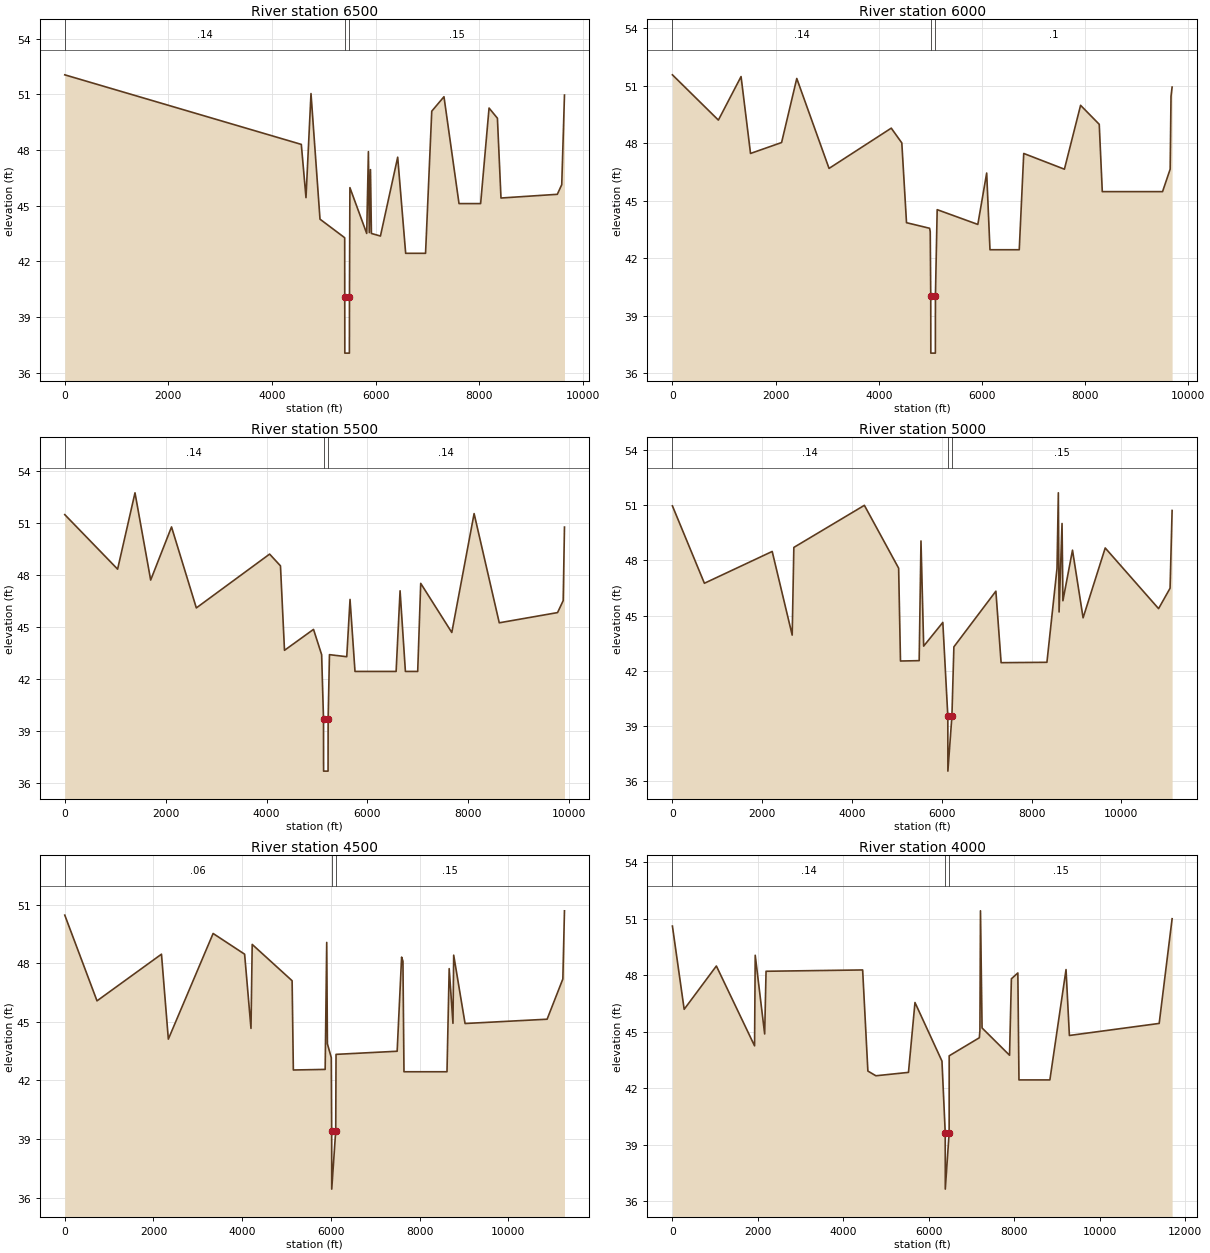
Type RM Length L Ch R = 1 ,6500    ,500,500,500
BEGIN DESCRIPTION:
Indian Field Swamp 13.0
END DESCRIPTION:
XS GIS Cut Line= 6
 2154014.1535733454752.4705832162152178.86597091453053.619211784
2149831.44377273451519.1470225812149649.78885165451331.567551284
2147249.30183184450199.7631768182145827.12337487450261.308804722
#Sta/Elev= 30
       0   52.06  4565.2   48.31  4655.4   45.44    4752   51.05  4925.9   44.28
  5402.3   43.28  5403.4   40.06  5404.9   37.06  5493.1   37.06  5494.6   40.06
  5503.1   45.98  5827.4   43.51    5860   47.92  5878.2   43.56  5899.9   46.95
  5918.1   43.51  6092.2   43.37  6425.2   47.62  6579.1   42.44  6962.9   42.44
  7082.7    50.1  7318.5   50.88  7608.7   45.12    8026   45.12  8188.6   50.27
  8349.9   49.72  8418.8   45.42  9506.1   45.62  9591.5   46.14  9644.1   50.97
#Mann= 3 ,-1,0
       0     .14       0  5403.4    .045       0  5494.6     .15       0
Bank Sta=5403.4,5494.6
XS Rating Curve= 0 ,0
Exp/Cntr=0.3,0.1

Type RM Length L Ch R = 1 ,6000    ,500,500,500
BEGIN DESCRIPTION:
Indian Field Swamp 12.0
END DESCRIPTION:
XS GIS Cut Line= 6
2153948.56330092454600.8536882782153067.72960545453461.213093488
2150084.93265684451254.2301313232149262.18856471  450818.8834278
2147547.04493119450070.0315998662145812.33101788 450089.27004718
#Sta/Elev= 30
       0   51.56   891.2    49.2  1330.9   51.47  1514.4   47.46  2116.7   48.03
  2411.1   51.37  3036.8   46.68    4243   48.78  4447.5   48.01  4538.6   43.85
  4986.5   43.56  4998.6   43.38  5008.3   40.05  5009.8   37.05    5098   37.05
  5099.5   40.05  5133.3   44.53  5921.3   43.76  6092.9   46.44  6156.9   42.44
  6724.4   42.44  6811.5   47.46    7600   46.64  7913.6   49.97  8275.3   48.98
  8334.4   45.47  9502.7   45.47  9650.4   46.64  9666.8   50.44  9688.2   50.92
#Mann= 3 ,-1,0
       0     .14       0  5008.3    .045       0  5099.5      .1       0
Bank Sta=5008.3,5099.5
XS Rating Curve= 0 ,0
Exp/Cntr=0.3,0.1

Type RM Length L Ch R = 1 ,5500    ,500,500,500
BEGIN DESCRIPTION:
Indian Field Swamp 11.0
END DESCRIPTION:
XS GIS Cut Line= 6
2153948.88767345454514.146280916 2153201.0221931453158.895496262
2150246.74955654 450767.84565668 2149227.5682147450347.510714428
2148175.63725547450049.9063162632145818.11325472450010.686924751
#Sta/Elev= 30
       0    51.5  1047.5   48.35  1392.3   52.76  1703.2   47.72  2116.5   50.79
  2608.3   46.11  4061.2   49.22  4276.5   48.54  4356.2   43.66  4931.6   44.87
  5092.6   43.41  5129.8   39.68  5131.3   36.68  5219.9   36.68  5221.4   39.68
  5247.7   43.41  5590.7   43.29  5655.6    46.6    5754   42.44  6569.2   42.44
  6647.6    47.1  6753.3   42.44  6997.1   42.44  7056.9   47.53  7673.3   44.69
  8115.4   51.56  8614.2   45.25  9769.9   45.84  9881.6   46.53  9907.1   50.78
#Mann= 3 ,-1,0
       0     .14       0  5129.8     .05       0  5221.4     .14       0
Bank Sta=5129.8,5221.4
XS Rating Curve= 0 ,0
Exp/Cntr=0.3,0.1

Type RM Length L Ch R = 1 ,5000    ,500,500,500
BEGIN DESCRIPTION:
Indian Field Swamp 10.0
END DESCRIPTION:
XS GIS Cut Line= 6
2156143.73844631453382.6631840412153685.87995884452183.132631824
2150707.30761258450549.2870492212150627.85152846450521.092954854
2148400.86645325449854.7036954442145811.19917017449946.593674921
#Sta/Elev= 30
       0   50.97   712.6   46.76  2222.9   48.49  2668.3   43.94  2705.2   48.71
  4276.7      51  5039.8   47.58  5080.9   42.53  5497.3   42.55  5537.6   49.06
  5597.4   43.34  6024.1   44.63  6135.4   39.54  6136.9   36.54    6227   39.54
  6270.6    43.3  7206.1   46.33  7322.6   42.44  8343.4   42.46  8568.3   47.57
  8597.8   51.68  8614.2    45.2    8680   50.01  8699.6   45.81  8913.1   48.56
  9149.1   44.88    9642   48.68 10830.7   45.38 11086.7   46.49 11132.4   50.72
#Mann= 3 ,-1,0
       0     .14       0  6135.4    .045       0    6227     .15       0
Bank Sta=6135.4,6227
XS Rating Curve= 0 ,0
Exp/Cntr=0.3,0.1

Type RM Length L Ch R = 1 ,4500    ,500,500,500
BEGIN DESCRIPTION:
Indian Field Swamp 9.0
END DESCRIPTION:
XS GIS Cut Line= 6
2156229.79618767453116.0946929922152532.09964985451168.702884613
2151034.07061496450207.5564410892150911.67817091450114.935132074
2148825.25004542449701.6257755612145800.25760503449864.716339633
#Sta/Elev= 30
       0   50.46   726.9   46.07  2180.8   48.46  2335.6   44.11  3345.4   49.52
  4055.7   48.46  4199.4   44.66  4226.7   48.96  5126.8    47.1  5154.6   42.53
  5872.1   42.56  5907.1   49.06  5922.7   43.87  6010.5   43.16  6018.8   39.43
  6020.3   36.43  6110.4   39.43  6117.3   43.33  7495.6   43.49  7595.9   48.31
    7626    48.1  7649.4   42.44  8619.5   42.44    8669   47.72  8754.2   44.92
  8770.6   48.41    9027   44.91 10877.2   45.13 11232.2   47.19 11268.9   50.68
#Mann= 3 ,-1,0
       0     .06       0  6018.8     .04       0  6110.4     .15       0
Bank Sta=6018.8,6110.4
XS Rating Curve= 0 ,0
Exp/Cntr=0.3,0.1

Type RM Length L Ch R = 1 ,4000    ,500,500,500
BEGIN DESCRIPTION:
Indian Field Swamp 8.0
END DESCRIPTION:
XS GIS Cut Line= 6
2156552.96264677452974.389566591      2151015.33       449709.73
2150922.24456206449667.724485969 2150371.3701228449524.906503489
2149623.72752917449486.4016294382145787.58791659 449704.19097259
#Sta/Elev= 30
       0   50.61     275   46.19  1028.4   48.49  1921.9   44.25  1937.1   49.06
  2158.3   44.88  2190.7   48.21  4450.4   48.28    4573   42.91  4760.2   42.66
  5522.5   42.84  5674.8   46.55  6306.2   43.44  6382.5   39.64    6384   36.64
  6474.1   39.64  6475.2   43.72    7181   44.68  7194.1   45.07  7207.2   51.42
  7244.2    45.2  7887.4   43.75  7930.2   47.81  8081.4   48.12  8107.7   42.44
  8830.8   42.44  9208.8    48.3  9287.2    44.8   11388   45.44 11690.6      51
#Mann= 3 ,-1,0
       0     .14       0  6382.5     .04       0  6474.1     .15       0
Bank Sta=6382.5,6474.1
XS Rating Curve= 0 ,0
Exp/Cntr=0.3,0.1