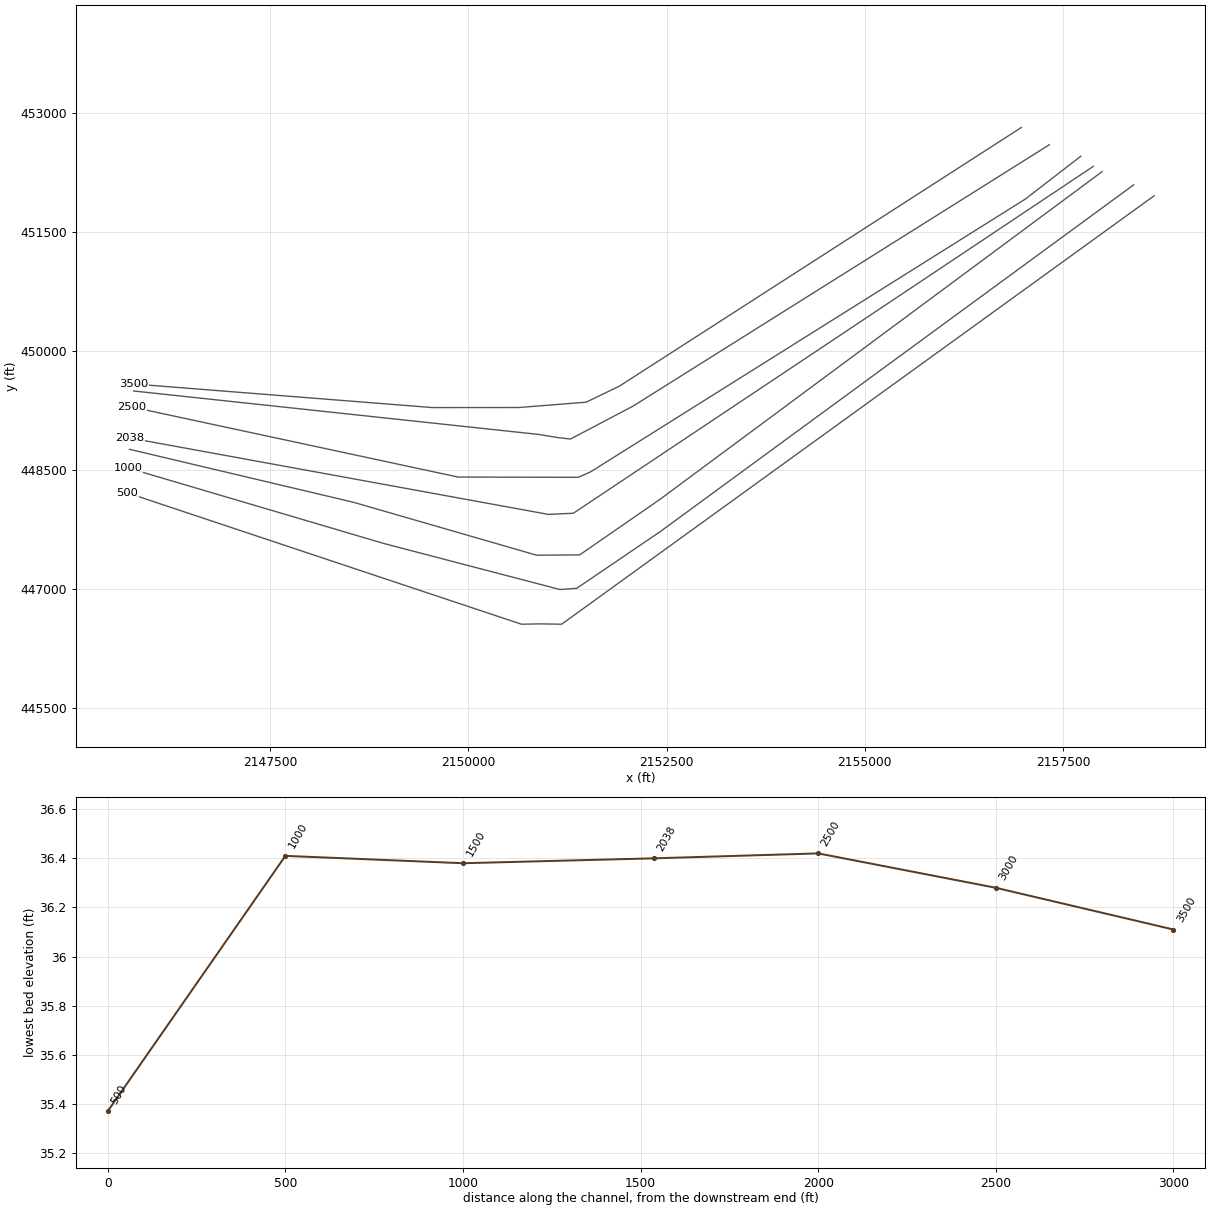
HEC-RAS study IndianFieldsSwamp.prj: S-18-19 over Indian Fields Swamp

--- IndianFieldsSwamp.g14 (geometry) --- (continued)

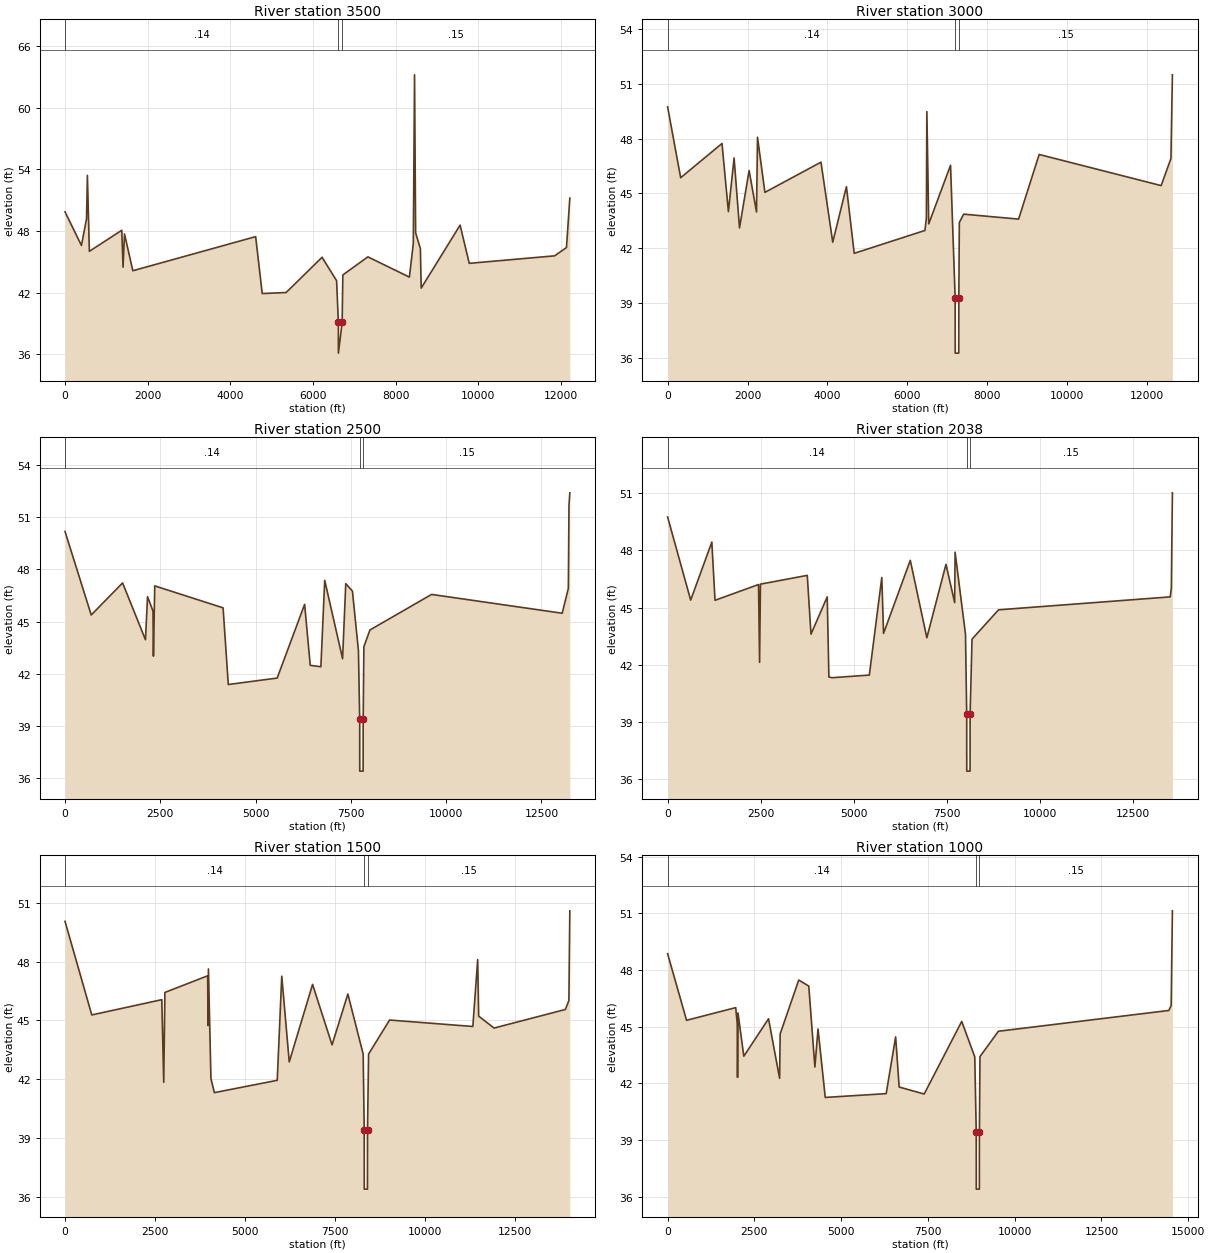
Type RM Length L Ch R = 1 ,3500    ,500,500,500
BEGIN DESCRIPTION:
Indian Field Swamp 7.0
END DESCRIPTION:
XS GIS Cut Line= 6
2156973.30597892452814.9628618842151905.77186854449554.205726693
 2151486.1382397449351.6912670112150640.24163196449284.467695535
2149549.88642728 449283.607101542145779.32640585449581.416006209
#Sta/Elev= 30
       0   49.86   397.1   46.59   520.3   49.18   541.1   53.41   589.1   46.02
    1373   48.07  1404.2   44.48  1439.4   47.71  1640.7   44.13  4613.3   47.45
  4772.3   41.91  5350.6   42.01  6220.3   45.44  6572.3   43.16  6614.4   39.11
  6615.9   36.11    6706   39.11  6723.2   43.72    7329   45.48  8333.3   43.51
  8428.5   46.78  8458.1    63.2  8484.5   47.82  8599.7   46.27  8619.4   42.44
  9560.9   48.57  9781.9   44.85 11847.3   45.58 12135.1   46.39   12216    51.2
#Mann= 3 ,-1,0
       0     .14       0  6614.4     .04       0    6706     .15       0
Bank Sta=6614.4,6706
XS Rating Curve= 0 ,0
Exp/Cntr=0.3,0.1

Type RM Length L Ch R = 1 ,3000    ,500,500,500
BEGIN DESCRIPTION:
Indian Field Swamp 6.0
END DESCRIPTION:
XS GIS Cut Line= 6
2157327.00069727452597.9401963912152077.86642383  449302.3686172
2151288.60229359448886.966602292      2151138.17         448904.
2150882.56909873448945.6207283532145780.58207696449492.870951408
#Sta/Elev= 30
       0   49.73   326.8   45.86  1361.1   47.73  1521.2   44.01  1663.4   46.94
  1799.2   43.12  2039.4   46.25  2224.7   43.99  2249.4   48.07  2434.7   45.06
  3837.3   46.71  4131.9   42.34  4474.6   45.37  4669.7   41.73    6439   42.98
  6474.9   43.65    6487   49.47  6534.5   43.34  7079.7   46.54  7195.4   39.28
  7196.9   36.28  7285.5   36.28    7287   39.28    7300  43.415  7408.8   43.87
  8782.5    43.6  9297.4   47.13 12349.9   45.43 12594.5   46.91 12631.4   51.48
#Mann= 3 ,-1,0
       0     .14       0  7195.4     .04       0    7287     .15       0
Bank Sta=7195.4,7287
XS Rating Curve= 0 ,0
Exp/Cntr=0.3,0.1

Type RM Length L Ch R = 1 ,2500    ,461.6,461.6,461.6
BEGIN DESCRIPTION:
Indian Field Swamp 5.0
END DESCRIPTION:
XS GIS Cut Line= 6
2157721.95583503452452.3162289862157025.33976343451913.919599308
 2151539.2185051448471.5030162622151385.96382913448404.388172181
      2149871.24       448407.592145759.80947622449290.509531196
#Sta/Elev= 30
       0   50.17   687.4   45.38  1510.4   47.22  2110.1   43.96  2164.4   46.43
  2307.7   45.61  2319.3   43.02  2354.2   47.05  4146.8   45.79  4283.5   41.39
  5566.2   41.76  6286.5   45.99  6433.7   42.49  6712.6   42.41  6813.6   47.37
  7282.1   42.87  7365.6   47.18  7540.6   46.75  7698.1   43.34  7731.1   39.42
  7732.6   36.42  7821.2   36.42  7822.7   39.42    7841   43.56    8000   44.52
  9617.6   46.56 13044.5   45.48 13205.6   46.91 13222.4   51.67 13244.3   52.39
#Mann= 3 ,-1,0
       0     .14       0  7731.1     .04       0  7822.7     .15       0
Bank Sta=7731.1,7822.7
XS Rating Curve= 0 ,0
Exp/Cntr=0.3,0.1

Type RM Length L Ch R = 1 ,2038    ,538.4,538.4,538.4
XS GIS Cut Line= 4
 2157880.7249684452325.1354826882151325.22474968447951.639678302
2151010.75028563447936.8032972992145736.95931787448899.388552181
#Sta/Elev= 30
       0   49.76   619.7   45.39  1187.7   48.44  1273.3   45.38  2442.2   46.21
  2469.8   42.12  2493.5   46.23  3750.9   46.69  3850.5    43.6  4286.3   45.56
  4331.2   41.35  4413.2   41.31  5417.3   41.45  5751.9   46.58  5799.3   43.64
  6517.2   47.48  6961.7   43.41  7475.8   47.27  7708.6   45.26  7720.4   47.91
    8000   43.59    8032    39.4  8033.5    36.4  8122.1    36.4  8123.6    39.4
    8175   43.34  8887.8   44.88 13497.2   45.56 13527.9   46.02 13556.2   51.03
#Mann= 3 ,-1,0
       0     .14       0    8032     .04       0  8123.6     .15       0
Bank Sta=8032,8123.6
XS Rating Curve= 0 ,0
Exp/Cntr(USF)=0,0
Exp/Cntr=0.3,0.1

Type RM Length L Ch R = 1 ,1500    ,500,500,500
BEGIN DESCRIPTION:
Indian Field Swamp 3.0
END DESCRIPTION:
XS GIS Cut Line= 6
2157992.83778257452259.4005323562152410.37632808448121.816367634
      2151404.55       447426.27      2150860.73       447422.71
2148557.12539852448088.4826194722145729.69058938448757.488356612
#Sta/Elev= 30
       0   50.06   742.7   45.28  2686.9   46.06  2741.1   41.84  2773.8   46.43
  3961.5   47.28  3970.8   44.74  3982.5   47.63  4051.9   42.03  4146.8   41.31
  5893.6   41.94    6019   47.26  6226.8   42.88  6874.5   46.84  7415.8   43.75
  7854.7   46.35    8280   43.28  8308.8   39.38  8310.3   36.38  8398.9   36.38
  8400.4   39.38    8430   43.28  9013.4   45.02 11325.4   44.69 11460.3   48.11
 11487.2   45.22 11915.5   44.61   13895   45.56 13992.8   46.02 14018.8    50.6
#Mann= 3 ,-1,0
       0     .14       0  8308.8     .04       0  8400.4     .15       0
Bank Sta=8308.8,8400.4
XS Rating Curve= 0 ,0
Exp/Cntr=0.3,0.1

Type RM Length L Ch R = 1 ,1000    ,500,500,500
BEGIN DESCRIPTION:
Indian Field Swamp 2.0
END DESCRIPTION:
XS GIS Cut Line= 6
2158389.90592361452092.3070353522152426.02271189447724.037946857
      2151367.75       447005.12  2151156.510192446989.570430701
2148940.97376942447568.5715319862145707.89265772448522.858264767
#Sta/Elev= 30
       0   48.86   546.1   45.34    1962   46.01  2006.4   45.16  2014.5   42.32
  2027.8   45.73  2195.8   43.44  2908.3   45.42  3226.7   42.27  3242.9   44.62
  3778.6   47.47  4067.4   47.15  4243.6   42.87    4334   44.88  4542.4   41.26
  6297.8   41.46  6570.3   44.46    6672   41.81  7392.5   41.44  8474.4   45.28
    8850   43.41  8892.7   39.41  8894.2   36.41  8982.8   36.41  8984.3   39.41
    9000   43.42    9531   44.76 14441.6   45.86 14509.2   46.13 14544.6   51.13
#Mann= 3 ,-1,0
       0     .14       0  8892.7     .04       0  8984.3     .15       0
Bank Sta=8892.7,8984.3
XS Rating Curve= 0 ,0
Exp/Cntr=0.3,0.1

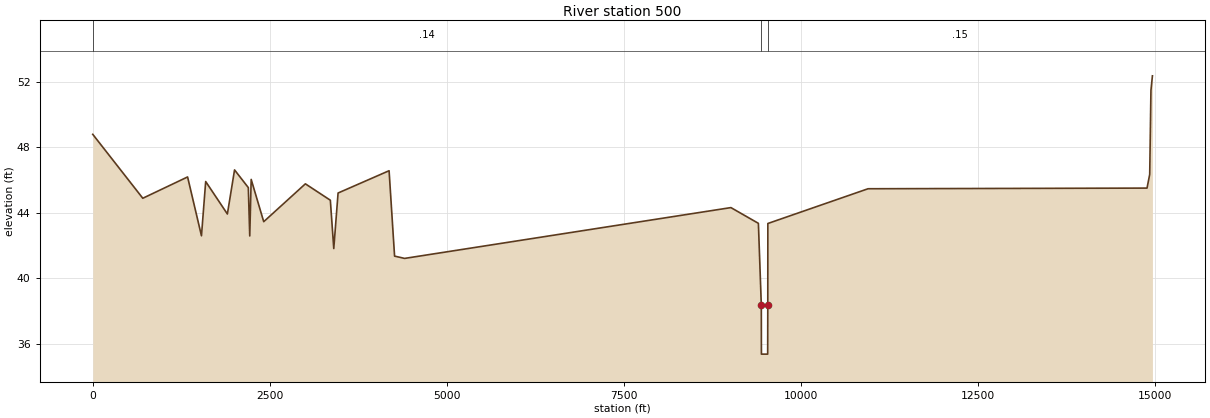
Type RM Length L Ch R = 1 ,500     ,,,
BEGIN DESCRIPTION:
Indian Field Swamp 1.0
END DESCRIPTION:
XS GIS Cut Line= 5
 2158646.4682101451953.477504352      2151177.11       446552.28
      2150907.89       446556.57      2150671.11       446552.28
2145698.99722281448209.147217397
#Sta/Elev= 30
       0   48.78   706.4   44.88    1339   46.18    1535   42.59  1594.6    45.9
    1901   43.92  2002.3   46.61  2196.6   45.53  2216.9   42.58  2237.1   46.03
  2414.2   43.45  3002.5   45.76    3355   44.76  3403.4   41.81  3464.2    45.2
  4184.6   46.56    4262   41.35  4403.7   41.21  9011.9   44.31    9400   43.35
  9441.1   38.37  9442.6   35.37  9531.2   35.37  9532.7   38.37  9533.6   43.34
 10948.5   45.46 14888.3    45.5 14926.3   46.34 14943.6   51.46 14964.6   52.35
#Mann= 3 ,-1,0
       0     .14       0  9441.1     .04       0  9532.7     .15       0
Bank Sta=9441.1,9532.7
XS Rating Curve= 0 ,0
Exp/Cntr=0.3,0.1
LCMann Table=0

Chan Stop Cuts=-1
Use User Specified Reach Order=0
Composite Channel Slope=5

--- IndianFieldsSwamp.g01 (geometry) ---

Geom Title=Natural
Program Version=6.60

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
River Reach=Indian Field Swa,Reach-1

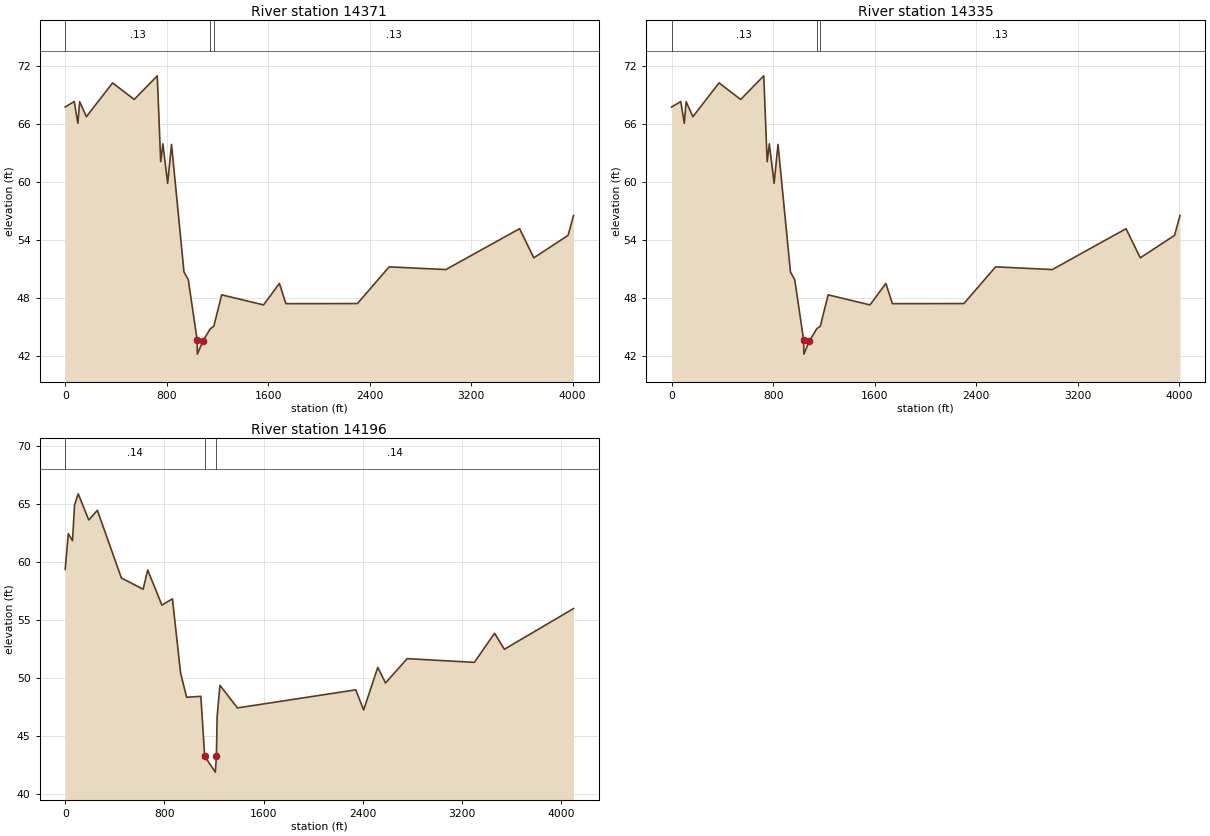
Type RM Length L Ch R = 1 ,14371   ,35.3,35.3,35.3
BEGIN DESCRIPTION:
Wire Road at Indian Field - US
END DESCRIPTION:
XS GIS Cut Line= 6
2150333.42248984  457818.40776572149728.21248984  457863.8777657
2148587.55000415458211.3003852132148247.66440599  458189.1377657
 2147994.4660008458132.4137917952146909.49685185459306.712552653
#Sta/Elev= 30
       0   67.73    71.3    68.3    99.9   66.06     114   68.28   167.1   66.73
   373.6   70.22   544.1   68.51   725.8   70.95   752.8   62.08   769.9   63.93
   807.5   59.85   838.2   63.87   936.4    50.7   970.1   49.91    1040  43.698
  1041.9   42.22    1085  43.563 1143.66   44.84 1171.83   45.11  1233.5   48.34
  1563.5    47.3  1688.6   49.52  1739.8   47.43  2303.6   47.44  2553.8   51.23
  3000.9   50.95  3581.9   55.17  3694.1   52.16  3964.3   54.48  4007.2   56.53
#Mann= 3 ,-1,0
       0     .13       0 1143.66    .045       0 1171.83     .13       0
Bank Sta=1040,1085
XS Rating Curve= 0 ,0
Exp/Cntr=0.3,0.1

Type RM Length L Ch R = 1 ,14335   ,139.4,139.4,139.4
BEGIN DESCRIPTION:
Wire Road at Indian Field - US
END DESCRIPTION:
XS GIS Cut Line= 6
2150329.49883881457784.4027901322149724.28883881457829.872790132
2148583.62635312458177.2954096452148243.74075496458155.132790132
2147990.54234977458098.4088162272146905.57320082459272.707577085
#Sta/Elev= 30
       0   67.73    71.3    68.3    99.9   66.06     114   68.28   167.1   66.73
   373.6   70.22   544.1   68.51   725.8   70.95   752.8   62.08   769.9   63.93
   807.5   59.85   838.2   63.87   936.4    50.7   970.1   49.91    1040  43.698
  1041.9   42.22    1085  43.563 1143.66   44.84 1171.83   45.11  1233.5   48.34
  1563.5    47.3  1688.6   49.52  1739.8   47.43  2303.6   47.44  2553.8   51.23
  3000.9   50.95  3581.9   55.17  3694.1   52.16  3964.3   54.48  4007.2   56.53
#Mann= 3 ,-1,0
       0     .13       0 1143.66    .045       0 1171.83     .13       0
Bank Sta=1040,1085
XS Rating Curve= 0 ,0
Exp/Cntr=0.3,0.1

Type RM Length L Ch R = 1 ,14196   ,572.1,572.1,572.1
BEGIN DESCRIPTION:
Wire Road at Indian Field - DS
END DESCRIPTION:
XS GIS Cut Line= 6
2150323.70635095457663.0944824492149589.22826132457723.219142731
2148557.91016933458039.7280789072148319.53207461458038.226249793
2147928.73818492457969.4063180592146859.36653229459215.052239341
#Sta/Elev= 30
       0   59.37      25   62.44      59   61.84    75.3   64.92   104.9   65.88
     190   63.62   259.3   64.46   453.1   58.62   628.7   57.65   665.4   59.31
   779.9   56.28     865   56.82   930.8   50.42   979.3   48.33  1094.2   48.41
    1125  43.235    1211   41.87 1219.69   43.27  1225.5   46.66  1248.1   49.36
  1389.4   47.41  2343.6   48.97  2407.3   47.23  2521.4   50.91  2583.8   49.56
  2758.3   51.66  3300.5   51.34  3463.4   53.85  3542.6   52.47  4100.4   55.98
#Mann= 3 ,-1,0
       0     .14       0    1125    .045       0 1219.69     .14       0
Bank Sta=1125,1219.69
XS Rating Curve= 0 ,0
Exp/Cntr=0.3,0.1

--- IndianFieldsSwamp.g02 (geometry) ---

Geom Title=Duplicate Effective
Program Version=6.60

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
River Reach=Indian Field Swa,Reach-1
Reach XY= 30
      2118288.29       525062.16      2118955.39       523528.35
      2120648.43        522700.4      2121312.48       520888.04
      2122993.51       519640.97       2124181.2       516753.99
      2127559.91       513322.44      2129580.58       512423.52
      2131677.85       512616.52      2137019.28       508872.32
      2139219.53       508913.64      2143396.56       507457.83
       2145551.5       505991.65      2148152.32       502646.04
      2150180.25       501860.21      2153790.57       496582.04
        2152978.       484744.12      2154459.86       478228.84
      2156305.04       474611.96      2155415.89       471733.58
      2154429.18        470712.2       2154493.3       466356.19
      2153350.16       462390.05       2152062.9       460666.57
      2149526.09       459190.34       2148865.8       457395.89
      2148459.05       452334.88      2150079.38       451415.63
       2151320.1       449436.34      2151206.67       446243.51

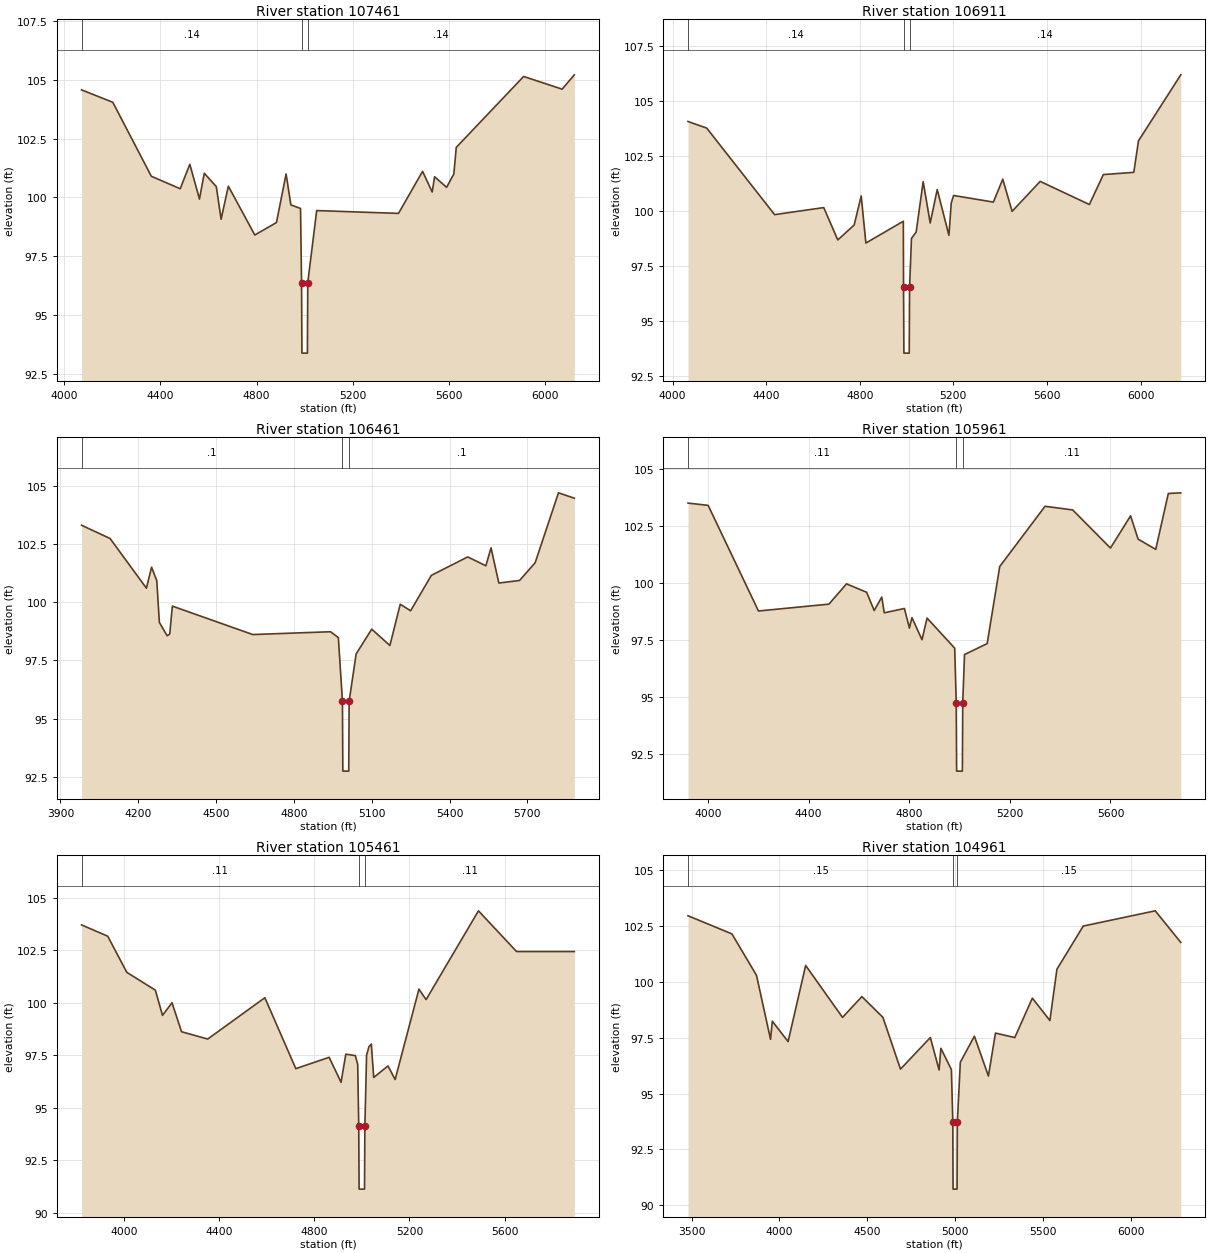
Type RM Length L Ch R = 1 ,107461  ,550,550,550
BEGIN DESCRIPTION:
Indian Field Swamp 215.0
END DESCRIPTION:
XS GIS Cut Line= 3
      2119186.83       525263.58      2118322.11       524928.98
      2117275.07       524529.67
#Sta/Elev= 30
  4072.8  104.58  4202.8  104.05  4362.8   100.9  4482.8  100.37  4522.8  101.41
  4562.8   99.93  4582.8  101.03  4632.8  100.46  4652.8   99.07  4682.8  100.48
  4792.8    98.4  4882.8   98.93  4922.8     101  4942.8   99.68  4982.8   99.53
  4987.1   96.37  4988.6   93.37  5011.4   93.37  5012.9   96.37    5050   99.44
    5390   99.32    5490  101.11    5530  100.23    5540  100.88    5590  100.43
    5620     101    5630  102.13    5910  105.15    6070  104.61  6120.6  105.22
#Mann= 3 ,-1,0
  4072.8     .14       0  4987.1    .045       0  5012.9     .14       0
Bank Sta=4987.1,5012.9
XS Rating Curve= 0 ,0
Exp/Cntr=0.3,0.1

Type RM Length L Ch R = 1 ,106911  ,450,450,450
BEGIN DESCRIPTION:
Indian Field Swamp 214.0
END DESCRIPTION:
XS GIS Cut Line= 3
      2119342.15       524828.18      2118506.08       524410.15
      2117424.59        523961.8
#Sta/Elev= 30
  4066.2  104.06  4146.2  103.76  4436.2   99.83  4646.2  100.15  4706.2   98.68
  4776.2   99.36  4806.2  100.68  4826.2   98.54  4986.2   99.53  4987.1   96.54
  4988.6   93.54  5011.4   93.54  5012.9   96.54    5021   98.75    5041   99.04
    5071  101.33    5101   99.45    5131  100.97    5181   98.89    5191  100.36
    5201   100.7    5371   100.4    5411  101.44    5451   99.98    5571  101.34
    5781  100.29    5841  101.65    5971  101.75    5991  103.18  6171.7  106.18
#Mann= 3 ,-1,0
  4066.2     .14       0  4987.1    .045       0  5012.9     .14       0
Bank Sta=4987.1,5012.9
XS Rating Curve= 0 ,0
Exp/Cntr=0.3,0.1

Type RM Length L Ch R = 1 ,106461  ,500,500,500
BEGIN DESCRIPTION:
Indian Field Swamp 213.0
END DESCRIPTION:
XS GIS Cut Line= 3
      2119537.68       524483.11      2118649.48       523984.26
      2117883.68        523548.7
#Sta/Elev= 30
  3981.3   103.3  4091.3  102.73  4231.3   100.6  4251.3   101.5  4271.3  100.92
  4281.3   99.13  4311.3   98.56  4321.3   98.63  4331.3   99.83  4641.3   98.61
  4941.3   98.73  4971.3   98.48  4987.1   95.75  4988.6   92.75  5011.4   92.75
  5012.9   95.75    5040   97.78    5100   98.84    5170   98.14    5210   99.91
    5250   99.63    5330  101.15    5470  101.94    5540  101.56    5560  102.33
    5590  100.82    5670  100.93    5730  101.69    5820  104.69    5881  104.46
#Mann= 3 ,-1,0
  3981.3      .1       0  4987.1    .045       0  5012.9      .1       0
Bank Sta=4987.1,5012.9
XS Rating Curve= 0 ,0
Exp/Cntr=0.3,0.1

Type RM Length L Ch R = 1 ,105961  ,500,500,500
BEGIN DESCRIPTION:
Indian Field Swamp 212.0
END DESCRIPTION:
XS GIS Cut Line= 3
      2119630.77       524382.86       2118918.9       523572.01
      2118297.08       522950.03
#Sta/Elev= 30
    3921  103.49    4001  103.39    4201   98.76    4481   99.06    4551   99.95
    4631   99.58    4661   98.78    4691   99.37    4701   98.68    4781   98.87
    4801   98.01    4811   98.47    4851    97.5    4871   98.45    4981   97.13
  4987.1   94.74  4988.6   91.74  5011.4   91.74  5012.9   94.74    5020   96.85
    5110   97.33    5160  100.71    5340  103.35    5450  103.19    5600  101.52
    5680  102.93    5710  101.91    5780  101.46    5830  103.91  5879.5  103.94
#Mann= 3 ,-1,0
    3921     .11       0  4987.1    .045       0  5012.9     .11       0
Bank Sta=4987.1,5012.9
XS Rating Curve= 0 ,0
Exp/Cntr=0.3,0.1

Type RM Length L Ch R = 1 ,105461  ,500,500,500
BEGIN DESCRIPTION:
Indian Field Swamp 211.0
END DESCRIPTION:
XS GIS Cut Line= 3
      2119778.39       524410.12      2119338.92       523318.02
      2118854.46       522568.33
#Sta/Elev= 30
  3822.8  103.72  3932.8  103.18  4012.8  101.46  4132.8  100.61  4162.8   99.41
  4202.8  100.01  4242.8   98.63  4352.8   98.28  4592.8  100.25  4722.8   96.87
  4862.8   97.41  4912.8   96.22  4932.8   97.56  4972.8   97.49  4982.8   97.07
  4987.1   94.13  4988.6   91.13  5011.4   91.13  5012.9   94.13    5020    97.5
    5030   97.92    5040   98.04    5050   96.45    5110      97    5140   96.35
    5240  100.66    5270  100.16    5490  104.39    5650  102.45  5892.6  102.45
#Mann= 3 ,-1,0
  3822.8     .11       0  4987.1    .045       0  5012.9     .11       0
Bank Sta=4987.1,5012.9
XS Rating Curve= 0 ,0
Exp/Cntr=0.3,0.1

Type RM Length L Ch R = 1 ,104961  ,500,500,500
BEGIN DESCRIPTION:
Indian Field Swamp 210.0
END DESCRIPTION:
XS GIS Cut Line= 3
      2120407.78       524576.23      2119817.64       523174.49
      2119302.35       521996.89
#Sta/Elev= 30
  3479.1  102.94  3729.1  102.13  3869.1  100.28  3949.1   97.42  3959.1   98.23
  4049.1   97.32  4149.1  100.72  4359.1    98.4  4469.1   99.33  4589.1    98.4
  4689.1   96.09  4859.1    97.5  4909.1   96.05  4919.1   97.02  4979.1   96.07
  4987.1   93.73  4988.6   90.73  5011.4   90.73  5012.9   93.73    5030    96.4
    5110   97.56    5190   95.78    5230    97.7    5340    97.5    5440   99.26
    5540   98.26    5580  100.55    5730  102.48    6140  103.16  6285.4  101.75
#Mann= 3 ,-1,0
  3479.1     .15       0  4987.1    .045       0  5012.9     .15       0
Bank Sta=4987.1,5012.9
XS Rating Curve= 0 ,0
Exp/Cntr=0.3,0.1

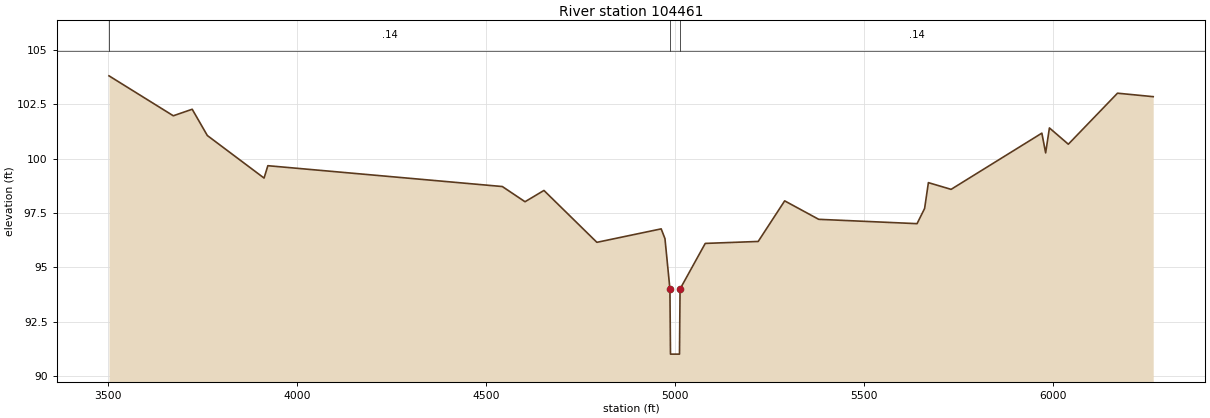
Type RM Length L Ch R = 1 ,104461  ,314,314,314
BEGIN DESCRIPTION:
Indian Field Swamp 209.0
END DESCRIPTION:
XS GIS Cut Line= 3
      2120848.52       524369.29       2120277.8       522985.89
       2119712.5        521854.9
#Sta/Elev= 30
  3503.5  103.82  3673.5  101.98  3723.5  102.28  3763.5  101.07  3913.5   99.11
  3923.5   99.68  4543.5   98.72  4603.5   98.02  4653.5   98.54  4793.5   96.15
  4963.5   96.77  4973.5   96.32  4986.6      94  4988.1      91  5011.9      91
  5013.4      94    5080    96.1    5220   96.19    5290   98.06    5380   97.21
    5640   97.01    5660   97.71    5670    98.9    5730   98.59    5970  101.18
    5980  100.27    5990  101.42    6040  100.67    6170  103.02  6264.4  102.86
#Mann= 3 ,-1,0
  3503.5     .14       0  4986.6    .045       0  5013.4     .14       0
Bank Sta=4986.6,5013.4
XS Rating Curve= 0 ,0
Exp/Cntr=0.5,0.3