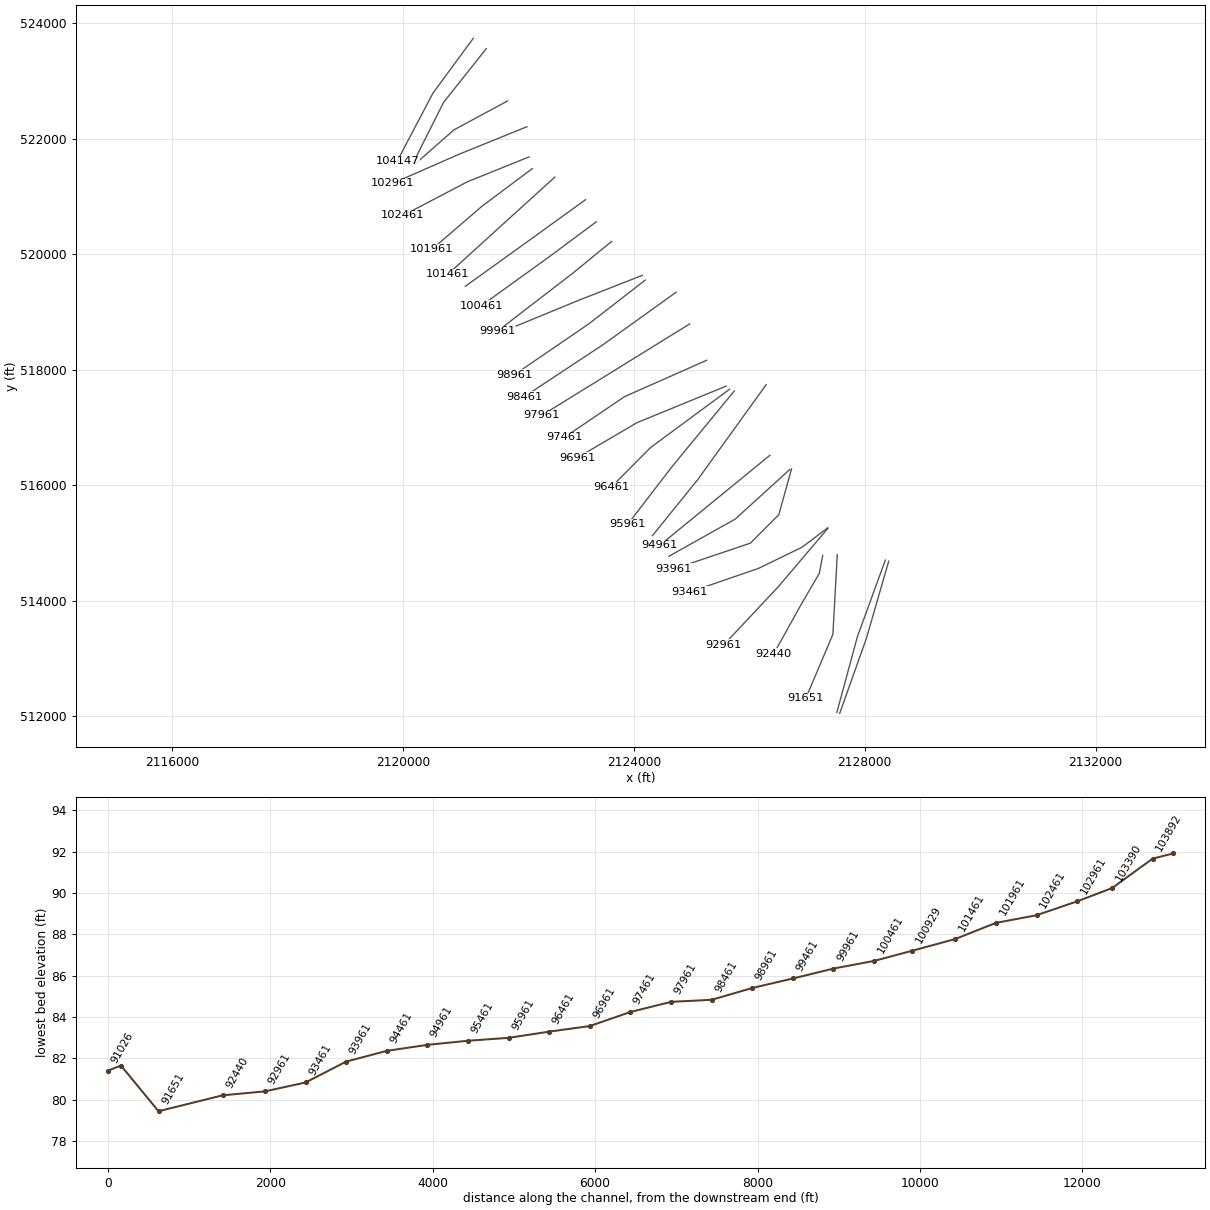
HEC-RAS study IndianFieldsSwamp.prj: S-18-19 over Indian Fields Swamp

--- IndianFieldsSwamp.g02 (geometry) --- (continued)

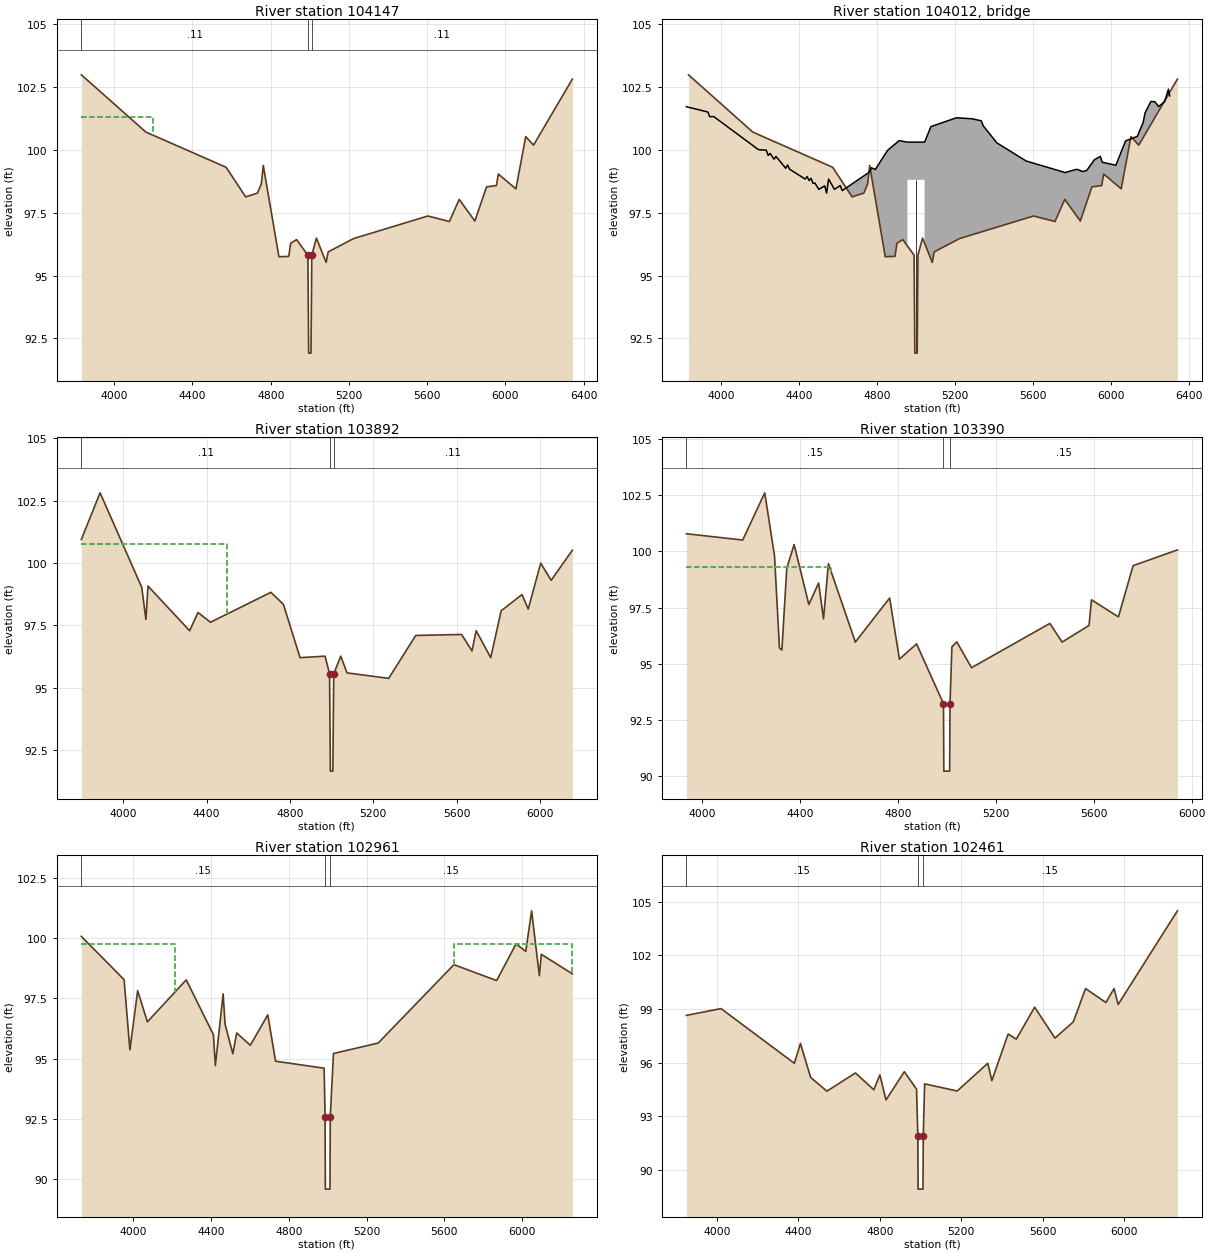
Type RM Length L Ch R = 1 ,104147  ,255,255,255
BEGIN DESCRIPTION:
Highway S-18-16 at Indian Field - US
END DESCRIPTION:
XS GIS Cut Line= 3
      2121219.57       523736.85      2120520.03       522784.71
      2119901.85       521608.79
#Sta/Elev= 30
    3832  102.99    4162  100.71    4572   99.31    4672   98.13    4732   98.28
    4752   98.65    4762   99.38    4842   95.75    4892   95.76    4902   96.28
    4932   96.43    4990   95.81    4994   91.91    5006   91.91    5010   95.81
  5033.5   96.49  5083.5   95.52  5093.5   95.94  5223.5   96.47  5603.5   97.37
  5713.5   97.15  5763.5   98.03  5843.5   97.17  5903.5   98.53  5953.5   98.58
  5963.5   99.04  6053.5   98.45  6103.5  100.53  6143.5  100.19    6342  102.82
#Mann= 3 ,-1,0
    3832     .11       0    4990    .045       0    5010     .11       0
#XS Ineff= 2 , 0
       0    4200   101.3               0
Permanent Ineff=
       F       F
Bank Sta=4990,5010
XS Rating Curve= 0 ,0
Exp/Cntr=0.5,0.3

Type RM Length L Ch R = 3 ,104012  ,,,
BEGIN DESCRIPTION:
Highway S-18-16 at Indian Field - TOR
Structure ID: LDS_IFS_09
Approximate Survey Structure
END DESCRIPTION:
Bridge Culvert--1,0,-1,-1, 0
Deck Dist Width WeirC Skew NumUp NumDn MinLoCord MaxHiCord MaxSubmerge Is_Ogee
117,36,3,0, 60, 60, , , 0.95, 0, 1,1,,
  3821.1  3931.1  3941.1  3961.1  4191.1  4231.1  4241.1  4251.1  4271.1  4281.1
  4331.1  4341.1  4351.1  4431.1  4441.1  4451.1  4461.1  4471.1  4481.1  4501.1
  4531.1  4541.1  4551.1  4581.1  4611.1  4621.1  4761.1  4771.1  4791.1  4853.5
  4913.5    4956    4956    5044    5044  5076.7  5207.8  5287.8  5335.2  5345.2
  5415.2  5565.2  5765.2  5825.2    5856    5876    5916    5946    5956    6026
    6076    6136    6166    6176    6206    6226    6246    6276    6296  6302.1
  101.72  101.51  101.32  101.33  100.01   99.99   99.78   99.86   99.63   99.74
   99.27    99.4   99.23   98.84   98.94   98.78   98.87   98.67   98.68   98.43
   98.57   98.28   98.84   98.43   98.58   98.38   99.12   99.29   99.22   99.98
  100.37  100.31  100.31  100.31  100.31  100.93  101.28  101.24  101.16  100.96
  100.28   99.56    99.1   99.23   99.14   99.18   99.61   99.74   99.51   99.39
  100.36  100.54  101.09  101.48  101.93  101.92  101.73  101.92  102.42  102.15
   71.91   71.91   71.91   71.91   71.91   71.91   71.91   71.91   71.91   71.91
   71.91   71.91   71.91   71.91   71.91   71.91   71.91   71.91   71.91   71.91
   71.91   71.91   71.91   71.91   71.91   71.91   71.91   71.91   71.91   71.91
   71.91   71.91   98.81   98.81   71.91   71.91   71.91   71.91   71.91   71.91
   71.91   71.91   71.91   71.91   71.91   71.91   71.91   71.91   71.91   71.91
   71.91   71.91   71.91   71.91   71.91   71.91   71.91   71.91   71.91   71.91
  3821.1  3931.1  3941.1  3961.1  4191.1  4231.1  4241.1  4251.1  4271.1  4281.1
  4331.1  4341.1  4351.1  4431.1  4441.1  4451.1  4461.1  4471.1  4481.1  4501.1
  4531.1  4541.1  4551.1  4581.1  4611.1  4621.1  4761.1  4771.1  4791.1  4853.5
  4913.5    4956    4956    5044    5044  5076.7  5207.8  5287.8  5335.2  5345.2
  5415.2  5565.2  5765.2  5825.2    5856    5876    5916    5946    5956    6026
    6076    6136    6166    6176    6206    6226    6246    6276    6296  6302.1
  101.72  101.51  101.32  101.33  100.01   99.99   99.78   99.86   99.63   99.74
   99.27    99.4   99.23   98.84   98.94   98.78   98.87   98.67   98.68   98.43
   98.57   98.28   98.84   98.43   98.58   98.38   99.12   99.29   99.22   99.98
  100.37  100.31  100.31  100.31  100.31  100.93  101.28  101.24  101.16  100.96
  100.28   99.56    99.1   99.23   99.14   99.18   99.61   99.74   99.51   99.39
  100.36  100.54  101.09  101.48  101.93  101.92  101.73  101.92  102.42  102.15
   71.91   71.91   71.91   71.91   71.91   71.91   71.91   71.91   71.91   71.91
   71.91   71.91   71.91   71.91   71.91   71.91   71.91   71.91   71.91   71.91
   71.91   71.91   71.91   71.91   71.91   71.91   71.91   71.91   71.91   71.91
   71.91   71.91   98.81   98.81   71.91   71.91   71.91   71.91   71.91   71.91
   71.91   71.91   71.91   71.91   71.91   71.91   71.91   71.91   71.91   71.91
   71.91   71.91   71.91   71.91   71.91   71.91   71.91   71.91   71.91   71.91
Pier Skew, UpSta & Num, DnSta & Num=  ,5000, 2 ,5000, 2 , 0 , 0 , 0 ,0,0
     1.5     1.5
   91.91   98.81
     1.5     1.5
   91.66   98.81
Abutment Skew #Up #Dn= , 2 , 2
    4956    4965
   98.81      96
    4956    4965
   98.81   96.18
Abutment Skew #Up #Dn= , 2 , 2
    5035    5044
   96.48   98.81
    5035    5044
   95.81   98.81
BR Coef= 1 , 1 , 0 ,1.25, 0 ,,,0.8,0,2,0,
WSPro=,,,, 1 ,,,, 0 ,,,, 0 ,,,,-1 ,-1 ,-1 , 0 , 0 , 0 , 0 , 0
BC Design=,, 0 ,, 0 ,,,,,,
BC HTab HWMax=102.99
BC Use User HTab Curves=0
BC User HTab FreeFlow(D)= 0

Type RM Length L Ch R = 1 ,103892  ,502,502,502
BEGIN DESCRIPTION:
Highway S-18-16 at Indian Field - DS
END DESCRIPTION:
XS GIS Cut Line= 3
      2121443.03       523555.15      2120705.39       522627.16
      2120179.32       521579.92
#Sta/Elev= 30
  3798.4  100.95  3888.4  102.82  4088.4   99.03  4108.4   97.74  4118.4   99.08
  4318.4   97.29  4358.4   98.02  4418.4   97.63  4708.4   98.83  4768.4   98.35
  4848.4   96.21  4968.4   96.27    4990   95.56    4994   91.66    5006   91.66
    5010   95.56  5043.9   96.27  5073.9    95.6  5273.9   95.38  5403.9    97.1
  5623.9   97.14  5673.9   96.48  5693.9   97.29  5763.9   96.21  5813.9   98.09
  5913.9   98.74  5943.9   98.16  6003.9     100  6053.9   99.31  6155.8  100.52
#Mann= 3 ,-1,0
  3798.4     .11       0    4990    .045       0    5010     .11       0
#XS Ineff= 2 , 0
       0    4500  100.76               0
Permanent Ineff=
       F       F
Bank Sta=4990,5010
XS Rating Curve= 0 ,0
Exp/Cntr=0.5,0.3

Type RM Length L Ch R = 1 ,103390  ,429,429,429
BEGIN DESCRIPTION:
Indian Field Swamp 207.0
END DESCRIPTION:
XS GIS Cut Line= 3
      2121813.39       522651.94      2120885.42       522151.57
      2120171.19       521523.77
#Sta/Elev= 30
  3936.8  100.79  4166.8  100.51  4256.8  102.61  4296.8    99.8  4316.8   95.71
  4326.8   95.62  4346.8   99.26  4376.8  100.31  4436.8   97.64  4476.8    98.6
  4496.8      97  4516.8   99.46  4626.8   95.97  4766.8   97.93  4806.8   95.21
  4876.8   95.89  4986.6   93.23  4988.1   90.23  5011.9   90.23  5013.4   93.23
  5021.1   95.76  5041.1   95.98  5101.1   94.83  5421.1    96.8  5471.1   95.97
  5581.1   96.71  5591.1   97.85  5701.1   97.09  5761.1   99.37    5942  100.07
#Mann= 3 ,-1,0
  3936.8     .15       0  4986.6    .045       0  5013.4     .15       0
#XS Ineff= 2 , 0
       0    4529   99.29               0
Permanent Ineff=
       F       F
Bank Sta=4986.6,5013.4
XS Rating Curve= 0 ,0
Exp/Cntr=0.3,0.1

Type RM Length L Ch R = 1 ,102961  ,500,500,500
BEGIN DESCRIPTION:
Indian Field Swamp 206.0
END DESCRIPTION:
XS GIS Cut Line= 3
      2122150.01       522206.14      2120974.78        521729.5
      2119820.93       521223.56
#Sta/Elev= 30
  3731.8  100.06  3951.8   98.27  3981.8   95.36  4021.8   97.81  4071.8   96.52
  4271.8   98.26  4411.8   95.99  4421.8   94.71  4461.8   97.68  4471.8   96.42
  4511.8    95.2  4531.8   96.06  4601.8   95.55  4691.8   96.81  4731.8   94.89
  4981.8    94.6  4986.6   92.59  4988.1   89.59  5011.9   89.59  5013.4   92.59
    5030   95.21    5260   95.64    5650   98.89    5870   98.23    5970   99.75
    6020   99.44    6050  101.12    6090   98.43    6100   99.32  6259.9   98.51
#Mann= 3 ,-1,0
  3731.8     .15       0  4986.6    .045       0  5013.4     .15       0
#XS Ineff= 2 , 0
       0  4215.7   99.74  5652.3       0   99.74
Permanent Ineff=
       F       F
Bank Sta=4986.6,5013.4
XS Rating Curve= 0 ,0
Exp/Cntr=0.3,0.1

Type RM Length L Ch R = 1 ,102461  ,500,500,500
BEGIN DESCRIPTION:
Indian Field Swamp 205.0
END DESCRIPTION:
XS GIS Cut Line= 3
      2122186.47       521683.03      2121120.25        521253.2
      2120002.95        520668.6
#Sta/Elev= 30
  3850.4   98.64  4020.4   99.02  4380.4   95.96  4410.4   97.07  4460.4   95.17
  4540.4    94.4  4680.4   95.42  4770.4   94.48  4800.4   95.31  4830.4   93.91
  4920.4   95.49  4980.4   94.51  4986.6   91.92  4988.1   88.92  5011.9   88.92
  5013.4   91.92    5020   94.81    5180   94.41    5330   95.96    5350   94.99
    5430    97.6    5470   97.31    5560    99.1    5660   97.37    5750   98.28
    5810  100.14    5910   99.36    5950  100.14    5970   99.25    6261  104.49
#Mann= 3 ,-1,0
  3850.4     .15       0  4986.6    .045       0  5013.4     .15       0
Bank Sta=4986.6,5013.4
XS Rating Curve= 0 ,0
Exp/Cntr=0.3,0.1

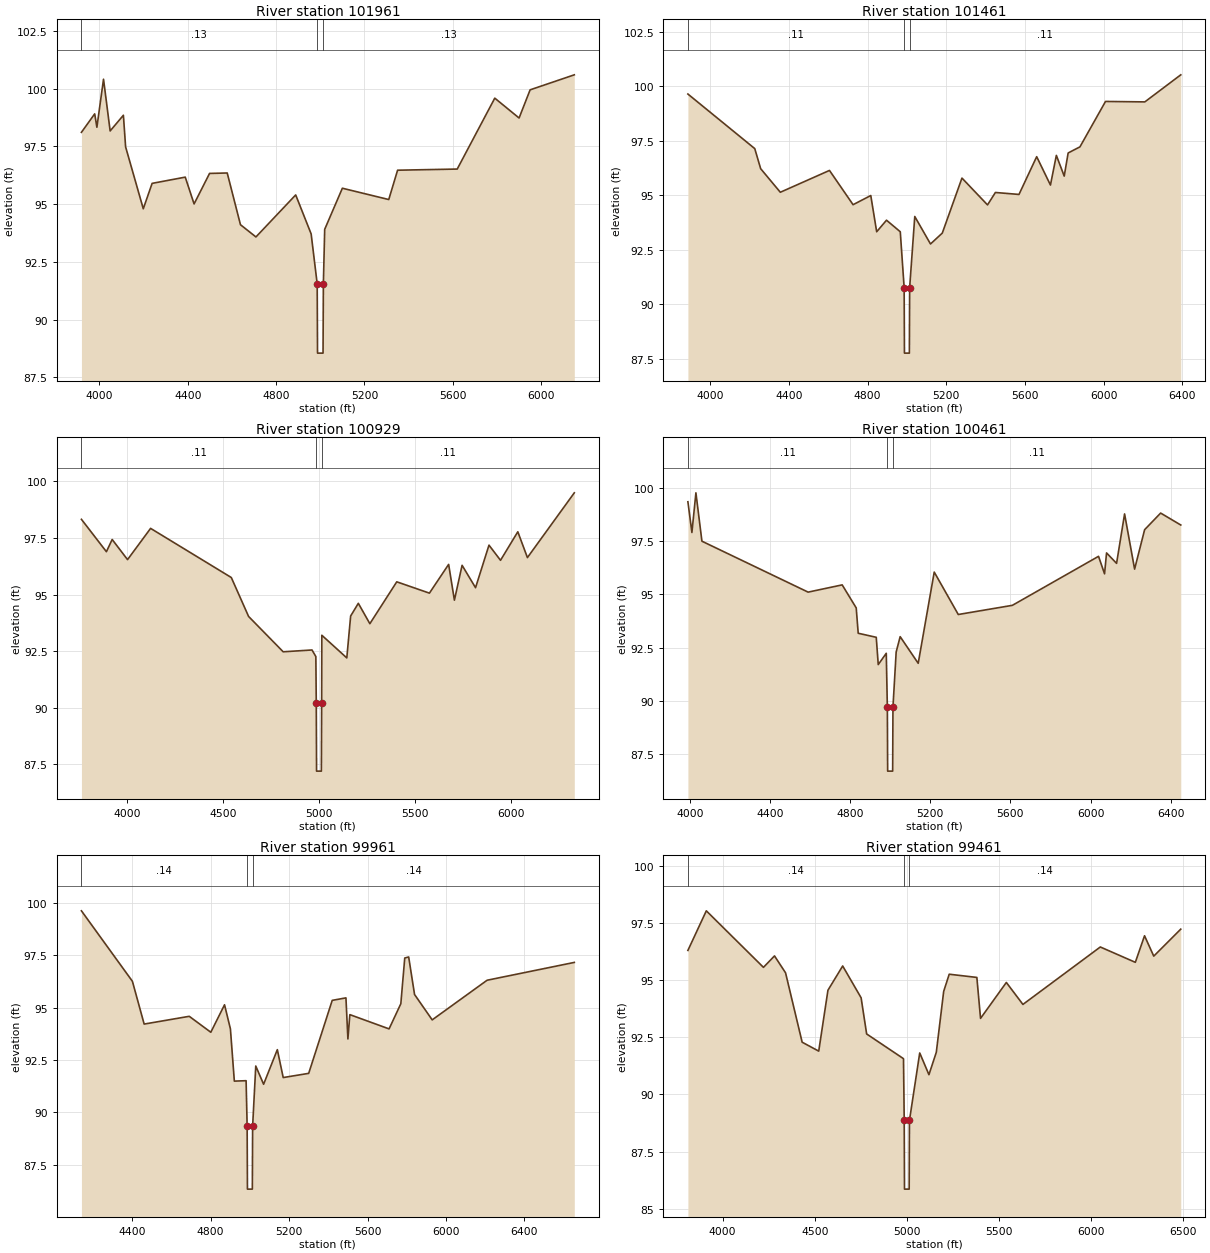
Type RM Length L Ch R = 1 ,101961  ,500,500,500
BEGIN DESCRIPTION:
Indian Field Swamp 204.0
END DESCRIPTION:
XS GIS Cut Line= 3
      2122241.96       521480.01      2121375.98       520832.48
      2120503.94       520082.78
#Sta/Elev= 30
  3918.7   98.11  3978.7   98.91  3988.7   98.33  4018.7  100.41  4048.7   98.17
  4108.7   98.85  4118.7   97.48  4198.7    94.8  4238.7    95.9  4388.7   96.17
  4428.7   95.01  4498.7   96.33  4578.7   96.35  4638.7   94.11  4708.7   93.58
  4888.7    95.4  4958.7   93.71    4986   91.55  4987.5   88.55  5012.5   88.55
    5014   91.55    5020   93.91    5100   95.69    5310    95.2    5350   96.47
    5620   96.52    5790   99.59    5900   98.73    5950   99.95    6150   100.6
#Mann= 3 ,-1,0
  3918.7     .13       0    4986    .045       0    5014     .13       0
Bank Sta=4986,5014
XS Rating Curve= 0 ,0
Exp/Cntr=0.3,0.1

Type RM Length L Ch R = 1 ,101461  ,532,532,532
BEGIN DESCRIPTION:
Indian Field Swamp 203.0
END DESCRIPTION:
XS GIS Cut Line= 3
      2122632.03       521332.37      2121806.94       520584.34
      2120776.59       519647.32
#Sta/Elev= 30
  3886.3   99.64  4226.3   97.14  4256.3   96.22  4356.3   95.14  4606.3   96.14
  4726.3   94.57  4816.3   94.99  4846.3   93.33  4896.3   93.86  4966.3   93.33
    4986   90.77  4987.5   87.77  5012.5   87.77    5014   90.77    5040   94.03
    5120   92.77    5180   93.27    5280   95.79    5410   94.56    5450   95.13
    5570   95.04    5660   96.77    5730   95.47    5760   96.83    5800   95.88
    5820   96.94    5880   97.22    6010    99.3    6210   99.28  6392.7  100.52
#Mann= 3 ,-1,0
  3886.3     .11       0    4986    .045       0    5014     .11       0
Bank Sta=4986,5014
XS Rating Curve= 0 ,0
Exp/Cntr=0.3,0.1

Type RM Length L Ch R = 1 ,100929  ,468,468,468
BEGIN DESCRIPTION:
Indian Field Swamp 202.0
END DESCRIPTION:
XS GIS Cut Line= 3
      2123164.41       520942.36      2122158.37       520215.57
      2121083.28       519442.82
#Sta/Elev= 30
  3763.8   98.32  3893.8   96.89  3923.8   97.43  4003.8   96.54  4123.8   97.92
  4543.8   95.75  4633.8   94.03  4813.8   92.47  4963.8   92.55  4983.8   92.26
    4986    90.2  4987.5    87.2  5012.5    87.2    5014    90.2  5014.9    93.2
  5144.9    92.2  5164.9   94.05  5204.9   94.61  5264.9   93.71  5404.9   95.56
  5574.9   95.06  5674.9   96.33  5704.9   94.75  5744.9   96.29  5814.9    95.3
  5884.9   97.18  5944.9   96.51  6034.9   97.77  6084.9   96.63  6328.9   99.49
#Mann= 3 ,-1,0
  3763.8     .11       0    4986    .045       0    5014     .11       0
Bank Sta=4986,5014
XS Rating Curve= 0 ,0
Exp/Cntr=0.3,0.1

Type RM Length L Ch R = 1 ,100461  ,500,500,500
BEGIN DESCRIPTION:
Indian Field Swamp 201.0
END DESCRIPTION:
XS GIS Cut Line= 3
      2123350.55       520559.26      2122540.49       519957.01
       2121363.6       519109.32
#Sta/Elev= 30
  3990.6   99.35  4010.6   97.91  4030.6   99.77  4060.6    97.5  4590.6   95.11
  4760.6   95.45  4830.6   94.37  4840.6   93.18  4930.6   92.99  4940.6   91.71
  4980.6   92.24    4986   89.71  4987.5   86.71  5012.5   86.71    5014   89.71
    5030    92.3    5050   93.02    5140   91.77    5220   96.05    5340   94.06
    5610   94.49    6040   96.79    6070   95.97    6080   96.95    6130   96.46
    6170   98.78    6220   96.19    6270   98.04    6350   98.82  6450.4   98.26
#Mann= 3 ,-1,0
  3990.6     .11       0    4986    .045       0    5014     .11       0
Bank Sta=4986,5014
XS Rating Curve= 0 ,0
Exp/Cntr=0.3,0.1

Type RM Length L Ch R = 1 ,99961   ,500,500,500
BEGIN DESCRIPTION:
Indian Field Swamp 200.0
END DESCRIPTION:
XS GIS Cut Line= 3
      2123615.49       520219.15      2122950.91       519674.43
      2121639.24       518665.36
#Sta/Elev= 30
  4140.7   99.61  4400.7   96.25  4460.7   94.21  4690.7   94.58  4800.7   93.82
  4870.7   95.13  4900.7   93.98  4920.7   91.49  4980.7   91.51    4986   89.34
  4987.5   86.34  5012.5   86.34    5014   89.34    5030   92.21    5070   91.34
    5140   92.99    5170   91.66    5300   91.86    5420   95.34    5490   95.46
    5500    93.5    5510   94.66    5710   93.98    5770   95.18    5790   97.36
    5810   97.41    5840   95.62    5930   94.41    6210    96.3  6654.9   97.15
#Mann= 3 ,-1,0
  4140.7     .14       0    4986    .045       0    5014     .14       0
Bank Sta=4986,5014
XS Rating Curve= 0 ,0
Exp/Cntr=0.3,0.1

Type RM Length L Ch R = 1 ,99461   ,500,500,500
BEGIN DESCRIPTION:
Indian Field Swamp 199.0
END DESCRIPTION:
XS GIS Cut Line= 3
      2124148.94       519632.01       2123042.8       519198.38
      2121667.86       518633.13
#Sta/Elev= 30
  3811.9   96.29  3911.9   98.02  4221.9   95.55  4281.9   96.05  4341.9   95.31
  4431.9   92.28  4521.9   91.89  4571.9   94.55  4651.9   95.61  4751.9   94.22
  4781.9   92.64  4981.9   91.56  4985.8   88.86  4987.3   85.86  5012.7   85.86
  5014.2   88.86    5070   91.81    5120   90.86    5160   91.84    5200    94.5
    5230   95.25    5380   95.11    5400   93.32    5540   94.89    5630   93.93
    6050   96.44    6240   95.77    6290   96.93    6340   96.04  6486.6   97.22
#Mann= 3 ,-1,0
  3811.9     .14       0  4985.8    .045       0  5014.2     .14       0
Bank Sta=4985.8,5014.2
XS Rating Curve= 0 ,0
Exp/Cntr=0.3,0.1

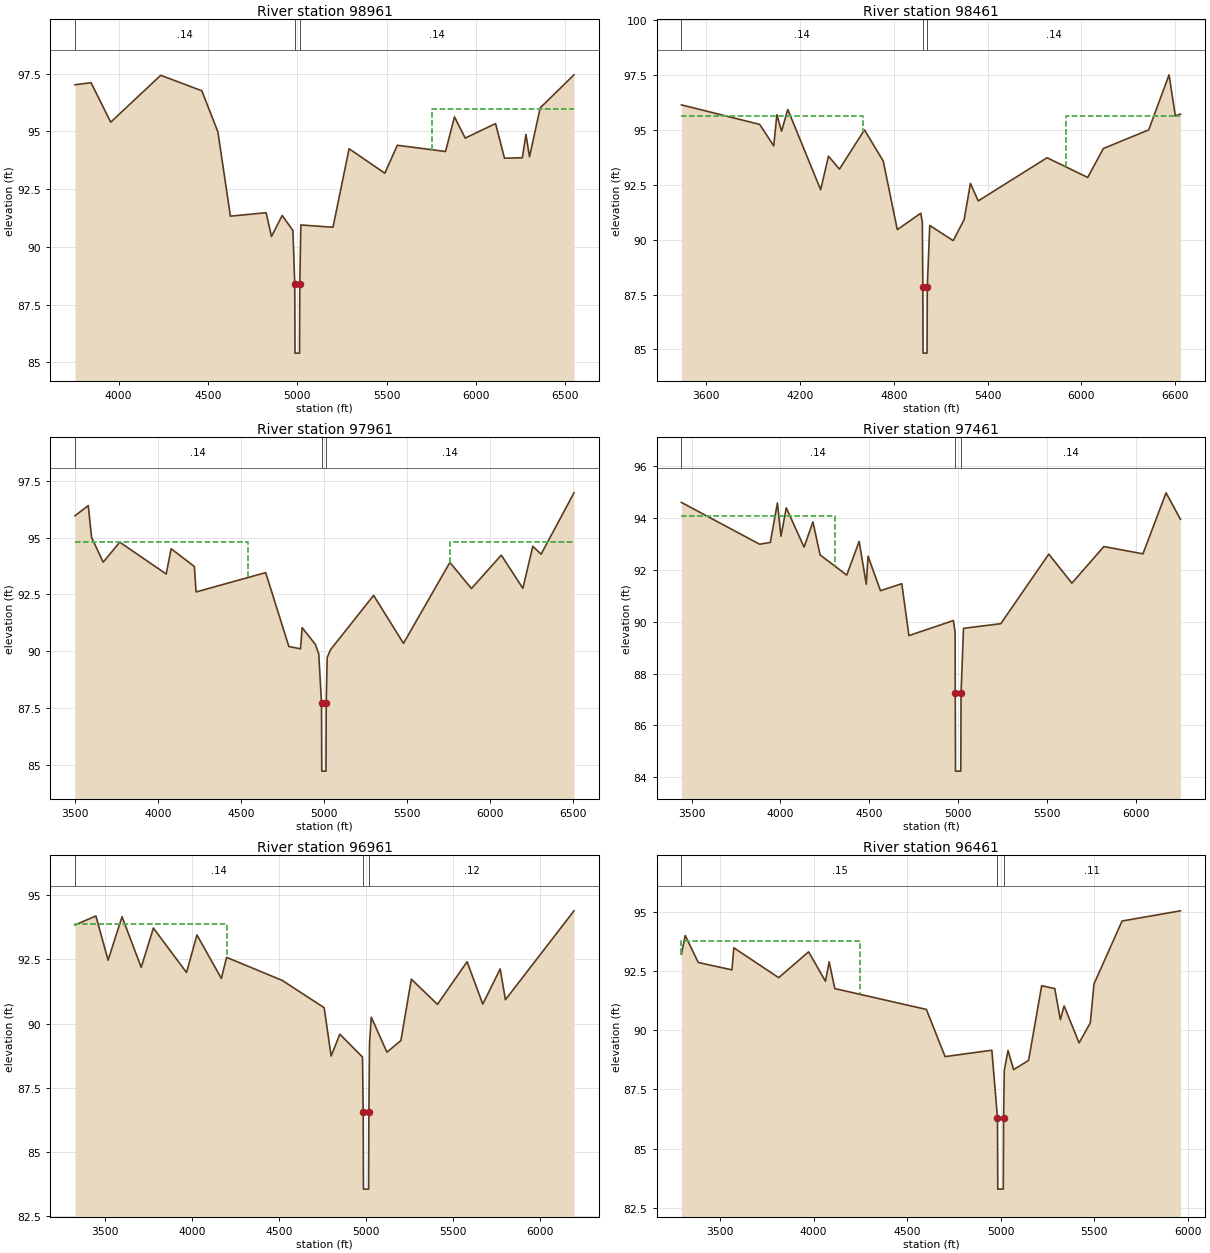
Type RM Length L Ch R = 1 ,98961   ,500,500,500
BEGIN DESCRIPTION:
Indian Field Swamp 198.0
END DESCRIPTION:
XS GIS Cut Line= 3
      2124199.09       519549.69      2123215.47       518787.45
      2121936.41       517913.54
#Sta/Elev= 30
  3755.6   97.02  3845.6   97.11  3955.6    95.4  4235.6   97.43  4465.6   96.76
  4555.6   94.98  4625.6   91.33  4825.6   91.48  4855.6   90.45  4915.6   91.36
  4975.6   90.71  4985.8    88.4  4987.3    85.4  5012.7    85.4  5014.2    88.4
    5020   90.95    5200   90.85    5290   94.25    5490   93.19    5560    94.4
    5830   94.13    5880   95.63    5940   94.71    6110   95.34    6160   93.84
    6260   93.86    6280   94.87    6300    93.9    6360   96.02  6549.1   97.45
#Mann= 3 ,-1,0
  3755.6     .14       0  4985.8    .045       0  5014.2     .14       0
#XS Ineff= 2 , 0
       0                  5753.6       0   95.98
Permanent Ineff=
       F       F
Bank Sta=4985.8,5014.2
XS Rating Curve= 0 ,0
Exp/Cntr=0.3,0.1

Type RM Length L Ch R = 1 ,98461   ,500,500,500
BEGIN DESCRIPTION:
Indian Field Swamp 197.0
END DESCRIPTION:
XS GIS Cut Line= 3
      2124732.52       519338.45      2123466.98       518430.75
      2122104.68       517530.47
#Sta/Elev= 30
  3442.6   96.15  3942.6   95.26  4032.6   94.28  4052.6    95.7  4082.6   94.95
  4122.6   95.94  4332.6   92.28  4382.6   93.81  4452.6   93.22  4612.6   95.01
  4732.6   93.59  4822.6   90.46  4972.6   91.21  4982.6   90.79  4985.8   87.83
  4987.3   84.83  5012.7   84.83  5014.2   87.83    5030   90.65    5180   89.96
    5250   90.92    5290   92.57    5340   91.77    5780   93.74    6040   92.84
    6140   94.16    6430   95.01    6560   97.52    6600   95.65  6632.9   95.73
#Mann= 3 ,-1,0
  3442.6     .14       0  4985.8    .045       0  5014.2     .14       0
#XS Ineff= 2 , 0
       0  4605.4   95.62    5900       0   95.62
Permanent Ineff=
       F       F
Bank Sta=4985.8,5014.2
XS Rating Curve= 0 ,0
Exp/Cntr=0.3,0.1

Type RM Length L Ch R = 1 ,97961   ,500,500,500
BEGIN DESCRIPTION:
Indian Field Swamp 196.0
END DESCRIPTION:
XS GIS Cut Line= 3
      2124968.78       518790.66      2123692.18       518001.17
        2122409.       517208.25
#Sta/Elev= 30
    3499   95.96    3579   96.41    3599   95.01    3669   93.92    3769    94.8
    4049    93.4    4079   94.51    4219   93.73    4229   92.61    4649   93.46
    4789   90.21    4859   90.11    4869   91.04    4949    90.3    4969   89.89
  4985.8   87.73  4987.3   84.73  5012.7   84.73  5014.2   87.73    5020   89.73
    5040   90.07    5300   92.46    5480   90.35    5760   93.91    5890   92.76
    6070   94.23    6200   92.77    6260   94.62    6310   94.27  6508.4   96.97
#Mann= 3 ,-1,0
    3499     .14       0  4985.8    .045       0  5014.2     .14       0
#XS Ineff= 2 , 0
       0  4544.9   94.82  5759.3       0   94.82
Permanent Ineff=
       F       F
Bank Sta=4985.8,5014.2
XS Rating Curve= 0 ,0
Exp/Cntr=0.3,0.1

Type RM Length L Ch R = 1 ,97461   ,500,500,500
BEGIN DESCRIPTION:
Indian Field Swamp 195.0
END DESCRIPTION:
XS GIS Cut Line= 3
      2125262.39       518160.58      2123838.57       517530.24
      2122802.77       516828.73
#Sta/Elev= 30
  3442.9   94.59  3882.9   92.98  3942.9   93.05  3982.9   94.57  4002.9   93.29
  4032.9   94.38  4132.9   92.87  4182.9   93.84  4222.9   92.57  4372.9   91.79
  4442.9   93.09  4482.9   91.44  4492.9   92.52  4562.9   91.19  4682.9   91.46
  4722.9   89.46  4972.9   90.04  4982.9    89.6  4983.7   87.24  4985.2   84.24
  5014.8   84.24  5016.3   87.24    5030   89.74    5240   89.92    5510    92.6
    5640   91.48    5820   92.89    6040   92.61    6170   94.96    6251   93.94
#Mann= 3 ,-1,0
  3442.9     .14       0  4983.7    .045       0  5016.3     .14       0
#XS Ineff= 2 , 0
       0  4304.2   94.07               0
Permanent Ineff=
       F       F
Bank Sta=4983.7,5016.3
XS Rating Curve= 0 ,0
Exp/Cntr=0.3,0.1

Type RM Length L Ch R = 1 ,96961   ,500,500,500
BEGIN DESCRIPTION:
Indian Field Swamp 194.0
END DESCRIPTION:
XS GIS Cut Line= 3
      2125598.94       517713.06      2124053.59       517079.18
      2123024.73       516474.29
#Sta/Elev= 30
  3329.7   93.84  3449.7   94.19  3519.7   92.47  3599.7   94.16  3709.7   92.19
  3779.7   93.72  3969.7   91.99  4029.7   93.45  4169.7   91.76  4199.7   92.58
  4519.7   91.68  4759.7   90.62  4799.7   88.74  4849.7   89.59  4979.7    88.7
  4983.7   86.56  4985.2   83.56  5014.8   83.56  5016.3   86.56    5020   89.23
    5030   90.25    5120   88.89    5200   89.34    5260   91.73    5410   90.75
    5580   92.41    5670   90.76    5770   92.13    5800   90.93  6193.5   94.39
#Mann= 3 ,-1,0
  3329.7     .14       0  4983.7    .045       0  5016.3     .12       0
#XS Ineff= 2 , 0
       0    4200   93.87               0
Permanent Ineff=
       F       F
Bank Sta=4983.7,5016.3
XS Rating Curve= 0 ,0
Exp/Cntr=0.3,0.1

Type RM Length L Ch R = 1 ,96461   ,500,500,500
BEGIN DESCRIPTION:
Indian Field Swamp 193.0
END DESCRIPTION:
XS GIS Cut Line= 3
      2125659.76       517659.34      2124286.52       516646.25
      2123608.99       515962.89
#Sta/Elev= 30
  3293.5    93.2  3313.5   93.99  3383.5   92.85  3563.5   92.54  3573.5   93.47
  3813.5   92.21  3973.5    93.3  4063.5   92.06  4083.5   92.88  4113.5   91.75
  4603.5   90.87  4703.5   88.88  4953.5   89.15  4983.7   86.29  4985.2   83.29
  5014.8   83.29  5016.3   86.29    5020   88.29    5040   89.14    5070   88.33
    5150   88.72    5220   91.87    5290   91.75    5320   90.44    5340   91.02
    5420   89.46    5480    90.3    5500   91.95    5650    94.6  5962.3   95.03
#Mann= 3 ,-1,0
  3293.5     .15       0  4983.7    .045       0  5016.3     .11       0
#XS Ineff= 2 , 0
       0    4250   93.75    5763       0   93.75
Permanent Ineff=
       F       F
Bank Sta=4983.7,5016.3
XS Rating Curve= 0 ,0
Exp/Cntr=0.3,0.1

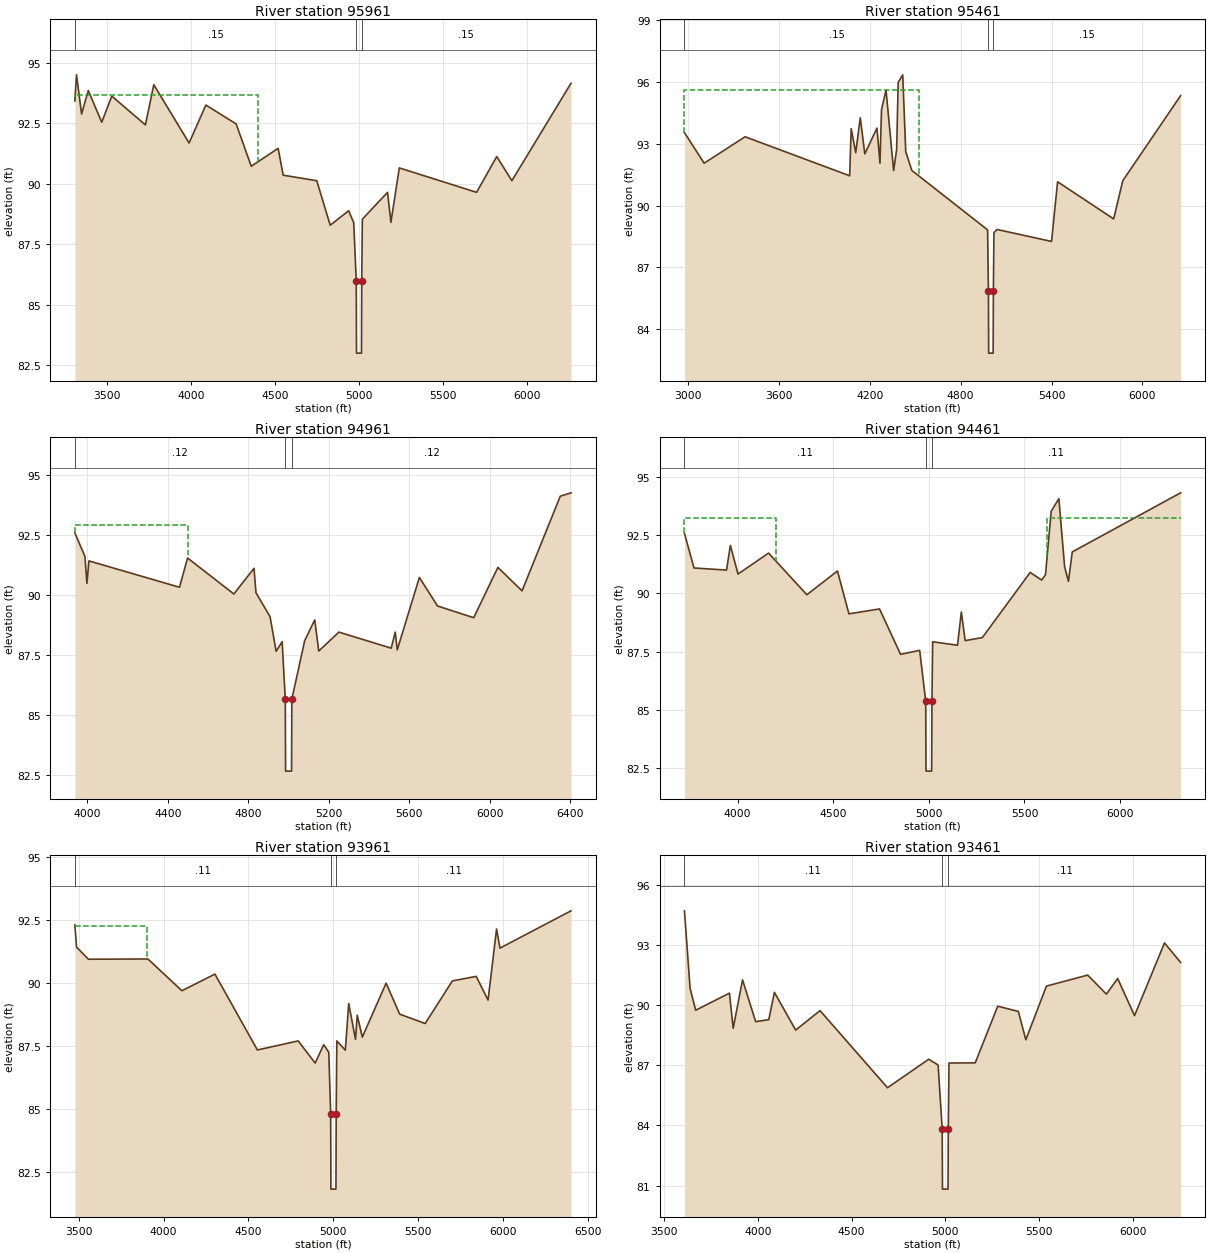
Type RM Length L Ch R = 1 ,95961   ,500,500,500
BEGIN DESCRIPTION:
Indian Field Swamp 192.0
END DESCRIPTION:
XS GIS Cut Line= 3
      2125740.89       517629.04      2124666.43       516322.88
      2123896.74        515322.9
#Sta/Elev= 30
  3308.7   93.42  3318.7    94.5  3348.7   92.88  3388.7   93.85  3468.7   92.54
  3528.7   93.62  3728.7   92.43  3778.7   94.09  3988.7   91.68  4088.7   93.25
  4268.7   92.47  4358.7   90.72  4518.7   91.46  4548.7   90.35  4748.7   90.12
  4828.7   88.28  4938.7   88.88  4968.7   88.38  4983.7   85.99  4985.2   82.99
  5014.8   82.99  5016.3   85.99    5020   88.53    5170   89.64    5190    88.4
    5240   90.65    5700   89.64    5820   91.12    5910   90.12  6261.9   94.15
#Mann= 3 ,-1,0
  3308.7     .15       0  4983.7    .045       0  5016.3     .15       0
#XS Ineff= 2 , 0
       0    4400   93.68               0
Permanent Ineff=
       F       F
Bank Sta=4983.7,5016.3
XS Rating Curve= 0 ,0
Exp/Cntr=0.3,0.1

Type RM Length L Ch R = 1 ,95461   ,500,500,500
BEGIN DESCRIPTION:
Indian Field Swamp 191.0
END DESCRIPTION:
XS GIS Cut Line= 3
      2126293.71       517738.81      2125111.45       516098.71
      2124325.03       515125.03
#Sta/Elev= 30
  2978.2   93.53  3108.2   92.05  3378.2   93.33  4068.2   91.44  4078.2   93.72
  4108.2   92.56  4138.2   94.25  4168.2    92.5  4248.2   93.75  4268.2   92.05
  4278.2   94.64  4308.2   95.59  4358.2   91.69  4378.2   92.71  4388.2   95.96
  4418.2   96.33  4438.2   92.61  4478.2    91.7  4978.2   88.82  4983.7   85.85
  4985.2   82.85  5014.8   82.85  5016.3   85.85    5020   88.68    5040   88.84
    5400   88.26    5440   91.15    5810   89.35    5870    91.2  6251.6   95.32
#Mann= 3 ,-1,0
  2978.2     .15       0  4983.7    .045       0  5016.3     .15       0
#XS Ineff= 2 , 0
       0  4526.8    95.6               0
Permanent Ineff=
       F       F
Bank Sta=4983.7,5016.3
XS Rating Curve= 0 ,0
Exp/Cntr=0.3,0.1

Type RM Length L Ch R = 1 ,94961   ,500,500,500
BEGIN DESCRIPTION:
Indian Field Swamp 190.0
END DESCRIPTION:
XS GIS Cut Line= 3
      2126358.08       516515.73      2125535.89       515843.86
       2124449.6       514955.62
#Sta/Elev= 30
  3938.2   92.59  3988.2   91.61  3998.2   90.48  4008.2   91.42  4458.2   90.32
  4498.2   91.54  4728.2   90.04  4828.2   91.11  4838.2   90.09  4908.2   89.09
  4938.2   87.65  4968.2   88.05  4983.7   85.65  4985.2   82.65  5014.8   82.65
  5016.3   85.65    5080   88.09    5130   88.96    5150   87.66    5250   88.45
    5510   87.78    5530   88.45    5540   87.71    5650   90.73    5740   89.54
    5920   89.05    6040   91.15    6160   90.17    6350   94.12  6403.2   94.26
#Mann= 3 ,-1,0
  3938.2     .12       0  4983.7    .045       0  5016.3     .12       0
#XS Ineff= 2 , 0
       0  4498.4   92.93               0
Permanent Ineff=
       F       F
Bank Sta=4983.7,5016.3
XS Rating Curve= 0 ,0
Exp/Cntr=0.3,0.1

Type RM Length L Ch R = 1 ,94461   ,500,500,500
BEGIN DESCRIPTION:
Indian Field Swamp 189.0
END DESCRIPTION:
XS GIS Cut Line= 3
      2126702.64       516269.57      2125756.97       515410.22
      2124608.68       514766.32
#Sta/Elev= 30
  3722.2   92.58  3772.2   91.09  3942.2      91  3962.2   92.06  4002.2   90.83
  4162.2   91.73  4362.2   89.94  4522.2   90.96  4582.2   89.12  4742.2   89.33
  4852.2   87.38  4952.2   87.55  4983.7   85.36  4985.2   82.36  5014.8   82.36
  5016.3   85.36    5020   87.92    5150   87.77    5170    89.2    5190   87.97
    5280    88.1    5530    90.9    5590   90.57    5610    90.8    5640   93.53
    5680   94.07    5710   91.14    5730   90.52    5750   91.78  6316.5   94.32
#Mann= 3 ,-1,0
  3722.2     .11       0  4983.7    .045       0  5016.3     .11       0
#XS Ineff= 2 , 0
       0    4200   93.22    5619       0   93.22
Permanent Ineff=
       F       F
Bank Sta=4983.7,5016.3
XS Rating Curve= 0 ,0
Exp/Cntr=0.3,0.1

Type RM Length L Ch R = 1 ,93961   ,500,500,500
BEGIN DESCRIPTION:
Indian Field Swamp 188.0
END DESCRIPTION:
XS GIS Cut Line= 4
      2126732.97       516280.98       2126512.4        515486.7
      2126019.51       514993.38      2124694.77       514546.74
#Sta/Elev= 30
  3478.3   92.32  3488.3   91.44  3558.3   90.96  3908.3   90.97  4108.3   89.71
  4302.6   90.37  4552.6   87.36  4792.6   87.72  4892.6   86.84  4942.6   87.57
  4972.6   87.27  4983.7   84.84  4985.2   81.84  5014.8   81.84  5016.3   84.84
    5020   87.72    5070   87.35    5090    89.2    5130   87.78    5140   88.74
    5170   87.87    5310   90.01    5390   88.78    5540   88.41    5700    90.1
    5840   90.28    5910   89.34    5960   92.16    5980    91.4    6398   92.88
#Mann= 3 ,-1,0
  3478.3     .11       0  4983.7    .045       0  5016.3     .11       0
#XS Ineff= 2 , 0
       0  3905.4   92.29               0
Permanent Ineff=
       F       F
Bank Sta=4983.7,5016.3
XS Rating Curve= 0 ,0
Exp/Cntr=0.3,0.1

Type RM Length L Ch R = 1 ,93461   ,500,500,500
BEGIN DESCRIPTION:
Indian Field Swamp 187.0
END DESCRIPTION:
XS GIS Cut Line= 4
      2127355.53       515255.81      2126913.74       514922.41
       2126159.8        514556.3      2124972.39       514147.22
#Sta/Elev= 30
  3608.4   94.69  3638.4   90.83  3668.4   89.74  3848.4   90.59  3868.4   88.84
  3918.4   91.25  3988.4   89.17  4058.4   89.27  4088.4   90.63  4201.9   88.75
  4331.9   89.72  4691.9   85.88  4911.9    87.3  4961.9   87.01  4983.7   83.83
  4985.2   80.83  5014.8   80.83  5016.3   83.83    5020   87.11    5160   87.12
    5280   89.94    5390   89.68    5430   88.27    5540   90.94    5760   91.49
    5860   90.54    5920   91.32    6010   89.47    6170   93.09  6255.9   92.12
#Mann= 3 ,-1,0
  3608.4     .11       0  4983.7    .045       0  5016.3     .11       0
Bank Sta=4983.7,5016.3
XS Rating Curve= 0 ,0
Exp/Cntr=0.3,0.1

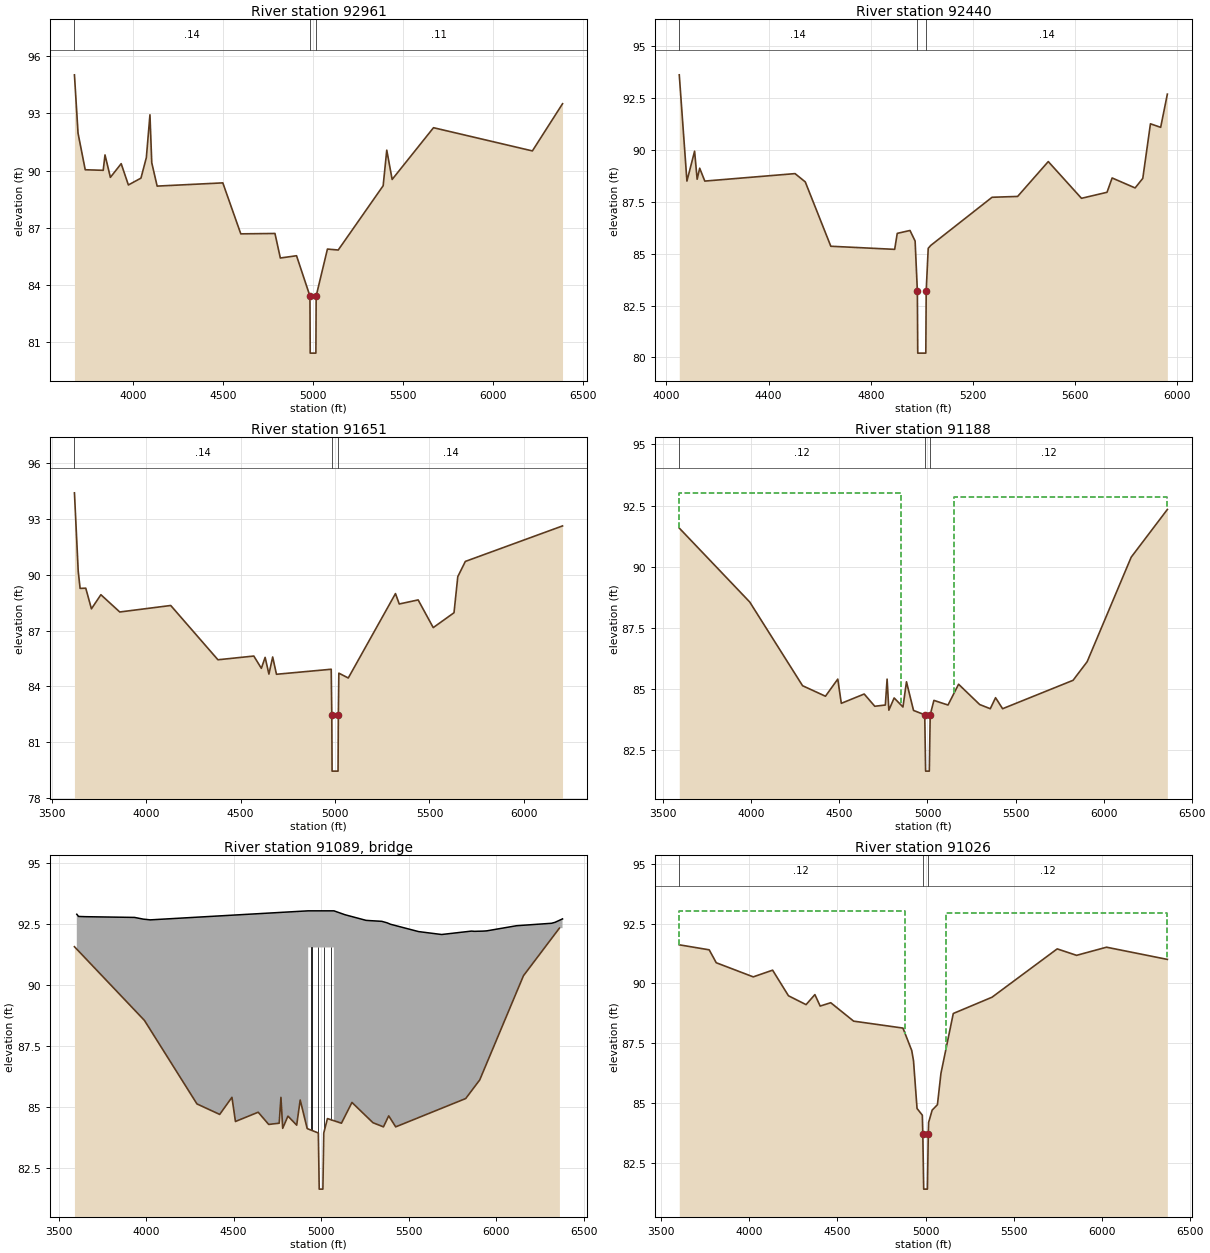
Type RM Length L Ch R = 1 ,92961   ,521,521,521
BEGIN DESCRIPTION:
Indian Field Swamp 186.0
END DESCRIPTION:
XS GIS Cut Line= 4
      2127364.24       515252.34      2126985.12       514806.44
      2126504.85       514240.95      2125555.35       513228.95
#Sta/Elev= 30
  3672.8   95.03  3692.8   91.96  3732.8   90.04  3832.8   90.01  3842.8   90.82
  3872.8   89.64  3932.8   90.36  3972.8   89.24  4042.8    89.6  4072.8   90.68
  4092.8   92.93  4102.8   90.41  4132.8   89.18  4498.1   89.35  4598.1   86.67
  4788.1   86.69  4818.1    85.4  4908.1   85.52  4982.7    83.4  4984.2    80.4
  5015.8    80.4  5017.3    83.4    5080   85.87    5140   85.82    5390    89.2
    5410   91.07    5440   89.53    5670   92.25    6220   91.03  6387.7   93.51
#Mann= 3 ,-1,0
  3672.8     .14       0  4982.7    .045       0  5017.3     .11       0
Bank Sta=4982.7,5017.3
XS Rating Curve= 0 ,0
Exp/Cntr=0.3,0.1

Type RM Length L Ch R = 1 ,92440   ,789,789,789
BEGIN DESCRIPTION:
Indian Field Swamp 185.0
END DESCRIPTION:
XS GIS Cut Line= 4
      2127271.98       514778.85      2127213.87       514470.94
      2126895.79       513925.66      2126426.25       513081.25
#Sta/Elev= 30
  4050.6   93.62  4080.6    88.5  4110.6   89.94  4120.6   88.59  4130.6   89.12
  4150.6    88.5  4503.9   88.86  4543.9   88.46  4643.9   85.36  4893.9   85.21
  4903.9   85.98  4953.9   86.12  4973.9   85.61  4982.7   83.21  4984.2   80.21
  5015.8   80.21  5017.3   83.21  5025.2   85.26  5035.2    85.4  5275.2   87.72
  5375.2   87.76  5495.2   89.44  5625.2   87.67  5725.2   87.96  5745.2   88.65
  5835.2   88.17  5865.2   88.63  5895.2   91.26  5935.2   91.09  5961.4   92.69
#Mann= 3 ,-1,0
  4050.6     .14       0  4982.7    .045       0  5017.3     .14       0
Bank Sta=4982.7,5017.3
XS Rating Curve= 0 ,0
Exp/Cntr=0.3,0.1

Type RM Length L Ch R = 1 ,91651   ,463,463,463
BEGIN DESCRIPTION:
Indian Field Swamp 184.0
END DESCRIPTION:
XS GIS Cut Line= 3
      2127524.38       514792.81      2127448.64       513414.46
      2126979.09       512304.96
#Sta/Elev= 30
  3619.6   94.41  3639.6   90.19  3649.6   89.27  3679.6   89.28  3709.6   88.17
  3759.6   88.93  3859.6      88  4129.6   88.35  4379.6   85.43  4569.6   85.63
  4609.6   84.97  4629.6   85.56  4649.6   84.66  4669.6   85.58  4689.6   84.65
  4979.6   84.92  4982.7   82.44  4984.2   79.44  5015.8   79.44  5017.3   82.44
    5020   84.71    5070   84.45    5320   88.99    5340   88.43    5440   88.65
    5520   87.16    5630   87.96    5650    89.9    5690   90.72  6204.8   92.63
#Mann= 3 ,-1,0
  3619.6     .14       0  4982.7    .045       0  5017.3     .14       0
Bank Sta=4982.7,5017.3
XS Rating Curve= 0 ,0
Exp/Cntr=0.5,0.3

Type RM Length L Ch R = 1 ,91188   ,162,162,162
BEGIN DESCRIPTION:
I-95 South at Indian Field - US
END DESCRIPTION:
XS GIS Cut Line= 3
      2128357.03       514699.91      2127874.89       513379.34
       2127517.2       512061.66
#Sta/Elev= 30
  3590.8   91.58  3990.8   88.56  4290.8   85.14  4420.8   84.71  4490.8   85.41
  4510.8   84.42  4640.8    84.8  4700.8    84.3  4760.8   84.35  4770.8   85.41
  4780.8   84.14  4810.8   84.64  4860.8   84.27  4880.8    85.3  4920.8   84.13
  4984.5   83.95  4989.5   81.65  5010.5   81.65  5015.5   83.95  5036.6   84.54
  5116.6   84.35  5176.6    85.2  5296.6   84.37  5356.6    84.2  5386.6   84.65
  5426.6    84.2  5826.6   85.36  5906.6   86.12  6156.6   90.39    6362   92.34
#Mann= 3 ,-1,0
  3590.8     .12       0  4984.5    .045       0  5015.5     .12       0
#XS Ineff= 2 , 0
       0    4849   93.02    5151       0   92.86
Permanent Ineff=
       F       F
Bank Sta=4984.5,5015.5
XS Rating Curve= 0 ,0
Exp/Cntr=0.5,0.3

Type RM Length L Ch R = 3 ,91089   ,,,
BEGIN DESCRIPTION:
I-95 South at Indian Field - TOR
Structure ID: LDS_IFS_08
Approximate Survey Structure
END DESCRIPTION:
Bridge Culvert--1,0,-1,-1, 0
Deck Dist Width WeirC Skew NumUp NumDn MinLoCord MaxHiCord MaxSubmerge Is_Ogee
77.5,43,3,0, 26, 26, , , 0.95, 0, 1,1,,
  3604.2  3614.2  3654.2  3934.2  3984.2  4024.2  4926.5  4926.5  5073.5  5073.5
  5136.9  5256.9  5276.9  5346.9  5376.9  5396.9  5556.9  5689.2  5859.2  5877.1
  5927.1  5947.1  6117.1  6317.1  6337.1  6379.9
   92.91   92.82   92.81   92.78   92.71   92.68   93.05   93.05   93.05   93.05
   92.89   92.66   92.65   92.62   92.56    92.5    92.2   92.08   92.22   92.21
   92.22   92.23   92.44   92.54   92.58   92.72
   61.65   61.65   61.65   61.65   61.65   61.65   61.65   91.55   91.55   61.65
   61.65   61.65   61.65   61.65   61.65   61.65   61.65   61.65   61.65   61.65
   61.65   61.65   61.65   61.65   61.65   61.65
  3604.2  3614.2  3654.2  3934.2  3984.2  4024.2  4926.5  4926.5  5073.5  5073.5
  5136.9  5256.9  5276.9  5346.9  5376.9  5396.9  5556.9  5689.2  5859.2  5877.1
  5927.1  5947.1  6117.1  6317.1  6337.1  6379.9
   92.91   92.82   92.81   92.78   92.71   92.68   93.05   93.05   93.05   93.05
   92.89   92.66   92.65   92.62   92.56    92.5    92.2   92.08   92.22   92.21
   92.22   92.23   92.44   92.54   92.58   92.72
   61.65   61.65   61.65   61.65   61.65   61.65   61.65   91.55   91.55   61.65
   61.65   61.65   61.65   61.65   61.65   61.65   61.65   61.65   61.65   61.65
   61.65   61.65   61.65   61.65   61.65   61.65
Pier Skew, UpSta & Num, DnSta & Num=  ,4944.9, 2 ,4944.9, 2 , 0 , 0 , 0 ,0,0
     1.5     1.5
   84.18   91.55
     1.5     1.5
   85.36   91.55
Pier Skew, UpSta & Num, DnSta & Num=  ,4981.6, 2 ,4981.6, 2 , 0 , 0 , 0 ,0,0
     1.5     1.5
   84.15   91.55
     1.5     1.5
   84.49   91.55
Pier Skew, UpSta & Num, DnSta & Num=  ,5018.4, 2 ,5018.4, 2 , 0 , 0 , 0 ,0,0
     1.5     1.5
   84.26   91.55
     1.5     1.5
   84.21   91.55
Pier Skew, UpSta & Num, DnSta & Num=  ,5055.1, 2 ,5055.1, 2 , 0 , 0 , 0 ,0,0
     1.5     1.5
   84.54   91.55
     1.5     1.5
   84.65   91.55
Abutment Skew #Up #Dn= , 2 , 2
  4926.5    4949
   91.55   84.19
  4926.5    4949
   91.55      85
Abutment Skew #Up #Dn= , 2 , 2
    5051  5073.5
   84.56   91.55
    5051  5073.5
   84.66   91.55
BR Coef= 1 , 1 , 0 ,1.25, 0 ,,,0.8,0,2,0,
WSPro=,,,, 1 ,,,, 0 ,,,, 0 ,,,,-1 ,-1 ,-1 , 0 , 0 , 0 , 0 , 0
BC Design=,, 0 ,, 0 ,,,,,,
BC HTab HWMax=92.49
BC Use User HTab Curves=0
BC User HTab FreeFlow(D)= 0

Type RM Length L Ch R = 1 ,91026   ,14,14,14
BEGIN DESCRIPTION:
I-95 South at Indian Field - DS
END DESCRIPTION:
XS GIS Cut Line= 3
       2128415.6       514681.87        2128028.       513340.95
      2127566.56       512045.28
#Sta/Elev= 30
  3601.7   91.61  3771.7    91.4  3811.7   90.86  4021.7   90.27  4131.7   90.55
  4221.7   89.48  4321.7   89.11  4371.7   89.53  4401.7   89.05  4461.7   89.19
  4591.7   88.42  4871.7   88.13  4921.7   87.19  4931.7   86.76  4951.7   84.77
  4981.7   84.49  4984.5    83.7  4989.5    81.4  5010.5    81.4  5015.5    83.7
  5017.5   84.19  5037.5    84.7  5067.5   84.93  5087.5   86.24  5157.5   88.74
  5377.5   89.42  5747.5   91.44  5857.5   91.17  6027.5   91.51  6372.9      91
#Mann= 3 ,-1,0
  3601.7     .12       0  4984.5    .045       0  5015.5     .12       0
#XS Ineff= 2 , 0
       0    4885   93.03    5115       0   92.95
Permanent Ineff=
       F       F
Bank Sta=4984.5,5015.5
XS Rating Curve= 0 ,0
Exp/Cntr=0.5,0.3