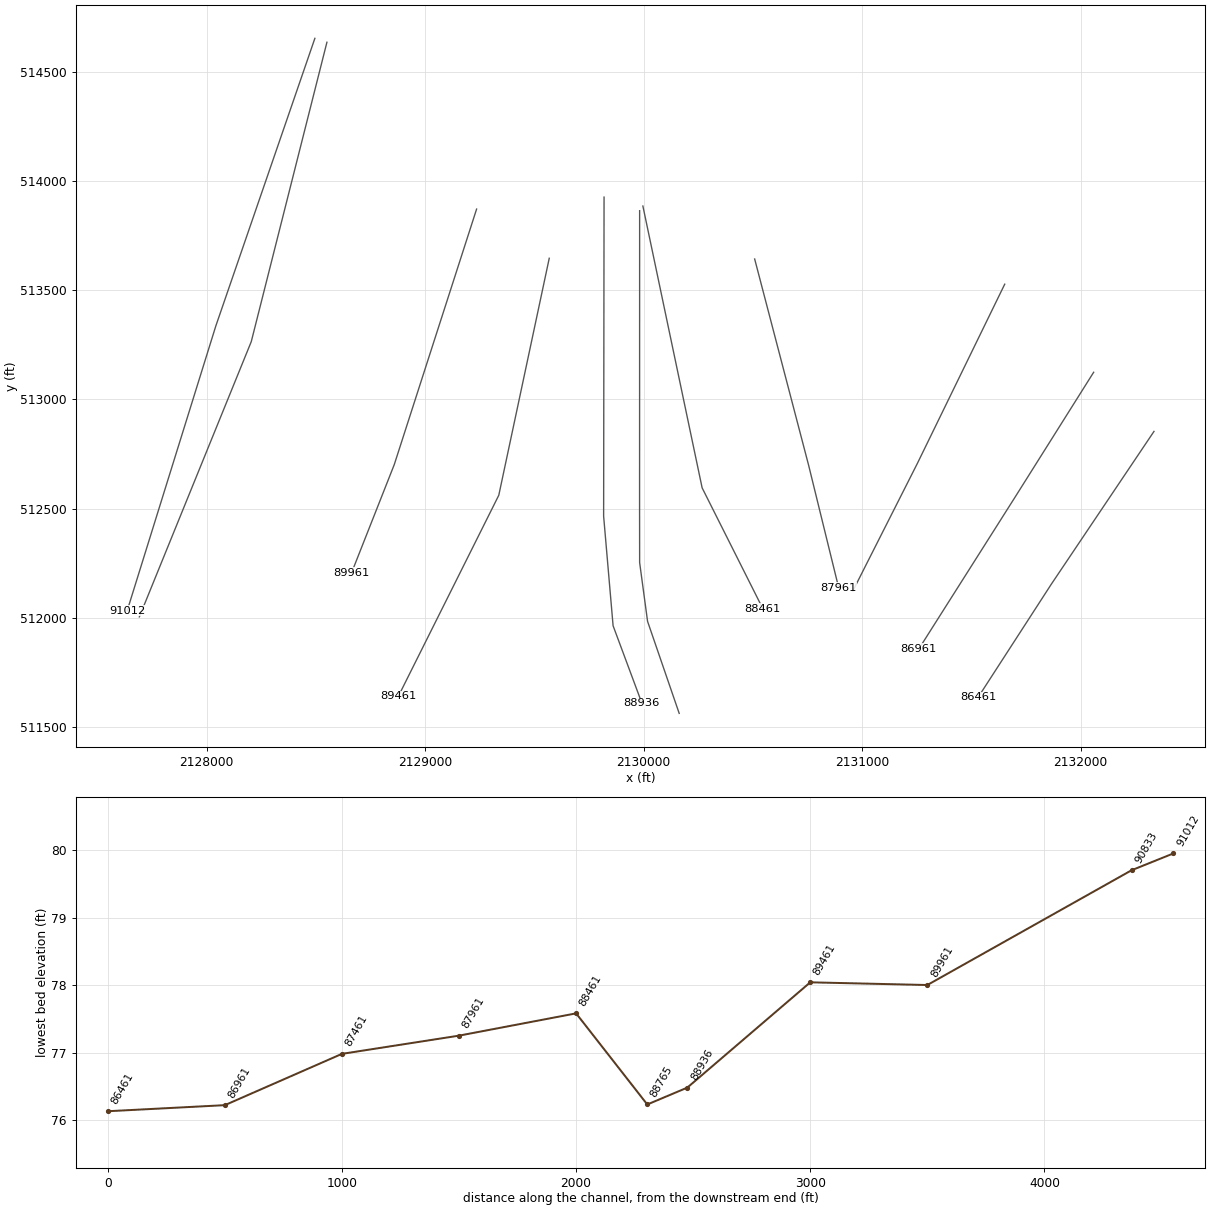
HEC-RAS study IndianFieldsSwamp.prj: S-18-19 over Indian Fields Swamp

--- IndianFieldsSwamp.g02 (geometry) --- (continued)

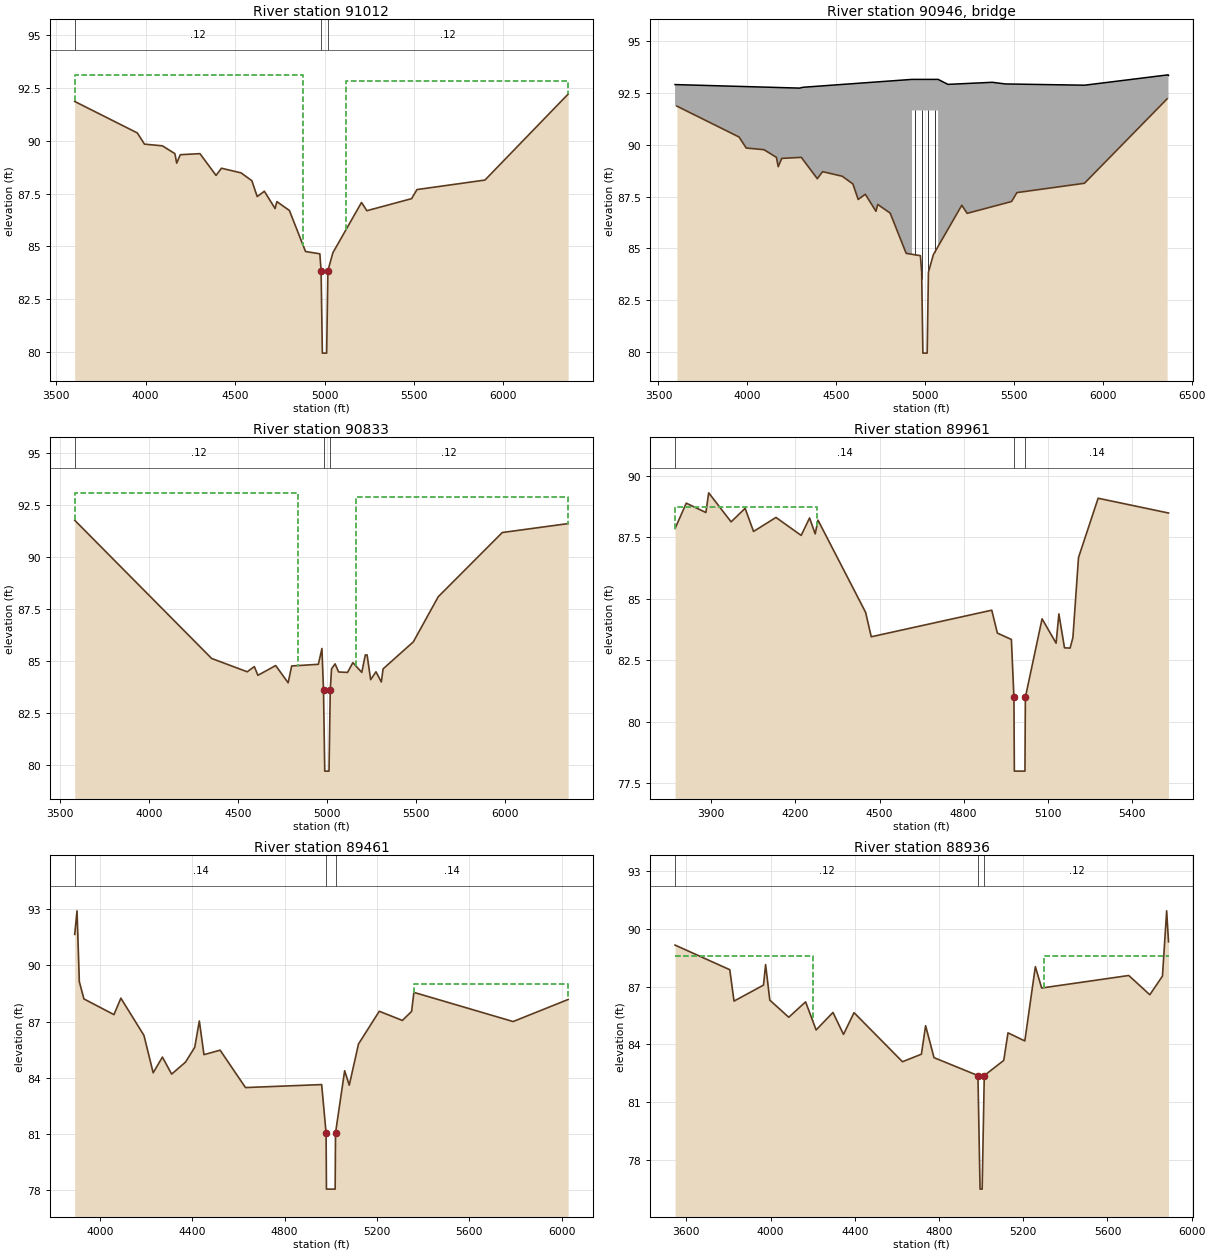
Type RM Length L Ch R = 1 ,91012   ,179,179,179
BEGIN DESCRIPTION:
I-95 North at Indian Field - US
END DESCRIPTION:
XS GIS Cut Line= 3
      2128495.22       514653.39       2128041.9       513336.32
      2127636.44       512032.93
#Sta/Elev= 30
  3603.9   91.86  3953.9   90.37  3993.9   89.84  4093.9   89.76  4163.9   89.39
  4173.9   88.94  4193.9   89.34  4303.9   89.39  4393.9   88.36  4423.9    88.7
  4533.9   88.48  4593.9   88.11  4623.9   87.36  4663.9   87.61  4723.9   86.79
  4733.9   87.12  4803.9    86.7  4893.9   84.76  4973.9   84.65    4981   83.85
    4988   79.95    5012   79.95    5019   83.85  5046.8    84.7  5206.8   87.08
  5236.8   86.69  5486.8   87.26  5516.8   87.69  5896.8   88.14  6361.8   92.21
#Mann= 3 ,-1,0
  3603.9     .12       0    4981    .045       0    5019     .12       0
#XS Ineff= 2 , 0
       0    4882   93.12    5118       0   92.83
Permanent Ineff=
       F       F
Bank Sta=4981,5019
XS Rating Curve= 0 ,0
Exp/Cntr=0.5,0.3

Type RM Length L Ch R = 3 ,90946   ,,,
BEGIN DESCRIPTION:
I-95 North at Indian Field - TOR
Structure ID: LDS_IFS_07
Approximate Survey Structure
END DESCRIPTION:
Bridge Culvert--1,0,-1,-1, 0
Deck Dist Width WeirC Skew NumUp NumDn MinLoCord MaxHiCord MaxSubmerge Is_Ogee
44.5,43,3,0, 13, 13, , , 0.95, 0, 1,1,,
  3593.6  4293.6  4313.6  4926.5  4926.5  5073.5  5073.5  5128.8  5378.8  5451.9
  5897.9  6367.9  6369.7
    92.9   92.73   92.77   93.15   93.15   93.15   93.15   92.91   93.01   92.93
   92.87   93.37   93.34
   59.95   59.95   59.95   59.95   91.65   91.65   59.95   59.95   59.95   59.95
   59.95   59.95   59.95
  3593.6  4293.6  4313.6  4926.5  4926.5  5073.5  5073.5  5128.8  5378.8  5451.9
  5897.9  6367.9  6369.7
    92.9   92.73   92.77   93.15   93.15   93.15   93.15   92.91   93.01   92.93
   92.87   93.37   93.34
   59.95   59.95   59.95   59.95   91.65   91.65   59.95   59.95   59.95   59.95
   59.95   59.95   59.95
Pier Skew, UpSta & Num, DnSta & Num=  ,4944.9, 2 ,4944.9, 2 , 0 , 0 , 0 ,0,0
     1.5     1.5
   84.72   91.65
     1.5     1.5
   84.86   91.65
Pier Skew, UpSta & Num, DnSta & Num=  ,4981.6, 2 ,4981.6, 2 , 0 , 0 , 0 ,0,0
     1.5     1.5
   83.52   91.65
     1.5     1.5
   83.27   91.65
Pier Skew, UpSta & Num, DnSta & Num=  ,5018.4, 2 ,5018.4, 2 , 0 , 0 , 0 ,0,0
     1.5     1.5
   83.52   91.65
     1.5     1.5
   83.27   91.65
Pier Skew, UpSta & Num, DnSta & Num=  ,5055.1, 2 ,5055.1, 2 , 0 , 0 , 0 ,0,0
     1.5     1.5
   84.67   91.65
     1.5     1.5
   84.68   91.65
Abutment Skew #Up #Dn= , 2 , 2
  4926.5    4949
   91.65   84.71
  4926.5    4949
   91.65   84.85
Abutment Skew #Up #Dn= , 2 , 2
    5051  5073.5
   84.68   91.65
    5051  5073.5
   84.76   91.65
BR Coef= 1 , 1 , 0 ,1.25, 0 ,,,0.8,0,2,0,
WSPro=,,,, 1 ,,,, 0 ,,,, 0 ,,,,-1 ,-1 ,-1 , 0 , 0 , 0 , 0 , 0
BC Design=,, 0 ,, 0 ,,,,,,
BC HTab HWMax=92.21
BC Use User HTab Curves=0
BC User HTab FreeFlow(D)= 0

Type RM Length L Ch R = 1 ,90833   ,872,872,872
BEGIN DESCRIPTION:
I-95 North at Indian Field - DS
END DESCRIPTION:
XS GIS Cut Line= 3
      2128550.35       514635.49      2128204.09       513264.49
      2127691.94       512004.13
#Sta/Elev= 30
  3582.1   91.77  4352.1   85.12  4552.1   84.48  4592.1   84.73  4612.1   84.31
  4712.1   84.78  4782.1   83.95  4802.1   84.76  4952.1   84.84  4972.1    85.6
    4981    83.6    4988    79.7    5012    79.7    5019    83.6  5026.1   84.62
  5046.1   84.86  5066.1   84.47  5116.1   84.45  5146.1   84.92  5196.1   84.45
  5216.1   85.29  5226.1   85.29  5246.1    84.1  5276.1   84.48  5306.1   83.99
  5316.1   84.62  5486.1   85.92  5626.1   88.09  5986.1   91.18  6356.6   91.61
#Mann= 3 ,-1,0
  3582.1     .12       0    4981    .045       0    5019     .12       0
#XS Ineff= 2 , 0
       0    4835   93.09    5165       0   92.91
Permanent Ineff=
       F       F
Bank Sta=4981,5019
XS Rating Curve= 0 ,0
Exp/Cntr=0.5,0.3

Type RM Length L Ch R = 1 ,89961   ,500,500,500
BEGIN DESCRIPTION:
Indian Field Swamp 180.0
END DESCRIPTION:
XS GIS Cut Line= 3
      2129235.31       513871.49      2128858.43       512701.18
       2128663.6       512207.11
#Sta/Elev= 30
  3770.5   87.86  3810.5   88.89  3880.5   88.51  3890.5   89.31  3970.5   88.13
  4020.5   88.68  4050.5   87.74  4130.5   88.31  4220.5   87.58  4250.5   88.29
  4270.5   87.64  4280.5    88.2  4450.5   84.45  4470.5   83.46  4900.5   84.54
  4920.5   83.61  4970.5   83.35  4979.6      81  4981.1      78  5018.9      78
  5020.4      81    5080   84.19    5130    83.2    5140   84.39    5160   83.01
    5180      83    5190   83.43    5210   86.68    5280   89.09  5531.1   88.49
#Mann= 3 ,-1,0
  3770.5     .14       0  4979.6    .045       0  5020.4     .14       0
#XS Ineff= 2 , 0
       0  4275.9   88.74               0
Permanent Ineff=
       F       F
Bank Sta=4979.6,5020.4
XS Rating Curve= 0 ,0
Exp/Cntr=0.3,0.1

Type RM Length L Ch R = 1 ,89461   ,525,525,525
BEGIN DESCRIPTION:
Indian Field Swamp 179.0
END DESCRIPTION:
XS GIS Cut Line= 3
      2129567.79       513646.27      2129336.85       512560.97
      2128877.51       511640.86
#Sta/Elev= 30
  3890.4   91.66  3900.4   92.92  3910.4   89.13  3930.4   88.21  4060.4   87.37
  4090.4   88.25  4190.4   86.26  4230.4   84.26  4270.4    85.1  4310.4   84.19
  4370.4   84.83  4410.4   85.62  4430.4   87.03  4450.4   85.23  4520.4   85.47
  4630.4   83.47  4960.4   83.63  4979.6   81.04  4981.1   78.04  5018.9   78.04
  5020.4   81.04    5060   84.37    5080    83.6    5120    85.8    5210   87.55
    5310   87.06    5350   87.54    5360   88.56    5790      87  6028.4   88.18
#Mann= 3 ,-1,0
  3890.4     .14       0  4979.6    .045       0  5020.4     .14       0
#XS Ineff= 2 , 0
       0                    5362       0   88.99
Permanent Ineff=
       F       F
Bank Sta=4979.6,5020.4
XS Rating Curve= 0 ,0
Exp/Cntr=0.5,0.3

Type RM Length L Ch R = 1 ,88936   ,171,171,171
BEGIN DESCRIPTION:
Mullberry Road at Indian Fields - US
END DESCRIPTION:
XS GIS Cut Line= 4
      2129818.62       513926.35      2129816.66       512465.16
      2129859.98       511963.32      2129991.91       511608.34
#Sta/Elev= 30
  3546.4   89.16  3806.4   87.88  3826.4   86.25  3966.4   87.08  3976.4   88.15
  3996.4    86.3  4086.4   85.41  4166.4   86.21  4216.4   84.75  4296.4   85.66
  4346.4   84.52  4396.4   85.65  4626.4    83.1  4716.4   83.49  4736.4   84.97
  4776.4   83.31    4985   82.38    4995   76.48    5005   76.48    5015   82.38
  5107.6   83.17  5127.6    84.6  5207.6   84.18  5257.6   88.04  5287.6   86.93
  5701.3   87.58  5801.3   86.58  5861.3   87.55  5881.3   90.94    5890   89.33
#Mann= 3 ,-1,0
  3546.4     .12       0    4985    .045       0    5015     .12       0
#XS Ineff= 2 , 0
       0    4200   88.57    5300       0   88.57
Permanent Ineff=
       F       F
Bank Sta=4985,5015
XS Rating Curve= 0 ,0
Exp/Cntr=0.5,0.3

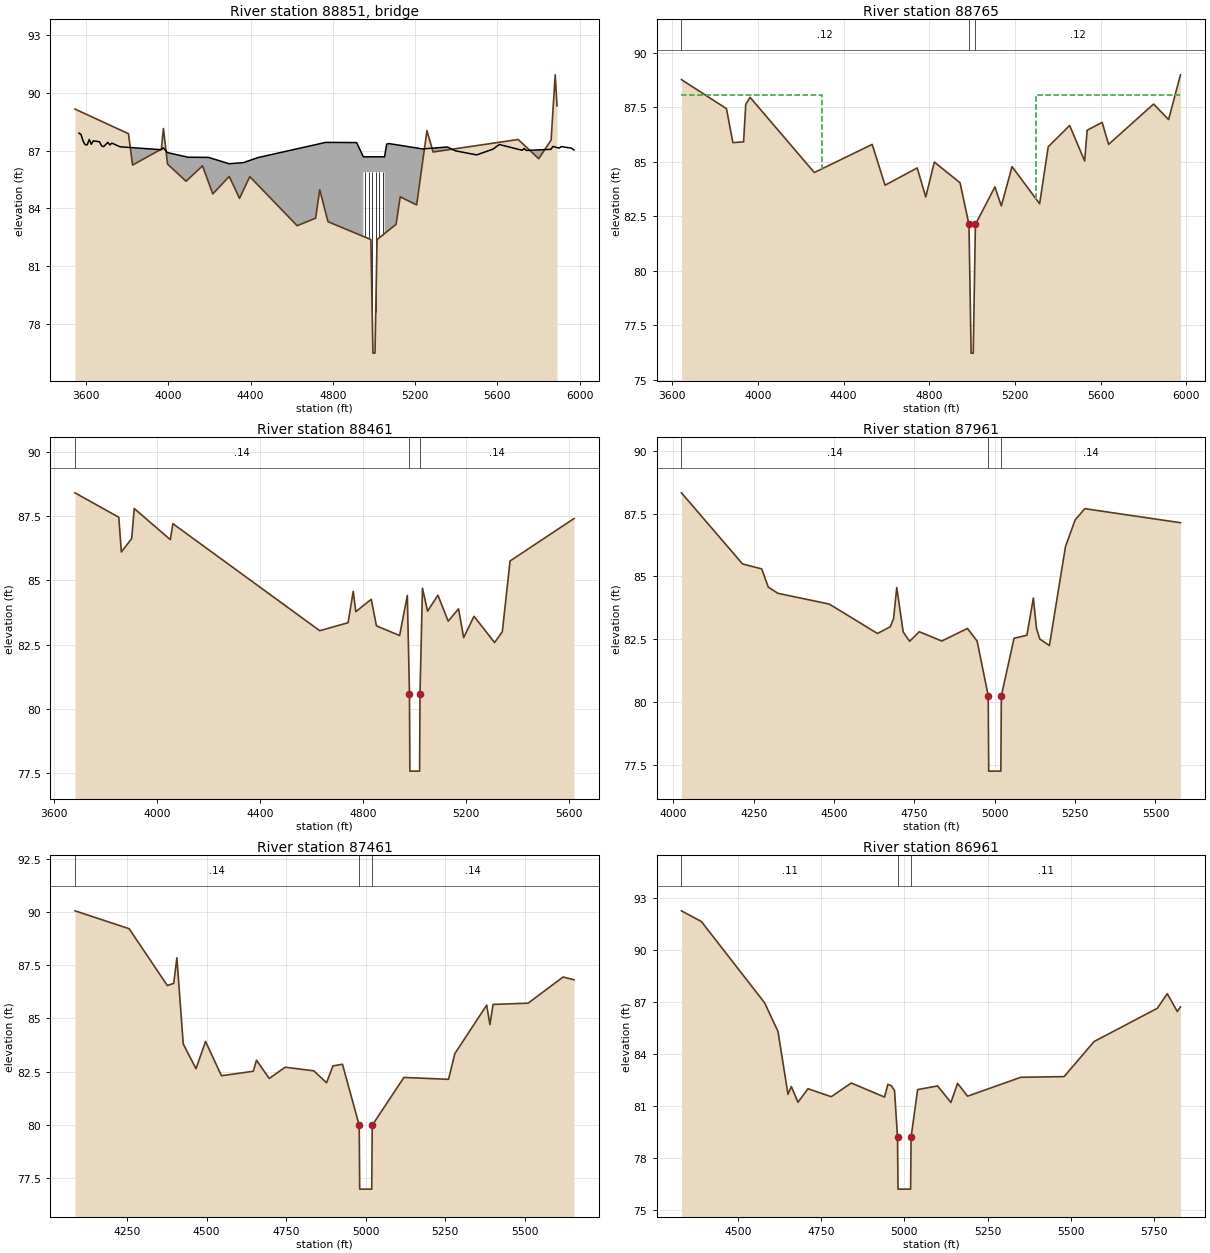
Type RM Length L Ch R = 3 ,88851   ,,,
BEGIN DESCRIPTION:
Mullberry Road at Indian Fields - TOR
Structure ID: LDS_IFS_06
Approximate Survey Structure
END DESCRIPTION:
Bridge Culvert--1,0,-1,-1, 0
Deck Dist Width WeirC Skew NumUp NumDn MinLoCord MaxHiCord MaxSubmerge Is_Ogee
70.5,29,3,0, 46, 46, , , 0.95, 0, 1,1,,
  3565.7  3575.7  3585.7  3595.7  3605.7  3615.7  3625.7  3635.7  3665.7  3675.7
  3685.7  3705.7  3715.7  3725.7  3765.7  3965.7  3975.7  3995.7  4095.7  4195.7
  4295.7  4365.7  4435.7  4765.7  4915.7  4948.5  4948.5  5051.5  5051.5  5061.8
  5071.8  5236.6  5356.6  5396.6  5499.2  5579.2  5609.2  5720.4  5730.4  5740.4
  5860.4  5870.4  5900.4  5910.4  5960.4  5972.6
   87.91   87.84    87.5   87.31    87.3   87.58   87.33   87.51   87.46   87.25
   87.21   87.43    87.3   87.39    87.2   87.05   87.15    86.9   86.66   86.65
   86.32   86.38   86.64   87.43   87.42   86.68   86.68   86.68   86.68   87.34
   87.37   87.09   87.19   86.99   86.78   87.08   87.32   87.02   87.11   87.01
   87.07   87.22   87.13   87.21   87.13   87.03
   56.48   56.48   56.48   56.48   56.48   56.48   56.48   56.48   56.48   56.48
   56.48   56.48   56.48   56.48   56.48   56.48   56.48   56.48   56.48   56.48
   56.48   56.48   56.48   56.48   56.48   56.48   85.88   85.88   56.48   56.48
   56.48   56.48   56.48   56.48   56.48   56.48   56.48   56.48   56.48   56.48
   56.48   56.48   56.48   56.48   56.48   56.48
  3565.7  3575.7  3585.7  3595.7  3605.7  3615.7  3625.7  3635.7  3665.7  3675.7
  3685.7  3705.7  3715.7  3725.7  3765.7  3965.7  3975.7  3995.7  4095.7  4195.7
  4295.7  4365.7  4435.7  4765.7  4915.7  4948.5  4948.5  5051.5  5051.5  5061.8
  5071.8  5236.6  5356.6  5396.6  5499.2  5579.2  5609.2  5720.4  5730.4  5740.4
  5860.4  5870.4  5900.4  5910.4  5960.4  5972.6
   87.91   87.84    87.5   87.31    87.3   87.58   87.33   87.51   87.46   87.25
   87.21   87.43    87.3   87.39    87.2   87.05   87.15    86.9   86.66   86.65
   86.32   86.38   86.64   87.43   87.42   86.68   86.68   86.68   86.68   87.34
   87.37   87.09   87.19   86.99   86.78   87.08   87.32   87.02   87.11   87.01
   87.07   87.22   87.13   87.21   87.13   87.03
   56.48   56.48   56.48   56.48   56.48   56.48   56.48   56.48   56.48   56.48
   56.48   56.48   56.48   56.48   56.48   56.48   56.48   56.48   56.48   56.48
   56.48   56.48   56.48   56.48   56.48   56.48   85.88   85.88   56.48   56.48
   56.48   56.48   56.48   56.48   56.48   56.48   56.48   56.48   56.48   56.48
   56.48   56.48   56.48   56.48   56.48   56.48
Pier Skew, UpSta & Num, DnSta & Num=  ,4957.1, 2 ,4957.1, 2 , 0 , 0 , 0 ,0,0
     1.1     1.1
   83.07   85.88
     1.1     1.1
   83.79   85.88
Pier Skew, UpSta & Num, DnSta & Num=  ,4974.3, 2 ,4974.3, 2 , 0 , 0 , 0 ,0,0
     1.1     1.1
   82.65   85.88
     1.1     1.1
   82.89   85.88
Pier Skew, UpSta & Num, DnSta & Num=  ,4991.4, 2 ,4991.4, 2 , 0 , 0 , 0 ,0,0
     1.1     1.1
    78.6   85.88
     1.1     1.1
   78.35   85.88
Pier Skew, UpSta & Num, DnSta & Num=  ,5008.6, 2 ,5008.6, 2 , 0 , 0 , 0 ,0,0
     1.1     1.1
    78.6   85.88
     1.1     1.1
   78.35   85.88
Pier Skew, UpSta & Num, DnSta & Num=  ,5025.8, 2 ,5025.8, 2 , 0 , 0 , 0 ,0,0
     1.1     1.1
   82.47   85.88
     1.1     1.1
   82.36   85.88
Pier Skew, UpSta & Num, DnSta & Num=  ,5042.9, 2 ,5042.9, 2 , 0 , 0 , 0 ,0,0
     1.1     1.1
   82.62   85.88
     1.1     1.1
   82.72   85.88
Abutment Skew #Up #Dn= , 2 , 2
  4948.5    4957
   85.88   83.08
  4948.5    4957
   85.88   83.79
Abutment Skew #Up #Dn= , 2 , 2
    5043  5051.5
   82.62   85.88
    5043  5051.5
   82.72   85.88
BR Coef= 1 , 1 , 0 ,1.25, 0 ,,,0.8,0,2,0,
WSPro=,,,, 1 ,,,, 0 ,,,, 0 ,,,,-1 ,-1 ,-1 , 0 , 0 , 0 , 0 , 0
BC Design=,, 0 ,, 0 ,,,,,,
BC HTab HWMax=90.94
BC Use User HTab Curves=0
BC User HTab FreeFlow(D)= 0

Type RM Length L Ch R = 1 ,88765   ,304,304,304
BEGIN DESCRIPTION:
Mullberry Road at Indian Fields - DS
END DESCRIPTION:
XS GIS Cut Line= 5
      2129981.44       513864.07      2129981.16       512511.49
      2129981.45       512252.68      2130017.77        511983.4
      2130162.47       511562.17
#Sta/Elev= 30
  3643.4   88.77  3853.4   87.44  3883.4   85.88  3933.4   85.92  3943.4   87.63
  3963.4   87.96  4263.4   84.51  4533.4    85.8  4593.4   83.93  4743.4   84.72
  4783.4   83.39  4823.4   84.99  4943.4   84.04    4985   82.13    4995   76.23
    5005   76.23    5015   82.13    5106   83.85    5136   82.98    5186   84.78
  5314.8   83.08  5354.8   85.69  5454.8   86.67  5524.8   85.04  5536.5   86.45
  5606.5   86.81  5636.5    85.8  5846.5   87.65  5916.5   86.94  5971.9   88.99
#Mann= 3 ,-1,0
  3643.4     .12       0    4985    .045       0    5015     .12       0
#XS Ineff= 2 , 0
       0    4300   88.06    5300       0   88.06
Permanent Ineff=
       F       F
Bank Sta=4985,5015
XS Rating Curve= 0 ,0
Exp/Cntr=0.5,0.3

Type RM Length L Ch R = 1 ,88461   ,500,500,500
BEGIN DESCRIPTION:
Indian Field Swamp 177.0
END DESCRIPTION:
XS GIS Cut Line= 3
      2129996.28        513885.4      2130267.44       512594.88
      2130544.81       512042.39
#Sta/Elev= 30
  3681.3    88.4  3851.3   87.45  3861.3    86.1  3901.3   86.62  3911.3   87.79
  4051.3   86.58  4061.3    87.2  4631.3   83.04  4741.3   83.35  4761.3   84.57
  4771.3   83.78  4831.3   84.26  4851.3   83.23  4941.3   82.85  4971.3   84.41
  4979.6   80.58  4981.1   77.58  5018.9   77.58  5020.4   80.58    5030   84.69
    5050    83.8    5090   84.42    5130   83.41    5170   83.89    5190   82.77
    5230    83.6    5310   82.58    5340      83    5370   85.75  5618.2    87.4
#Mann= 3 ,-1,0
  3681.3     .14       0  4979.6    .045       0  5020.4     .14       0
Bank Sta=4979.6,5020.4
XS Rating Curve= 0 ,0
Exp/Cntr=0.3,0.1

Type RM Length L Ch R = 1 ,87961   ,500,500,500
BEGIN DESCRIPTION:
Indian Field Swamp 176.0
END DESCRIPTION:
XS GIS Cut Line= 3
      2130507.86       513642.86       2130754.5       512699.57
      2130892.15       512138.41
#Sta/Elev= 30
    4025   88.33    4215    85.5    4275    85.3    4295   84.58    4325   84.33
    4485    83.9    4635   82.73    4675      83    4685   83.32    4695   84.56
    4715   82.79    4735   82.42    4765    82.8    4835   82.43    4915   82.93
    4945   82.43  4979.6   80.25  4981.1   77.25  5018.9   77.25  5020.4   80.25
    5060   82.54    5100   82.66    5120   84.14    5130   82.92    5140   82.51
    5170   82.25    5220   86.19    5250   87.25    5280    87.7  5577.8   87.14
#Mann= 3 ,-1,0
    4025     .14       0  4979.6    .045       0  5020.4     .14       0
Bank Sta=4979.6,5020.4
XS Rating Curve= 0 ,0
Exp/Cntr=0.3,0.1

Type RM Length L Ch R = 1 ,87461   ,500,500,500
BEGIN DESCRIPTION:
Indian Field Swamp 175.0
END DESCRIPTION:
XS GIS Cut Line= 3
      2131652.22       513527.56      2131252.45       512706.74
      2130957.33       512122.99
#Sta/Elev= 30
    4087   90.06    4257   89.22    4377   86.55    4397   86.65    4407   87.85
    4427    83.8    4467   82.64    4497   83.92    4547   82.31    4647   82.52
    4657   83.04    4697   82.18    4747   82.71    4837   82.54    4877   81.98
    4897   82.77    4927   82.85  4979.6   79.98  4981.1   76.98  5018.9   76.98
  5020.4   79.98    5120   82.23    5260   82.14    5280   83.35    5380   85.63
    5390   84.71    5400   85.66    5510   85.72    5620   86.95  5654.1   86.82
#Mann= 3 ,-1,0
    4087     .14       0  4979.6    .045       0  5020.4     .14       0
Bank Sta=4979.6,5020.4
XS Rating Curve= 0 ,0
Exp/Cntr=0.3,0.1

Type RM Length L Ch R = 1 ,86961   ,500,500,500
BEGIN DESCRIPTION:
Indian Field Swamp 174.0
END DESCRIPTION:
XS GIS Cut Line= 3
      2132059.25       513124.25      2131702.89       512557.58
      2131258.96       511856.88
#Sta/Elev= 30
  4330.6   92.27  4390.6   91.65  4580.6   86.96  4620.6   85.31  4650.6   81.69
  4660.6   82.14  4680.6   81.23  4710.6   82.01  4780.6   81.55  4840.6   82.34
  4940.6   81.53  4950.6   82.26  4960.6   82.19  4970.6   81.91  4979.6   79.22
  4981.1   76.22  5018.9   76.22  5020.4   79.22    5040   81.96    5100   82.17
    5140   81.22    5160   82.32    5190   81.58    5350   82.67    5480   82.71
    5570   84.73    5760   86.65    5790   87.49    5820   86.46  5829.5   86.73
#Mann= 3 ,-1,0
  4330.6     .11       0  4979.6    .045       0  5020.4     .11       0
Bank Sta=4979.6,5020.4
XS Rating Curve= 0 ,0
Exp/Cntr=0.3,0.1

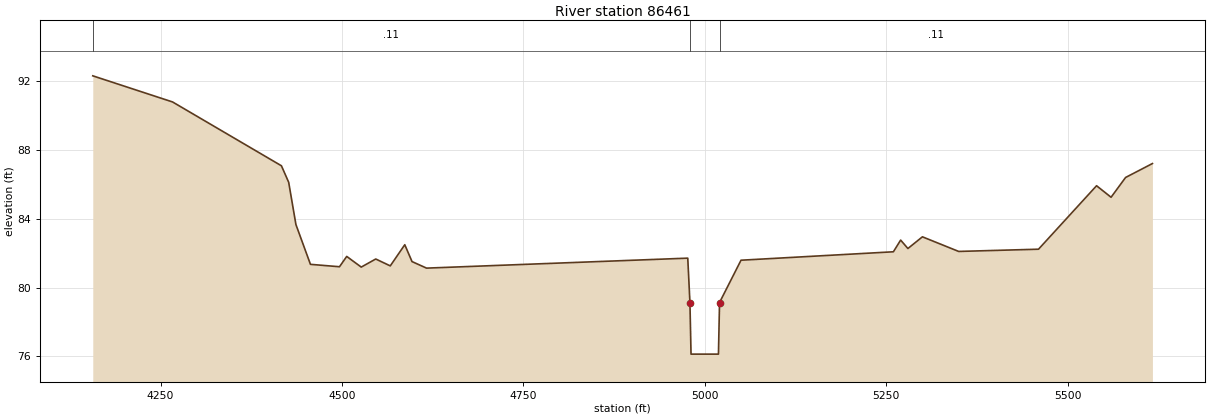
Type RM Length L Ch R = 1 ,86461   ,509,509,509
BEGIN DESCRIPTION:
Indian Field Swamp 173.0
END DESCRIPTION:
XS GIS Cut Line= 3
       2132335.3       512853.37      2131865.07       512153.21
      2131530.04        511635.1
#Sta/Elev= 30
  4156.6   92.31  4266.6   90.79  4416.6   87.08  4426.6   86.12  4436.6   83.66
  4456.6   81.35  4496.6   81.21  4506.6   81.81  4526.6   81.19  4546.6   81.66
  4566.6   81.26  4586.6   82.49  4596.6   81.51  4616.6   81.13  4976.6   81.71
  4979.6   79.13  4981.1   76.13  5018.9   76.13  5020.4   79.13    5050   81.59
    5260   82.08    5270   82.76    5280   82.27    5300   82.95    5350    82.1
    5460   82.23    5540   85.92    5560   85.25    5580    86.4    5617   87.21
#Mann= 3 ,-1,0
  4156.6     .11       0  4979.6    .045       0  5020.4     .11       0
Bank Sta=4979.6,5020.4
XS Rating Curve= 0 ,0
Exp/Cntr=0.3,0.1