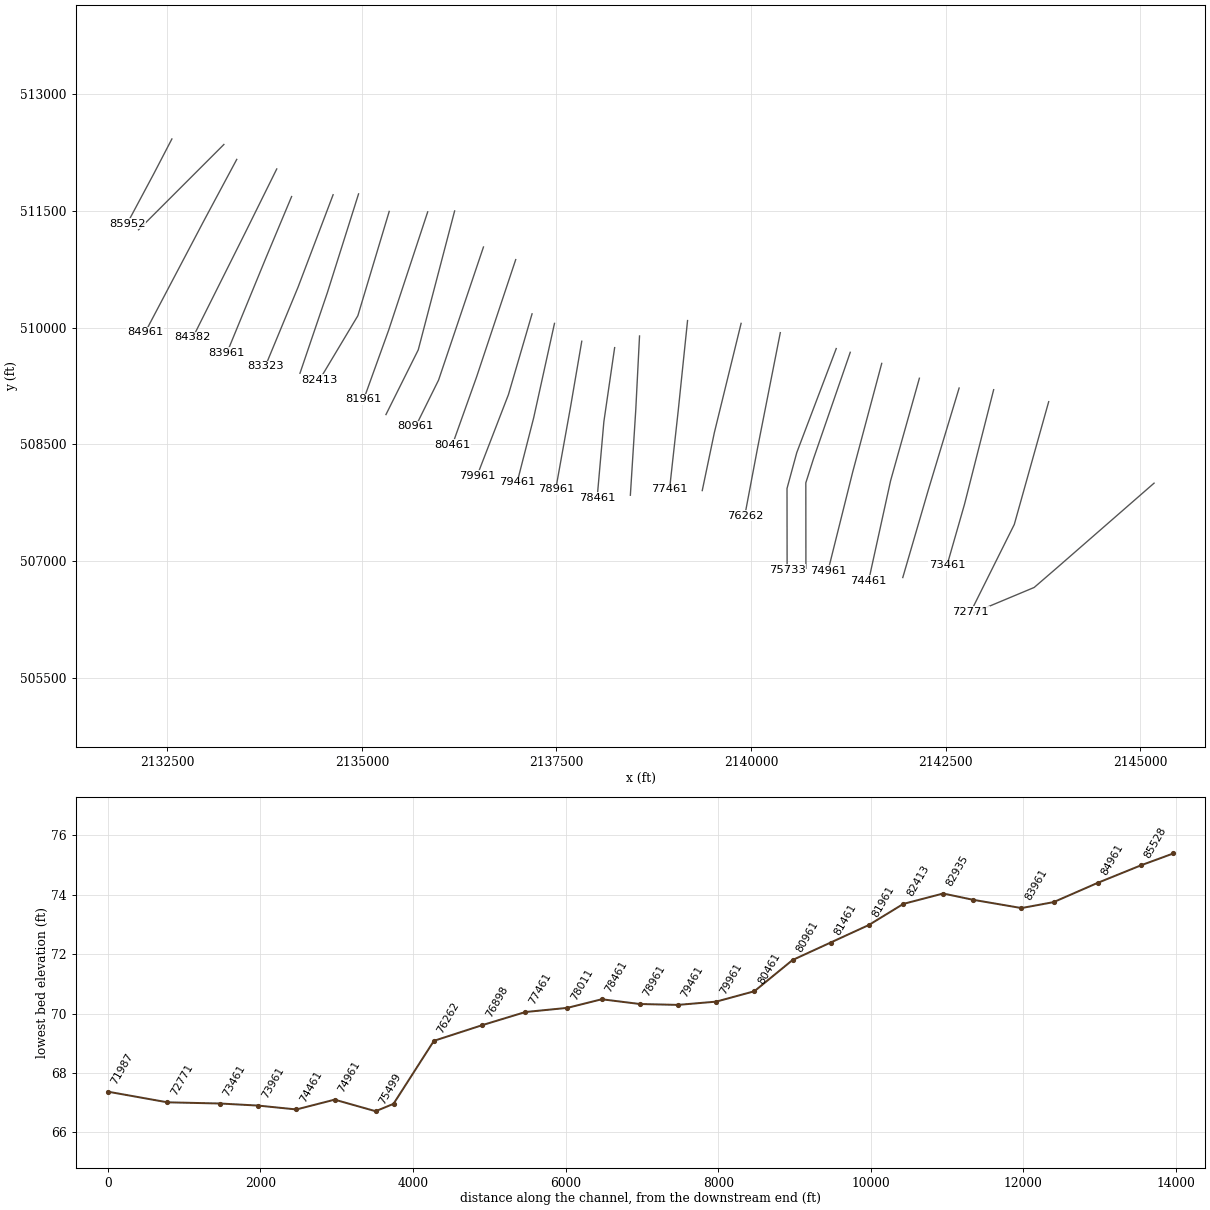
HEC-RAS study IndianFieldsSwamp.prj: S-18-19 over Indian Fields Swamp

--- IndianFieldsSwamp.g02 (geometry) --- (continued)

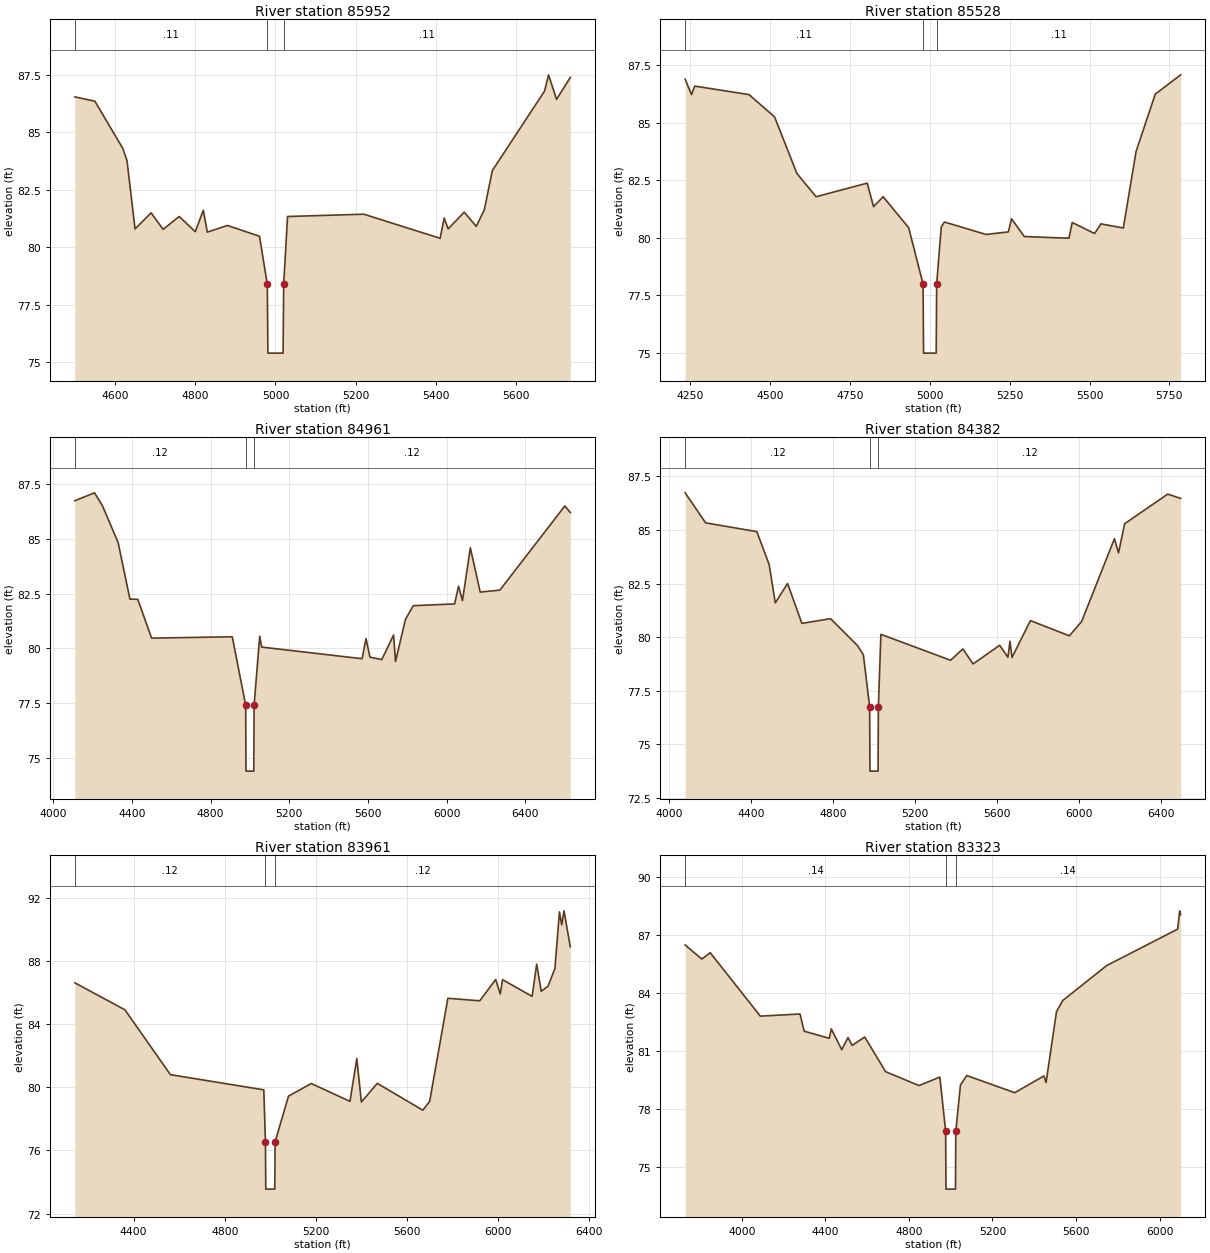
Type RM Length L Ch R = 1 ,85952   ,424,424,424
BEGIN DESCRIPTION:
Indian Field Swamp 172.0
END DESCRIPTION:
XS GIS Cut Line= 3
      2132557.06       512424.57      2132326.42       511981.03
      2131980.46       511333.47
#Sta/Elev= 30
  4500.2   86.55  4550.2   86.36  4620.2   84.29  4630.2   83.77  4650.2    80.8
  4690.2    81.5  4720.2   80.78  4760.2   81.34  4800.2   80.68  4820.2   81.61
  4830.2   80.66  4880.2   80.95  4960.2   80.48  4979.6   78.39  4981.1   75.39
  5018.9   75.39  5020.4   78.39  5030.1   81.34  5220.1   81.44  5410.1   80.39
  5420.1   81.27  5430.1    80.8  5470.1   81.53  5500.1   80.91  5520.1   81.63
  5540.1   83.34  5670.1    86.8  5680.1   87.51  5700.1   86.44  5734.3    87.4
#Mann= 3 ,-1,0
  4500.2     .11       0  4979.6    .045       0  5020.4     .11       0
Bank Sta=4979.6,5020.4
XS Rating Curve= 0 ,0
Exp/Cntr=0.3,0.1

Type RM Length L Ch R = 1 ,85528   ,567,567,567
BEGIN DESCRIPTION:
Indian Field Swamp 171.0
END DESCRIPTION:
XS GIS Cut Line= 3
      2133225.37       512353.64      2132672.39       511800.66
      2132128.29       511256.56
#Sta/Elev= 30
  4233.7    86.9  4253.7   86.23  4263.7    86.6  4433.7   86.23  4513.7   85.26
  4583.7    82.8  4643.7   81.79  4803.7   82.38  4823.7   81.36  4853.7   81.79
  4933.7   80.44  4978.7   77.99  4980.2   74.99  5019.8   74.99  5021.3   77.99
  5035.7   80.48  5045.7   80.69  5175.7   80.15  5245.7   80.26  5255.7   80.83
  5295.7   80.06  5385.7   80.01  5435.7   79.99  5445.7   80.67  5515.7   80.19
  5535.7   80.61  5605.7   80.43  5645.7   83.76  5705.7   86.25  5785.2   87.09
#Mann= 3 ,-1,0
  4233.7     .11       0  4978.7    .045       0  5021.3     .11       0
Bank Sta=4978.7,5021.3
XS Rating Curve= 0 ,0
Exp/Cntr=0.3,0.1

Type RM Length L Ch R = 1 ,84961   ,579,579,579
BEGIN DESCRIPTION:
Indian Field Swamp 170.0
END DESCRIPTION:
XS GIS Cut Line= 3
       2133390.7       512161.84      2132970.85       511377.77
      2132212.52       509937.41
#Sta/Elev= 30
  4110.6   86.74  4210.6    87.1  4250.6   86.52  4330.6   84.83  4390.6   82.25
  4430.6   82.24  4500.6   80.47  4910.6   80.53  4978.7    77.4  4980.2    74.4
  5019.8    74.4  5021.3    77.4    5050   80.56    5060   80.06    5570   79.53
    5590   80.45    5610    79.6    5670   79.49    5730   80.61    5740    79.4
    5790   81.32    5830   81.95    6040   82.03    6060   82.84    6080   82.18
    6120   84.59    6170   82.57    6270   82.66    6600    86.5  6627.8    86.2
#Mann= 3 ,-1,0
  4110.6     .12       0  4978.7    .045       0  5021.3     .12       0
Bank Sta=4978.7,5021.3
XS Rating Curve= 0 ,0
Exp/Cntr=0.3,0.1

Type RM Length L Ch R = 1 ,84382   ,421,421,421
BEGIN DESCRIPTION:
Indian Field Swamp 169.0
END DESCRIPTION:
XS GIS Cut Line= 3
      2133904.76       512039.07      2133494.44       511209.25
      2132826.64       509873.73
#Sta/Elev= 30
    4078   86.73    4178   85.33    4428   84.92    4488   83.39    4518    81.6
    4578    82.5    4648   80.64    4788   80.86    4918   79.62    4948   79.18
  4978.7   76.75  4980.2   73.75  5019.8   73.75  5021.3   76.75  5033.7   80.13
  5373.7   78.92  5433.7   79.45  5483.7   78.75  5613.7   79.62  5653.7   79.06
  5663.7   79.81  5673.7   79.05  5763.7   80.77  5953.7   80.06  6013.7   80.73
  6173.7   84.59  6193.7   83.93  6223.7   85.29  6433.7   86.67  6496.9   86.47
#Mann= 3 ,-1,0
    4078     .12       0  4978.7    .045       0  5021.3     .12       0
Bank Sta=4978.7,5021.3
XS Rating Curve= 0 ,0
Exp/Cntr=0.3,0.1

Type RM Length L Ch R = 1 ,83961   ,638,638,638
BEGIN DESCRIPTION:
Indian Field Swamp 168.0
END DESCRIPTION:
XS GIS Cut Line= 3
      2134095.81       511684.23      2133764.23       510892.35
      2133263.34       509673.56
#Sta/Elev= 30
  4141.5   86.62  4361.5   84.91  4561.5    80.8  4971.5   79.84  4978.7   76.55
  4980.2   73.55  5019.8   73.55  5021.3   76.55    5080   79.44    5180   80.24
    5350   79.11    5380   81.82    5400   79.07    5470   80.25    5670   78.55
    5700   79.11    5780   85.64    5920   85.48    5990   86.83    6010   85.91
    6020   86.82    6150   85.76    6170    87.8    6190   86.08    6220   86.41
    6250   87.52    6270   91.11    6280   90.29    6290   91.18  6317.7    88.9
#Mann= 3 ,-1,0
  4141.5     .12       0  4978.7    .045       0  5021.3     .12       0
Bank Sta=4978.7,5021.3
XS Rating Curve= 0 ,0
Exp/Cntr=0.3,0.1

Type RM Length L Ch R = 1 ,83323   ,388,388,388
BEGIN DESCRIPTION:
Indian Field Swamp 167.0
END DESCRIPTION:
XS GIS Cut Line= 3
      2134629.19        511707.5      2134179.21       510521.34
      2133756.87       509500.83
#Sta/Elev= 30
    3728   86.49    3808   85.76    3848   86.09    4088    82.8    4278   82.91
    4298   82.02    4418   81.65    4428   82.14    4478   81.06    4508   81.69
    4528   81.28    4588   81.72    4688   79.92    4848    79.2    4948   79.64
  4975.7   76.83  4977.2   73.83  5022.8   73.83  5024.3   76.83  5046.6   79.23
  5076.6   79.72  5306.6   78.83  5446.6    79.7  5456.6   79.36  5506.6   83.03
  5536.6   83.61  5746.6   85.42  6086.6   87.31  6096.6   88.26  6101.1   88.07
#Mann= 3 ,-1,0
    3728     .14       0  4975.7    .045       0  5024.3     .14       0
Bank Sta=4975.7,5024.3
XS Rating Curve= 0 ,0
Exp/Cntr=0.3,0.1

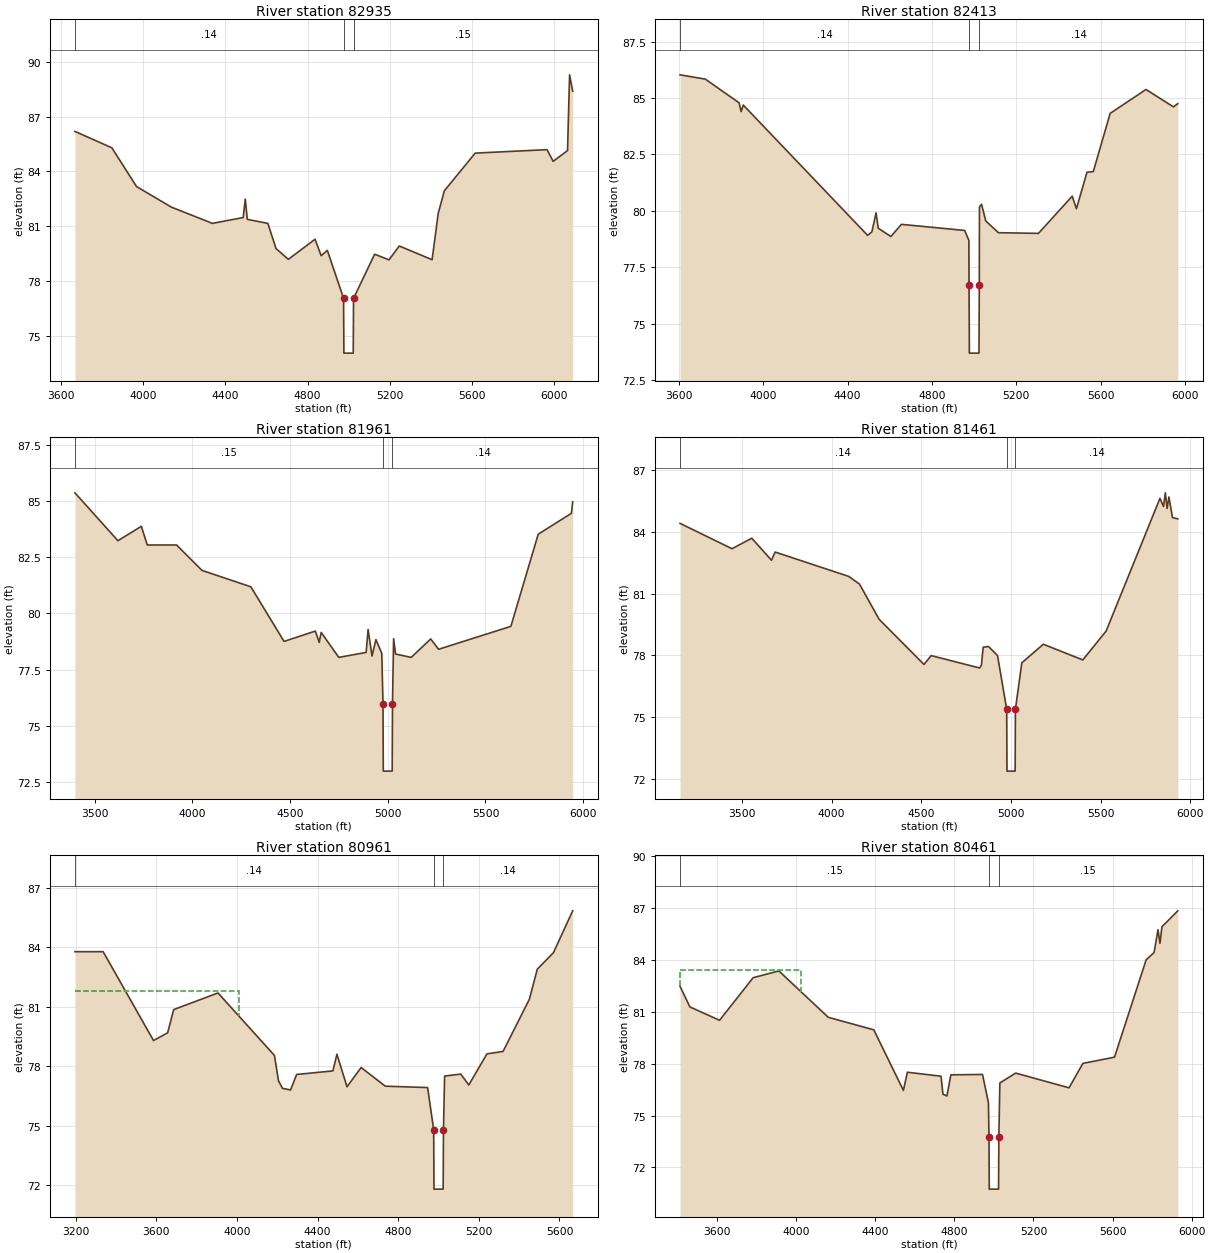
Type RM Length L Ch R = 1 ,82935   ,522,522,522
BEGIN DESCRIPTION:
Indian Field Swamp 166.0
END DESCRIPTION:
XS GIS Cut Line= 3
      2134956.32       511718.61      2134555.61       510449.87
       2134203.2       509413.04
#Sta/Elev= 30
  3666.6   86.19  3846.6   85.29  3966.6   83.17  4136.6   82.04  4336.6   81.15
  4486.6   81.47  4496.6   82.48  4506.6   81.37  4606.6   81.15  4646.6   79.77
  4706.6   79.18  4836.6   80.28  4866.6   79.38  4896.6   79.67  4975.7   77.04
  4977.2   74.04  5022.8   74.04  5024.3   77.04  5127.1   79.46  5197.1   79.15
  5247.1   79.91  5407.1   79.16  5437.1   81.71  5467.1   82.94  5617.1      85
  5967.1   85.19  5997.1   84.55  6067.1   85.14  6077.1   89.29  6092.2   88.39
#Mann= 3 ,-1,0
  3666.6     .14       0  4975.7    .045       0  5024.3     .15       0
Bank Sta=4975.7,5024.3
XS Rating Curve= 0 ,0
Exp/Cntr=0.3,0.1

Type RM Length L Ch R = 1 ,82413   ,452,452,452
BEGIN DESCRIPTION:
Indian Field Swamp 165.0
END DESCRIPTION:
XS GIS Cut Line= 3
      2135350.16       511493.22      2134947.08        510152.3
      2134453.71       509327.83
#Sta/Elev= 30
  3604.8   86.03  3724.8   85.84  3884.8   84.79  3894.8    84.4  3904.8   84.69
  4494.8   78.91  4514.8   79.07  4534.8   79.91  4544.8   79.23  4604.8   78.86
  4654.8    79.4  4954.8   79.13  4974.8   78.69  4975.7   76.69  4977.2   73.69
  5022.8   73.69  5024.3   76.69    5025   80.17    5035   80.29    5055   79.55
    5115   79.03    5305      79    5465   80.65    5485   80.09    5535   81.71
    5565   81.74    5645   84.32    5815   85.38    5945   84.61  5965.8   84.75
#Mann= 3 ,-1,0
  3604.8     .14       0  4975.7    .045       0  5024.3     .14       0
Bank Sta=4975.7,5024.3
XS Rating Curve= 0 ,0
Exp/Cntr=0.3,0.1

Type RM Length L Ch R = 1 ,81961   ,500,500,500
BEGIN DESCRIPTION:
Indian Field Swamp 164.0
END DESCRIPTION:
XS GIS Cut Line= 3
      2135844.98       511487.77      2135343.37        509967.9
      2135022.54       509077.65
#Sta/Elev= 30
  3399.5   85.36  3619.5   83.23  3739.5   83.87  3769.5   83.04  3919.5   83.04
  4049.5   81.91  4299.5   81.18  4469.5   78.75  4629.5   79.21  4649.5   78.71
  4659.5   79.15  4749.5   78.04  4889.5   78.26  4899.5   79.28  4919.5    78.1
  4939.5   78.83  4969.5   78.22  4975.7   75.98  4977.2   72.98  5022.8   72.98
  5024.3   75.98    5030   78.87    5040   78.19    5120   78.04    5220   78.86
    5260    78.4    5630   79.42    5770   83.52    5940   84.45  5946.3   84.96
#Mann= 3 ,-1,0
  3399.5     .15       0  4975.7    .045       0  5024.3     .14       0
Bank Sta=4975.7,5024.3
XS Rating Curve= 0 ,0
Exp/Cntr=0.3,0.1

Type RM Length L Ch R = 1 ,81461   ,500,500,500
BEGIN DESCRIPTION:
Indian Field Swamp 163.0
END DESCRIPTION:
XS GIS Cut Line= 3
      2136190.86       511499.27      2135723.47       509714.04
      2135308.44       508882.35
#Sta/Elev= 30
  3154.6    84.4  3444.6   83.17  3554.6   83.68  3664.6   82.61  3684.6   83.01
  4094.6   81.83  4154.6   81.46  4264.6   79.75  4514.6   77.56  4554.6   77.99
  4824.6   77.39  4834.6   77.52  4844.6    78.4  4874.6   78.43  4924.6   77.99
  4975.7   75.39  4977.2   72.39  5022.8   72.39  5024.3   75.39    5060   77.64
    5180   78.54    5400   77.78    5530   79.18    5830   85.61    5850   85.22
    5860   85.88    5870   85.12    5880   85.68    5900   84.68  5929.5   84.62
#Mann= 3 ,-1,0
  3154.6     .14       0  4975.7    .045       0  5024.3     .14       0
Bank Sta=4975.7,5024.3
XS Rating Curve= 0 ,0
Exp/Cntr=0.3,0.1

Type RM Length L Ch R = 1 ,80961   ,500,500,500
BEGIN DESCRIPTION:
Indian Field Swamp 162.0
END DESCRIPTION:
XS GIS Cut Line= 3
      2136561.52       511035.95      2135984.94       509326.26
      2135689.61       508729.88
#Sta/Elev= 30
  3195.7   83.77  3335.7   83.77  3585.7   79.29  3655.7   79.68  3685.7   80.85
  3905.7   81.69  4185.7   78.54  4205.7   77.26  4225.7   76.88  4265.7    76.8
  4295.7   77.58  4475.7   77.76  4495.7    78.6  4545.7   76.96  4615.7   77.93
  4735.7   76.99  4945.7   76.92  4975.7    74.8  4977.2    71.8  5022.8    71.8
  5024.3    74.8    5030    77.5    5110    77.6    5150   77.05    5240   78.62
    5320   78.74    5450   81.36    5490   82.89    5570   83.72  5665.5   85.83
#Mann= 3 ,-1,0
  3195.7     .14       0  4975.7    .045       0  5024.3     .14       0
#XS Ineff= 2 , 0
       0  4009.8   81.78               0
Permanent Ineff=
       F       F
Bank Sta=4975.7,5024.3
XS Rating Curve= 0 ,0
Exp/Cntr=0.3,0.1

Type RM Length L Ch R = 1 ,80461   ,500,500,500
BEGIN DESCRIPTION:
Indian Field Swamp 161.0
END DESCRIPTION:
XS GIS Cut Line= 3
      2136976.03       510873.91      2136473.74       509367.65
      2136161.28       508491.61
#Sta/Elev= 30
  3412.2   82.46  3462.2   81.27  3612.2    80.5  3782.2   82.96  3912.2   83.35
  4162.2   80.67  4392.2   79.95  4542.2   76.45  4562.2    77.5  4732.2   77.27
  4742.2   76.23  4762.2   76.13  4782.2   77.35  4942.2   77.37  4972.2   75.75
    4975   73.75  4976.5   70.75  5023.5   70.75    5025   73.75    5030   76.88
    5110   77.45    5380    76.6    5450   78.01    5610   78.37    5770   83.99
    5810   84.41    5830   85.73    5840   84.94    5850    85.9  5930.1   86.82
#Mann= 3 ,-1,0
  3412.2     .15       0    4975    .045       0    5025     .15       0
#XS Ineff= 2 , 0
       0  4026.4   83.41               0
Permanent Ineff=
       F       F
Bank Sta=4975,5025
XS Rating Curve= 0 ,0
Exp/Cntr=0.3,0.1

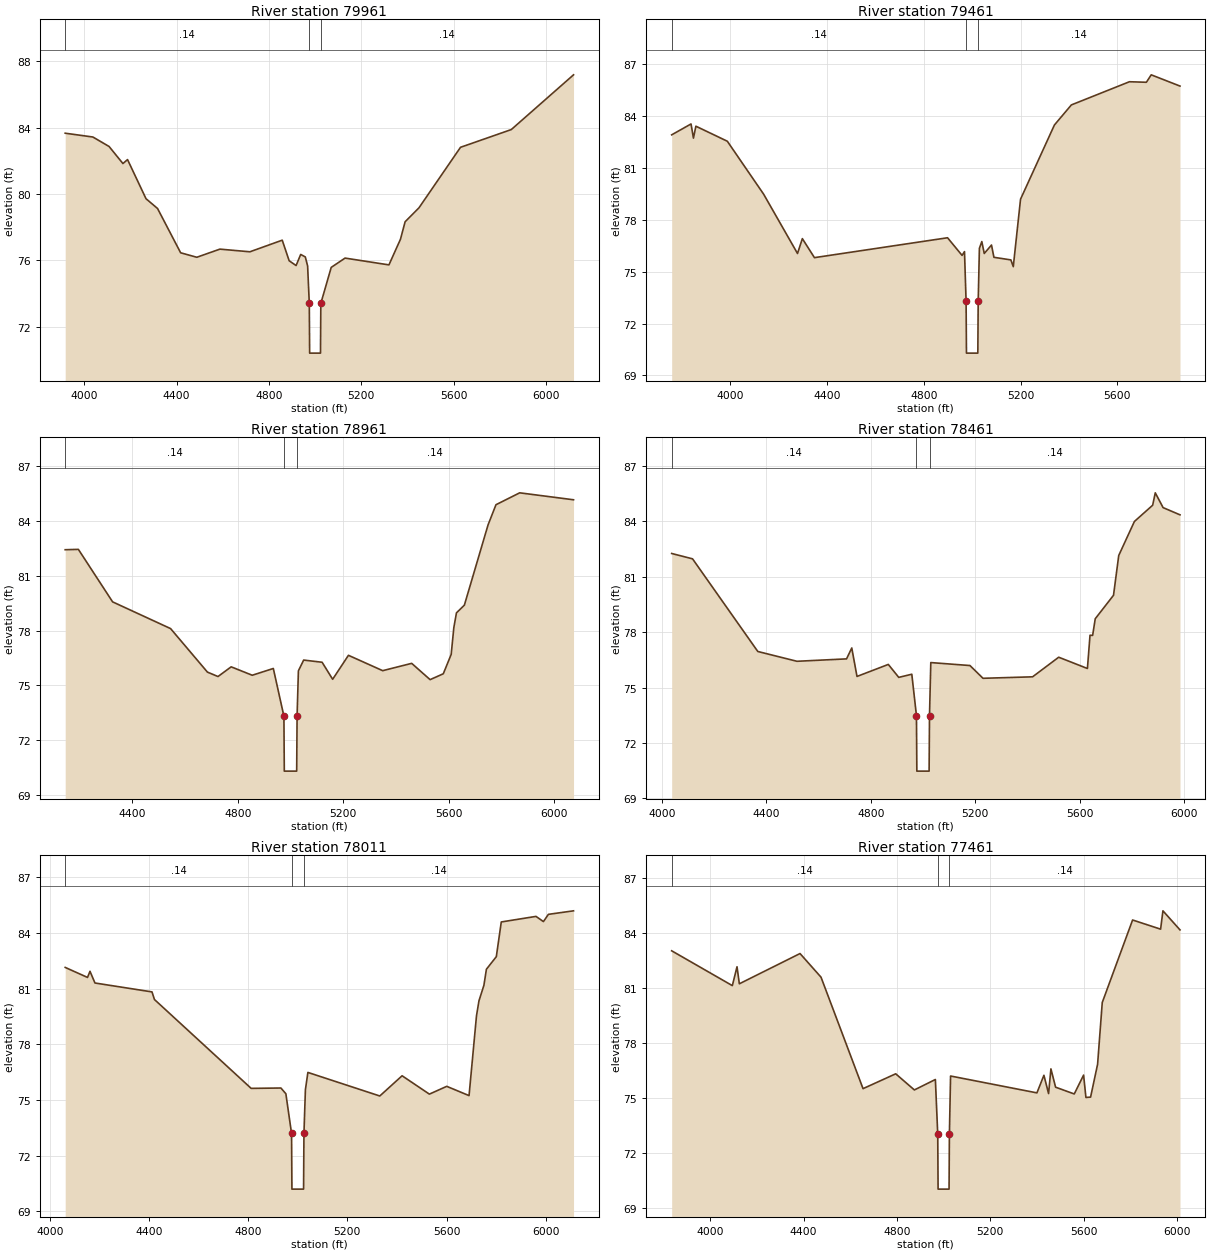
Type RM Length L Ch R = 1 ,79961   ,500,500,500
BEGIN DESCRIPTION:
Indian Field Swamp 160.0
END DESCRIPTION:
XS GIS Cut Line= 3
      2137186.23       510177.17      2136882.46       509138.47
      2136479.08       508094.17
#Sta/Elev= 30
  3917.8   83.66  4037.8   83.43  4107.8   82.86  4167.8   81.83  4187.8   82.07
  4267.8   79.71  4317.8   79.12  4417.8   76.45  4487.8   76.18  4587.8   76.67
  4717.8   76.51  4857.8   77.21  4887.8   75.97  4917.8   75.68  4937.8   76.35
  4957.8    76.2  4967.8   75.65    4975    73.4  4976.5    70.4  5023.5    70.4
    5025    73.4    5070   75.57    5130   76.13    5320   75.72    5370   77.27
    5390   78.32    5450   79.16    5630   82.81    5850   83.88  6119.5   87.18
#Mann= 3 ,-1,0
  3917.8     .14       0    4975    .045       0    5025     .14       0
Bank Sta=4975,5025
XS Rating Curve= 0 ,0
Exp/Cntr=0.3,0.1

Type RM Length L Ch R = 1 ,79461   ,500,500,500
BEGIN DESCRIPTION:
Indian Field Swamp 159.0
END DESCRIPTION:
XS GIS Cut Line= 3
      2137474.47       510054.21      2137207.18       508841.72
      2136994.09       508009.67
#Sta/Elev= 30
  3758.4   82.91  3838.4   83.54  3848.4   82.72  3858.4   83.41  3988.4   82.54
  4138.4   79.48  4278.4   76.05  4298.4   76.91  4348.4   75.81  4898.4   76.96
  4958.4   75.94  4968.4   76.16    4975   73.29  4976.5   70.29  5023.5   70.29
    5025   73.29    5030   76.35    5040   76.74    5050   76.05    5080   76.54
    5090   75.83    5160   75.68    5170   75.29    5200   79.19    5340   83.48
    5410   84.64    5650   85.98    5720   85.95    5740   86.38  5858.9   85.73
#Mann= 3 ,-1,0
  3758.4     .14       0    4975    .045       0    5025     .14       0
Bank Sta=4975,5025
XS Rating Curve= 0 ,0
Exp/Cntr=0.3,0.1

Type RM Length L Ch R = 1 ,78961   ,500,500,500
BEGIN DESCRIPTION:
Indian Field Swamp 158.0
END DESCRIPTION:
XS GIS Cut Line= 3
      2137825.01       509825.05      2137680.96       508982.07
      2137490.62       507924.66
#Sta/Elev= 30
  4144.8   82.42  4194.8   82.44  4324.8   79.57  4544.8   78.11  4684.8   75.73
  4724.8   75.49  4774.8   76.02  4854.8   75.56  4934.8   75.93    4975   73.32
  4976.5   70.32  5023.5   70.32    5025   73.32    5030    75.8    5050   76.39
    5120   76.27    5160   75.34    5220   76.65    5350   75.81    5460   76.21
    5530   75.32    5580   75.64    5610    76.7    5620   78.16    5630   78.97
    5660   79.39    5750   83.78    5780   84.88    5870   85.53  6074.4   85.15
#Mann= 3 ,-1,0
  4144.8     .14       0    4975    .045       0    5025     .14       0
Bank Sta=4975,5025
XS Rating Curve= 0 ,0
Exp/Cntr=0.3,0.1

Type RM Length L Ch R = 1 ,78461   ,450,450,450
BEGIN DESCRIPTION:
Indian Field Swamp 157.0
END DESCRIPTION:
XS GIS Cut Line= 3
      2138247.61       509742.82      2138109.01       508790.05
      2138022.46       507809.16
#Sta/Elev= 30
  4037.2   82.25  4117.2   81.96  4367.2   76.95  4517.2   76.42  4707.2   76.55
  4727.2   77.14  4747.2    75.6  4867.2   76.25  4907.2   75.55  4957.2   75.72
    4975   73.48  4976.5   70.48  5023.5   70.48    5025   73.48    5030   76.35
    5180   76.19    5230    75.5    5420   75.58    5520   76.64    5630   76.03
    5640   77.83    5650   77.82    5660   78.72    5730   79.99    5750   82.14
    5810   83.98    5880   84.86    5890   85.53    5920   84.73  5984.7   84.34
#Mann= 3 ,-1,0
  4037.2     .14       0    4975    .045       0    5025     .14       0
Bank Sta=4975,5025
XS Rating Curve= 0 ,0
Exp/Cntr=0.3,0.1

Type RM Length L Ch R = 1 ,78011   ,550,550,550
BEGIN DESCRIPTION:
Indian Field Swamp 156.0
END DESCRIPTION:
XS GIS Cut Line= 3
      2138567.41       509892.41      2138519.11       508944.88
      2138449.58       507845.63
#Sta/Elev= 30
  4062.1   82.14  4152.1    81.6  4162.1   81.93  4182.1    81.3  4412.1   80.82
  4422.1   80.41  4812.1   75.62  4932.1   75.64  4952.1   75.33    4975   73.19
  4976.5   70.19  5023.5   70.19    5025   73.19  5030.9   75.55  5040.9   76.48
  5330.9   75.21  5420.9    76.3  5530.9   75.31  5600.9   75.73  5690.9   75.23
  5720.9   79.53  5730.9   80.34  5750.9   81.18  5760.9   82.04  5800.9   82.72
  5820.9   84.59  5960.9   84.89  5990.9   84.61  6010.9      85  6112.3   85.19
#Mann= 3 ,-1,0
  4062.1     .14       0    4975    .045       0    5025     .14       0
Bank Sta=4975,5025
XS Rating Curve= 0 ,0
Exp/Cntr=0.3,0.1

Type RM Length L Ch R = 1 ,77461   ,563,563,563
BEGIN DESCRIPTION:
Indian Field Swamp 155.0
END DESCRIPTION:
XS GIS Cut Line= 3
      2139184.62       510090.48      2139064.55       508931.59
      2138953.34       507924.61
#Sta/Elev= 30
  3834.9   83.05  4094.9   81.15  4114.9   82.18  4124.9   81.25  4384.9    82.9
  4474.9   81.61  4654.9   75.53  4794.9   76.34  4874.9   75.46  4964.9   76.03
    4975   73.05  4976.5   70.05  5023.5   70.05    5025   73.05    5030   76.22
    5400    75.3    5430   76.26    5450   75.26    5460   76.61    5480   75.61
    5560   75.24    5600   76.27    5610   75.05    5630   75.07    5660   76.86
    5680   80.23    5810   84.73    5930   84.23    5940   85.23  6013.1   84.19
#Mann= 3 ,-1,0
  3834.9     .14       0    4975    .045       0    5025     .14       0
Bank Sta=4975,5025
XS Rating Curve= 0 ,0
Exp/Cntr=0.3,0.1

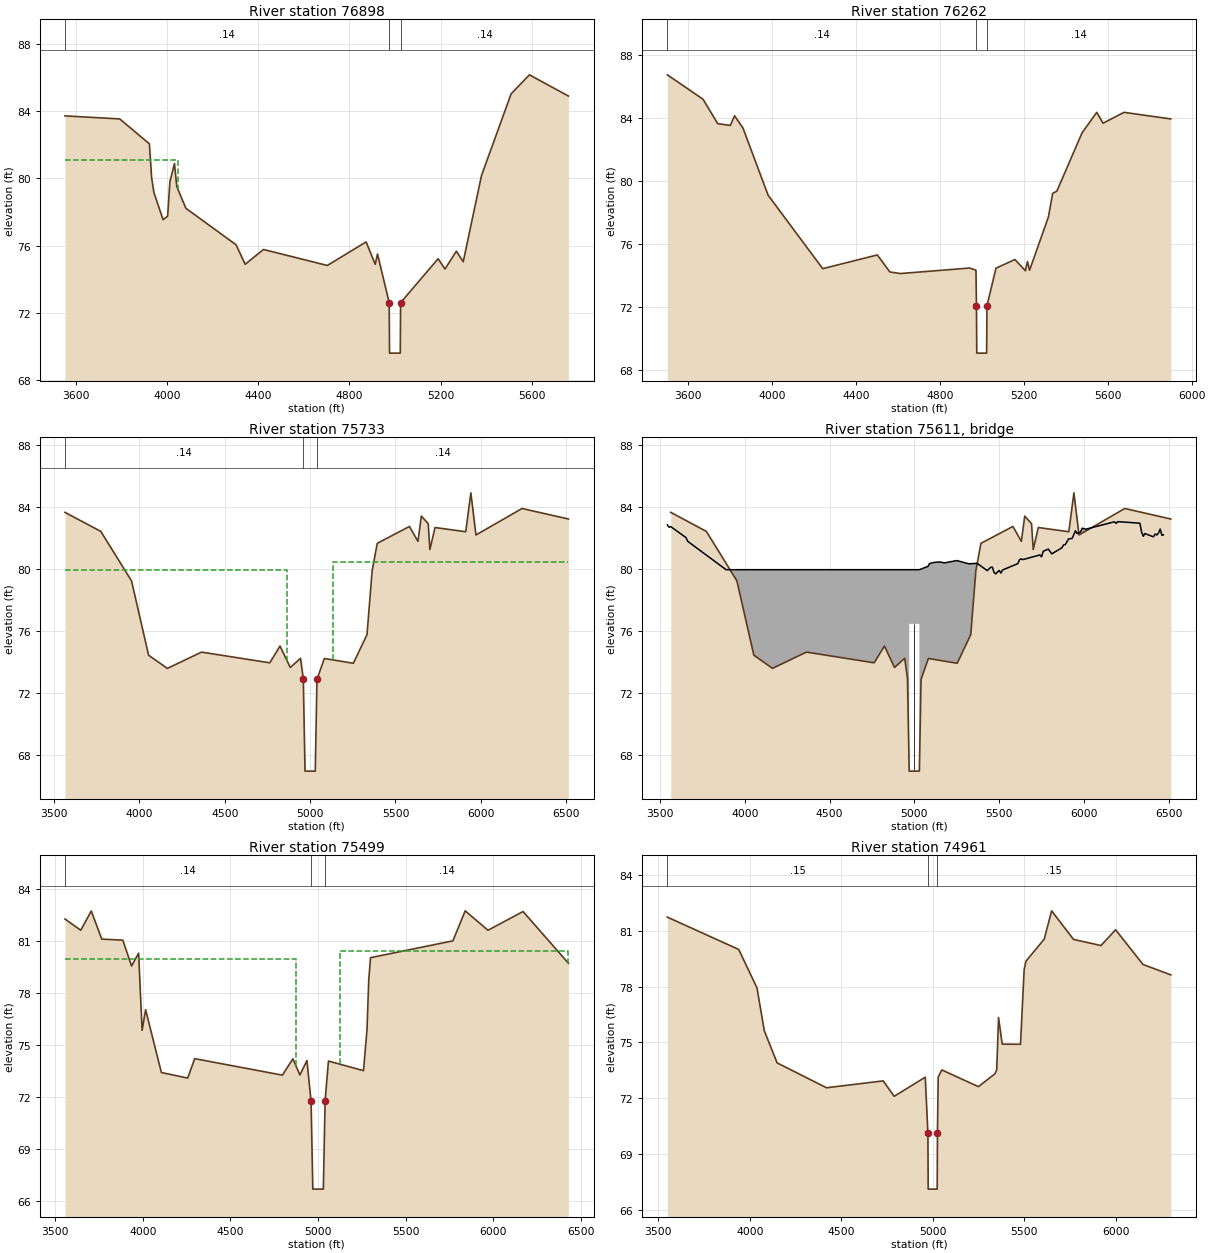
Type RM Length L Ch R = 1 ,76898   ,636,636,636
BEGIN DESCRIPTION:
Indian Field Swamp 154.0
END DESCRIPTION:
XS GIS Cut Line= 3
      2139872.91        510054.4      2139528.97        508650.2
      2139373.34       507905.19
#Sta/Elev= 30
  3553.8   83.71  3793.8   83.53  3923.8   82.05  3933.8   80.02  3943.8   79.15
  3983.8   77.54  4003.8   77.75  4013.8    79.8  4033.8   80.88  4043.8   79.51
  4083.8   78.22  4303.8   76.05  4343.8   74.89  4423.8   75.77  4703.8   74.82
  4873.8   76.22  4913.8   74.89  4923.8    75.5    4975   72.61  4976.5   69.61
  5023.5   69.61    5025   72.61  5189.5   75.22  5219.5   74.61  5269.5   75.67
  5299.5   75.04  5379.5   80.16  5509.5   85.02  5589.5   86.15  5760.6   84.89
#Mann= 3 ,-1,0
  3553.8     .14       0    4975    .045       0    5025     .14       0
#XS Ineff= 2 , 0
       0  4048.1   81.06               0
Permanent Ineff=
       F       F
Bank Sta=4975,5025
XS Rating Curve= 0 ,0
Exp/Cntr=0.3,0.1

Type RM Length L Ch R = 1 ,76262   ,529,529,529
BEGIN DESCRIPTION:
Indian Field Swamp 153.0
END DESCRIPTION:
XS GIS Cut Line= 3
      2140376.58       509934.88      2140087.32        508467.8
      2139919.66       507580.73
#Sta/Elev= 30
  3502.7   86.74  3672.7   85.19  3742.7   83.64  3802.7   83.53  3822.7   84.14
  3862.7   83.37  3982.7    79.1  4242.7   74.44  4502.7   75.31  4562.7   74.23
  4612.7   74.13  4942.7   74.48  4972.7   74.34    4975   72.08  4976.5   69.08
  5023.5   69.08    5025   72.08    5068   74.47    5158   75.02    5208   74.31
    5218   74.89    5228   74.34    5318   77.73    5338   79.22    5358   79.36
    5478   83.06    5548   84.36    5578   83.67    5678   84.36  5900.8   83.94
#Mann= 3 ,-1,0
  3502.7     .14       0    4975    .045       0    5025     .14       0
Bank Sta=4975,5025
XS Rating Curve= 0 ,0
Exp/Cntr=0.5,0.3

Type RM Length L Ch R = 1 ,75733   ,234,234,234
BEGIN DESCRIPTION:
Highway 15 at Indian Field - US
END DESCRIPTION:
XS GIS Cut Line= 4
      2141095.58       509730.61      2140588.44       508394.01
      2140462.93       507932.34       2140464.2       506890.74
#Sta/Elev= 30
  3563.6   83.66  3773.6   82.43  3953.6   79.24  4053.6   74.44  4163.6   73.59
  4363.6   74.64  4763.6   73.95  4823.6   75.03  4883.6   73.65  4943.6   74.24
    4960   72.92    4970   66.96    5030   66.96    5040   72.88  5083.2   74.23
  5253.2   73.92  5333.2   75.77  5363.2   79.89  5393.2   81.66  5581.6   82.75
  5631.6   81.79  5651.6   83.42  5691.6   82.93  5701.6   81.26  5731.6   82.68
  5911.6   82.41  5941.6   84.92  5971.6    82.2  6241.6   83.91  6513.2   83.23
#Mann= 3 ,-1,0
  3563.6     .14       0    4960    .045       0    5040     .14       0
#XS Ineff= 2 , 0
       0  4865.5   79.96  5134.5       0   80.45
Permanent Ineff=
       F       F
Bank Sta=4960,5040
XS Rating Curve= 0 ,0
Exp/Cntr=0.5,0.3

Type RM Length L Ch R = 3 ,75611   ,,,
BEGIN DESCRIPTION:
Highway 15 at Indian Field - TOR
Structure ID: LDS_IFS_05
Approximate Survey Structure
END DESCRIPTION:
Bridge Culvert--1,0,-1,-1, 0
Deck Dist Width WeirC Skew NumUp NumDn MinLoCord MaxHiCord MaxSubmerge Is_Ogee
104.5,35,3,0, 59, 59, , , 0.95, 0, 1,1,,
  3543.5  3553.5  3563.5  3653.5  3663.5  3889.8    4970    4970    5030    5030
    5080    5090    5110  5148.8  5178.8    5251    5321  5370.6  5430.6  5450.6
  5460.6  5470.6  5480.6  5500.6  5510.6  5520.6  5610.6  5620.6  5630.6  5640.6
  5740.6  5750.6  5760.6  5790.6  5810.6  5870.6  5880.6  5890.6  5910.6  5930.6
  5950.6  5960.6  5980.6  5990.6  6010.6  6180.6  6190.6  6200.6  6330.6  6340.6
  6350.6  6360.6  6410.6  6420.6  6430.6  6440.6  6450.6  6460.6  6469.6
   82.85    82.7   82.74   82.03   81.79   79.96   79.96   79.96   79.96   79.96
   80.17   80.35   80.42   80.46    80.4   80.55   80.34   80.37    79.9   80.11
   80.12   79.78   79.69   79.91   79.74   79.94   80.35    80.6   80.66   80.61
   80.91   80.79   81.15   81.29   80.98   81.37   81.56   81.58   81.95   81.97
   82.47   82.29    82.4   82.64   82.57   83.05   82.95   83.06   82.96    82.4
   82.12   82.29   82.08   82.26    82.2   82.33   82.58   82.18   82.21
   46.96   46.96   46.96   46.96   46.96   46.96   46.96   76.46   76.46   46.96
   46.96   46.96   46.96   46.96   46.96   46.96   46.96   46.96   46.96   46.96
   46.96   46.96   46.96   46.96   46.96   46.96   46.96   46.96   46.96   46.96
   46.96   46.96   46.96   46.96   46.96   46.96   46.96   46.96   46.96   46.96
   46.96   46.96   46.96   46.96   46.96   46.96   46.96   46.96   46.96   46.96
   46.96   46.96   46.96   46.96   46.96   46.96   46.96   46.96   46.96
  3543.5  3553.5  3563.5  3653.5  3663.5  3889.8    4970    4970    5030    5030
    5080    5090    5110  5148.8  5178.8    5251    5321  5370.6  5430.6  5450.6
  5460.6  5470.6  5480.6  5500.6  5510.6  5520.6  5610.6  5620.6  5630.6  5640.6
  5740.6  5750.6  5760.6  5790.6  5810.6  5870.6  5880.6  5890.6  5910.6  5930.6
  5950.6  5960.6  5980.6  5990.6  6010.6  6180.6  6190.6  6200.6  6330.6  6340.6
  6350.6  6360.6  6410.6  6420.6  6430.6  6440.6  6450.6  6460.6  6469.6
   82.85    82.7   82.74   82.03   81.79   79.96   79.96   79.96   79.96   79.96
   80.17   80.35   80.42   80.46    80.4   80.55   80.34   80.37    79.9   80.11
   80.12   79.78   79.69   79.91   79.74   79.94   80.35    80.6   80.66   80.61
   80.91   80.79   81.15   81.29   80.98   81.37   81.56   81.58   81.95   81.97
   82.47   82.29    82.4   82.64   82.57   83.05   82.95   83.06   82.96    82.4
   82.12   82.29   82.08   82.26    82.2   82.33   82.58   82.18   82.21
   46.96   46.96   46.96   46.96   46.96   46.96   46.96   76.46   76.46   46.96
   46.96   46.96   46.96   46.96   46.96   46.96   46.96   46.96   46.96   46.96
   46.96   46.96   46.96   46.96   46.96   46.96   46.96   46.96   46.96   46.96
   46.96   46.96   46.96   46.96   46.96   46.96   46.96   46.96   46.96   46.96
   46.96   46.96   46.96   46.96   46.96   46.96   46.96   46.96   46.96   46.96
   46.96   46.96   46.96   46.96   46.96   46.96   46.96   46.96   46.96
Pier Skew, UpSta & Num, DnSta & Num=  ,5000, 2 ,5000, 2 , 0 , 0 , 0 ,0,0
     1.5     1.5
   66.96   76.46
     1.5     1.5
   66.71   76.46
BR Coef= 1 , 1 , 0 ,1.25, 0 ,,,0.8,-1,2,0,
WSPro=,,,, 1 ,,,, 0 ,,,, 0 ,,,,-1 ,-1 ,-1 , 0 , 0 , 0 , 0 , 0
BC Design=,, 0 ,, 0 ,,,,,,
BC HTab HWMax=84.92
BC Use User HTab Curves=0
BC User HTab FreeFlow(D)= 0

Type RM Length L Ch R = 1 ,75499   ,538,538,538
BEGIN DESCRIPTION:
Highway 15 at Indian Field - DS
END DESCRIPTION:
XS GIS Cut Line= 4
      2141275.76       509682.61      2140804.65       508318.96
      2140704.57       508004.64      2140705.76       506905.85
#Sta/Elev= 30
  3556.4   82.28  3646.4   81.63  3706.4   82.74  3766.4   81.12  3886.4   81.06
  3936.4   79.57  3976.4   80.31  3996.4   75.86  4016.4   77.05  4106.4   73.43
  4256.4   73.11  4296.4   74.23  4796.4   73.28  4856.4   74.22  4896.4   73.29
  4936.4   74.12    4960   71.79    4970   66.71    5030   66.71    5040   71.79
  5059.1   74.09  5259.1   73.54  5279.1   75.91  5289.1   78.78  5299.1   80.05
    5769   81.02    5839   82.75    5969   81.63    6169   82.71  6427.8   79.73
#Mann= 3 ,-1,0
  3556.4     .14       0    4960    .045       0    5040     .14       0
#XS Ineff= 2 , 0
       0  4875.5   79.96  5124.5       0   80.43
Permanent Ineff=
       F       F
Bank Sta=4960,5040
XS Rating Curve= 0 ,0
Exp/Cntr=0.5,0.3

Type RM Length L Ch R = 1 ,74961   ,500,500,500
BEGIN DESCRIPTION:
Indian Field Swamp 150.0
END DESCRIPTION:
XS GIS Cut Line= 3
      2141680.12       509539.81       2141305.6       508138.49
      2140990.22       506875.47
#Sta/Elev= 30
  3549.5   81.75  3939.5   80.01  4039.5   77.94  4079.5   75.63  4149.5    73.9
  4419.5   72.56  4729.5   72.93  4789.5    72.1  4959.5   73.13  4973.9    70.1
  4975.4    67.1  5024.6    67.1  5026.1    70.1    5030   73.14    5050   73.52
    5250   72.62    5340   73.31    5350   73.52    5360   76.34    5380   74.91
    5480    74.9    5500   78.93    5510   79.38    5610   80.57    5650   82.09
    5770   80.55    5920   80.22    6000   81.07    6150    79.2  6301.8   78.64
#Mann= 3 ,-1,0
  3549.5     .15       0  4973.9    .045       0  5026.1     .15       0
Bank Sta=4973.9,5026.1
XS Rating Curve= 0 ,0
Exp/Cntr=0.3,0.1

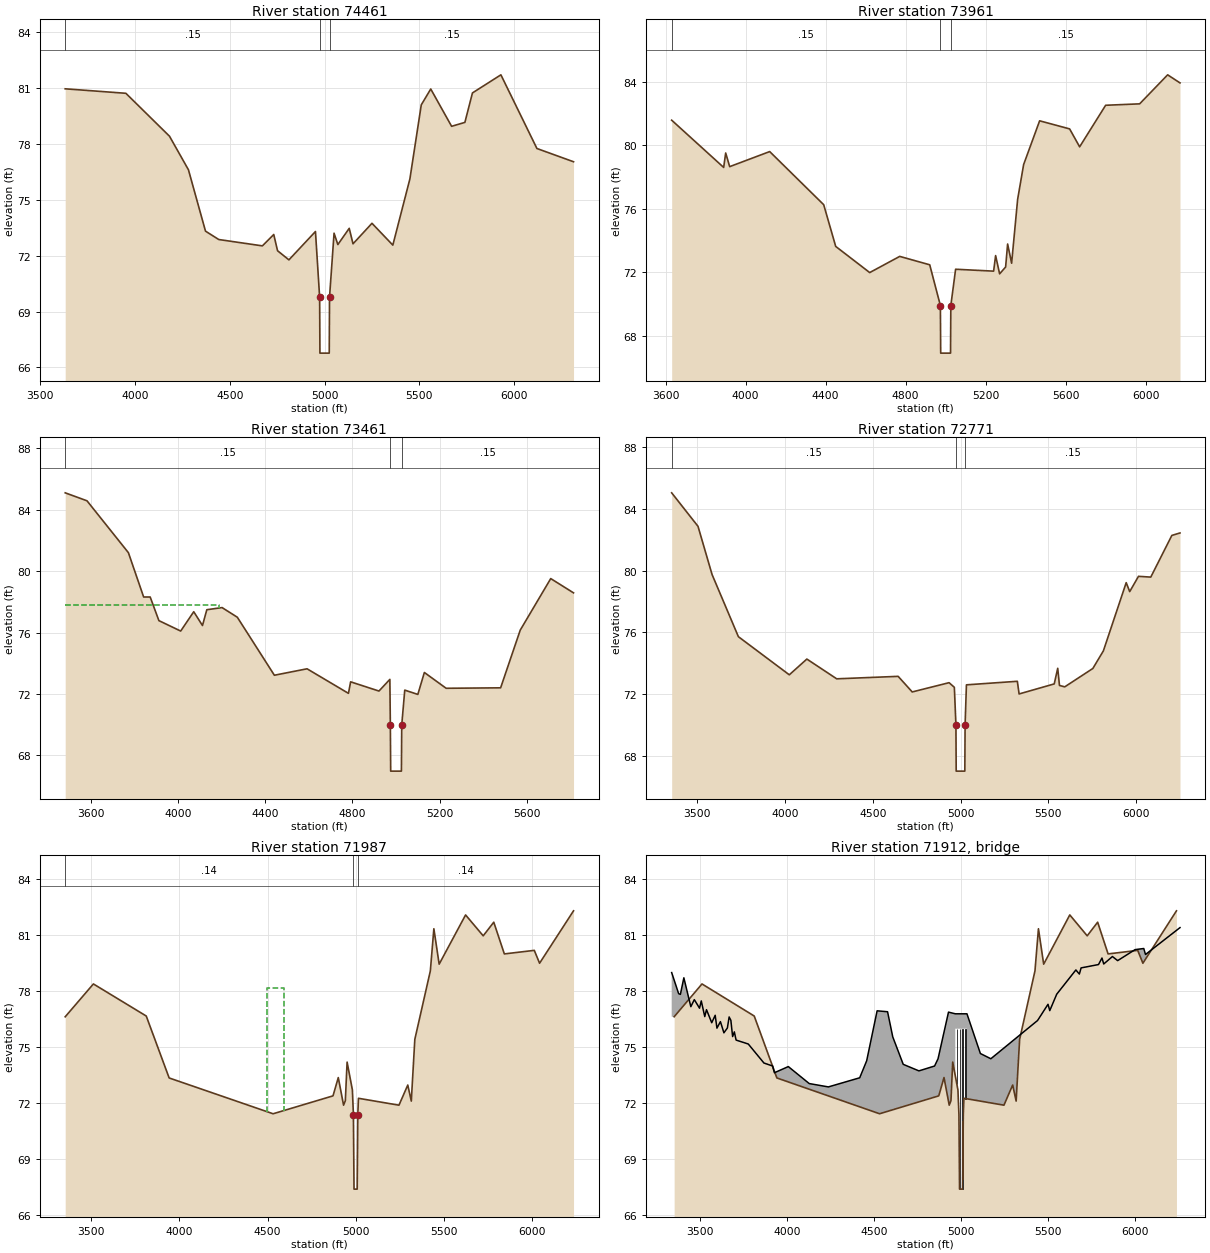
Type RM Length L Ch R = 1 ,74461   ,500,500,500
BEGIN DESCRIPTION:
Indian Field Swamp 149.0
END DESCRIPTION:
XS GIS Cut Line= 3
      2142164.22       509349.26      2141794.12       508032.17
      2141512.41       506749.65
#Sta/Elev= 30
  3631.9   80.94  3951.9    80.7  4181.9    78.4  4281.9    76.6  4371.9   73.31
  4441.9   72.86  4671.9   72.52  4731.9   73.13  4751.9   72.26  4811.9   71.77
  4951.9   73.29  4973.9   69.77  4975.4   66.77  5024.6   66.77  5026.1   69.77
    5050    73.2    5070   72.59    5130   73.46    5150   72.63    5250   73.73
    5360   72.56    5450   76.11    5510   80.08    5560   80.93    5670   78.93
    5740   79.14    5780   80.72    5930   81.69    6120   77.74  6313.1   77.03
#Mann= 3 ,-1,0
  3631.9     .15       0  4973.9    .045       0  5026.1     .15       0
Bank Sta=4973.9,5026.1
XS Rating Curve= 0 ,0
Exp/Cntr=0.3,0.1

Type RM Length L Ch R = 1 ,73961   ,500,500,500
BEGIN DESCRIPTION:
Indian Field Swamp 148.0
END DESCRIPTION:
XS GIS Cut Line= 3
      2142674.97       509223.43      2142278.68       507912.63
      2141950.75       506787.76
#Sta/Elev= 30
  3630.6   81.59  3890.6   78.61  3900.6   79.52  3920.6   78.66  4120.6   79.61
  4390.6   76.26  4450.6   73.63  4620.6   71.98  4770.6      73  4920.6   72.47
  4973.9    69.9  4975.4    66.9  5024.6    66.9  5026.1    69.9    5050   72.19
    5240   72.07    5250   73.05    5270    71.9    5300   72.33    5310   73.78
    5330   72.57    5360   76.59    5390   78.79    5470   81.55    5620   81.04
    5670   79.91    5800   82.53    5970   82.62    6110   84.45  6171.7   83.94
#Mann= 3 ,-1,0
  3630.6     .15       0  4973.9    .045       0  5026.1     .15       0
Bank Sta=4973.9,5026.1
XS Rating Curve= 0 ,0
Exp/Cntr=0.3,0.1

Type RM Length L Ch R = 1 ,73461   ,690,690,690
BEGIN DESCRIPTION:
Indian Field Swamp 147.0
END DESCRIPTION:
XS GIS Cut Line= 3
      2143118.76       509201.99      2142744.33       507730.48
      2142519.95        506947.4
#Sta/Elev= 30
  3481.6   85.11  3581.6   84.59  3771.6   81.21  3841.6   78.32  3871.6   78.32
  3911.6   76.78  4011.6    76.1  4071.6   77.36  4111.6   76.46  4131.6   77.49
  4201.6   77.63  4271.6      77  4441.6   73.22  4591.6   73.64  4781.6   72.04
  4791.6   72.79  4921.6   72.19  4971.6   72.95  4973.9   69.97  4975.4   66.97
  5024.6   66.97  5026.1   69.97    5040   72.25    5100   71.97    5130    73.4
    5230   72.37    5480    72.4    5570   76.16    5710   79.52  5814.6   78.59
#Mann= 3 ,-1,0
  3481.6     .15       0  4973.9    .045       0  5026.1     .15       0
#XS Ineff= 2 , 0
       0  4187.8   77.78  5812.2       0   77.78
Permanent Ineff=
       F       F
Bank Sta=4973.9,5026.1
XS Rating Curve= 0 ,0
Exp/Cntr=0.3,0.1

Type RM Length L Ch R = 1 ,72771   ,784,784,784
BEGIN DESCRIPTION:
Indian Field Swamp 146.0
END DESCRIPTION:
XS GIS Cut Line= 3
      2143826.11       509048.15      2143383.95       507470.09
      2142823.61        506345.6
#Sta/Elev= 30
  3354.9   85.04  3504.9   82.87  3584.9   79.75  3734.9   75.72  4024.9   73.25
  4124.9   74.27  4294.9   72.99  4644.9   73.15  4724.9   72.14  4934.9   72.74
  4964.9   72.44  4973.9   70.01  4975.4   67.01  5024.6   67.01  5026.1   70.01
  5033.7    72.6  5323.7   72.83  5333.7   72.01  5533.7   72.66  5553.7   73.67
  5563.7   72.56  5593.7   72.47  5753.7   73.66  5813.7    74.8  5943.7   79.22
  5963.7   78.64  6013.7   79.63  6083.7   79.58  6203.7   82.28  6250.1   82.44
#Mann= 3 ,-1,0
  3354.9     .15       0  4973.9    .045       0  5026.1     .15       0
Bank Sta=4973.9,5026.1
XS Rating Curve= 0 ,0
Exp/Cntr=0.5,0.3

Type RM Length L Ch R = 1 ,71987   ,144,144,144
BEGIN DESCRIPTION:
Gavins Road - US
END DESCRIPTION:
XS GIS Cut Line= 4
      2145180.31       508000.94      2143933.27       506913.81
      2143639.38       506660.26      2142861.95       506335.14
#Sta/Elev= 30
  3351.7   76.61  3511.7   78.37  3811.7   76.65  3941.7   73.33  4531.7   71.41
  4871.7   72.37  4901.7   73.35  4931.7   71.87  4941.7   72.11  4951.7   74.18
  4981.7   72.69  4987.5   71.37    4991   67.37    5009   67.37  5012.5   71.37
  5016.1   72.24  5246.1   71.87  5296.1   72.95  5316.1   72.09  5336.1    75.4
  5424.2   79.07  5444.2   81.33  5474.2   79.43  5624.2   82.07  5724.2   80.95
  5784.2   81.68  5844.2   79.98  6014.2   80.17  6044.2   79.48  6236.9   82.29
#Mann= 3 ,-1,0
  3351.7     .14       0  4987.5    .045       0  5012.5     .14       0
#XS Ineff= 1 ,-1
  4494.8  4590.8   78.17
Permanent Ineff=
       F
Bank Sta=4987.5,5012.5
XS Rating Curve= 0 ,0
Exp/Cntr=0.5,0.3

Type RM Length L Ch R = 3 ,71912   ,,,
BEGIN DESCRIPTION:
Gavins Road - TOR
Structure ID: LDS_IFS_04
Approximate Survey Structure
END DESCRIPTION:
Bridge Culvert--1,0,-1,-1, 0
Deck Dist Width WeirC Skew NumUp NumDn MinLoCord MaxHiCord MaxSubmerge Is_Ogee
62.5,25,3,0, 60, 60, , , 0.95, 0, 1,1,,
  3337.5  3377.5  3387.5  3407.5  3447.5  3467.5  3497.5  3507.5  3527.5  3537.5
  3567.5  3587.5  3597.5  3617.5  3637.5  3657.5  3667.5  3677.5  3687.5  3697.5
  3707.5  3777.5  3867.5  3917.5  3927.5  4007.5  4127.5  4237.5  4417.5  4457.5
  4517.5  4577.5  4607.5  4667.5  4757.5  4847.5  4867.5  4927.5  4966.5  4966.5
  5033.5  5033.5  5110.7  5170.7  5439.1  5499.1  5509.1  5549.1  5659.1  5679.1
  5689.1  5789.1  5809.1  5819.1  5869.1  5899.1  5999.1  6049.1  6059.1  6257.2
   78.98   77.85   77.81    78.7   77.15   77.53   77.07   77.46   76.62   76.99
   76.29   76.69      76   76.35   75.75   76.01    76.6   76.42   75.55    75.8
   75.36   75.15   74.13   73.97   73.61   73.94   73.03   72.85   73.34   74.25
   76.93   76.88   75.53   74.06   73.71   73.97   74.36   76.86   76.77   76.77
   76.77   76.77   74.64   74.36   76.41   77.28   76.94   77.82   79.12    78.9
   79.23   79.41   79.76   79.44   79.84   79.62   80.21   80.27   79.95   81.39
   47.37   47.37   47.37   47.37   47.37   47.37   47.37   47.37   47.37   47.37
   47.37   47.37   47.37   47.37   47.37   47.37   47.37   47.37   47.37   47.37
   47.37   47.37   47.37   47.37   47.37   47.37   47.37   47.37   47.37   47.37
   47.37   47.37   47.37   47.37   47.37   47.37   47.37   47.37   47.37   75.97
   75.97   47.37   47.37   47.37   47.37   47.37   47.37   47.37   47.37   47.37
   47.37   47.37   47.37   47.37   47.37   47.37   47.37   47.37   47.37   47.37
  3337.5  3377.5  3387.5  3407.5  3447.5  3467.5  3497.5  3507.5  3527.5  3537.5
  3567.5  3587.5  3597.5  3617.5  3637.5  3657.5  3667.5  3677.5  3687.5  3697.5
  3707.5  3777.5  3867.5  3917.5  3927.5  4007.5  4127.5  4237.5  4417.5  4457.5
  4517.5  4577.5  4607.5  4667.5  4757.5  4847.5  4867.5  4927.5  4966.5  4966.5
  5033.5  5033.5  5110.7  5170.7  5439.1  5499.1  5509.1  5549.1  5659.1  5679.1
  5689.1  5789.1  5809.1  5819.1  5869.1  5899.1  5999.1  6049.1  6059.1  6257.2
   78.98   77.85   77.81    78.7   77.15   77.53   77.07   77.46   76.62   76.99
   76.29   76.69      76   76.35   75.75   76.01    76.6   76.42   75.55    75.8
   75.36   75.15   74.13   73.97   73.61   73.94   73.03   72.85   73.34   74.25
   76.93   76.88   75.53   74.06   73.71   73.97   74.36   76.86   76.77   76.77
   76.77   76.77   74.64   74.36   76.41   77.28   76.94   77.82   79.12    78.9
   79.23   79.41   79.76   79.44   79.84   79.62   80.21   80.27   79.95   81.39
   47.37   47.37   47.37   47.37   47.37   47.37   47.37   47.37   47.37   47.37
   47.37   47.37   47.37   47.37   47.37   47.37   47.37   47.37   47.37   47.37
   47.37   47.37   47.37   47.37   47.37   47.37   47.37   47.37   47.37   47.37
   47.37   47.37   47.37   47.37   47.37   47.37   47.37   47.37   47.37   75.97
   75.97   47.37   47.37   47.37   47.37   47.37   47.37   47.37   47.37   47.37
   47.37   47.37   47.37   47.37   47.37   47.37   47.37   47.37   47.37   47.37
Pier Skew, UpSta & Num, DnSta & Num=  ,4974.9, 2 ,4974.9, 2 , 0 , 0 , 0 ,0,0
     1.1     1.1
   72.82   75.97
     1.1     1.1
   72.49   75.97
Pier Skew, UpSta & Num, DnSta & Num=  ,4991.6, 2 ,4991.6, 2 , 0 , 0 , 0 ,0,0
     1.1     1.1
   67.37   75.97
     1.1     1.1
   67.12   75.97
Pier Skew, UpSta & Num, DnSta & Num=  ,5008.4, 2 ,5008.4, 2 , 0 , 0 , 0 ,0,0
     1.1     1.1
   67.37   75.97
     1.1     1.1
   67.12   75.97
Pier Skew, UpSta & Num, DnSta & Num=  ,5025.1, 2 ,5025.1, 2 , 0 , 0 , 0 ,0,0
     1.1     1.1
      72   75.97
     1.1     1.1
   72.04   75.97
Abutment Skew #Up #Dn= , 2 , 2
  4966.5    4968
   75.97    73.1
  4966.5    4968
   75.97    72.3
Abutment Skew #Up #Dn= , 2 , 2
    5032  5033.5
   72.05   75.97
    5032  5033.5
    72.5   75.97
BR Coef= 1 , 1 , 0 ,1.25, 0 ,,,0.8,0,2,0,
WSPro=,,,, 1 ,,,, 0 ,,,, 0 ,,,,-1 ,-1 ,-1 , 0 , 0 , 0 , 0 , 0
BC Design=,, 0 ,, 0 ,,,,,,
BC HTab HWMax=82.29
BC Use User HTab Curves=0
BC User HTab FreeFlow(D)= 0