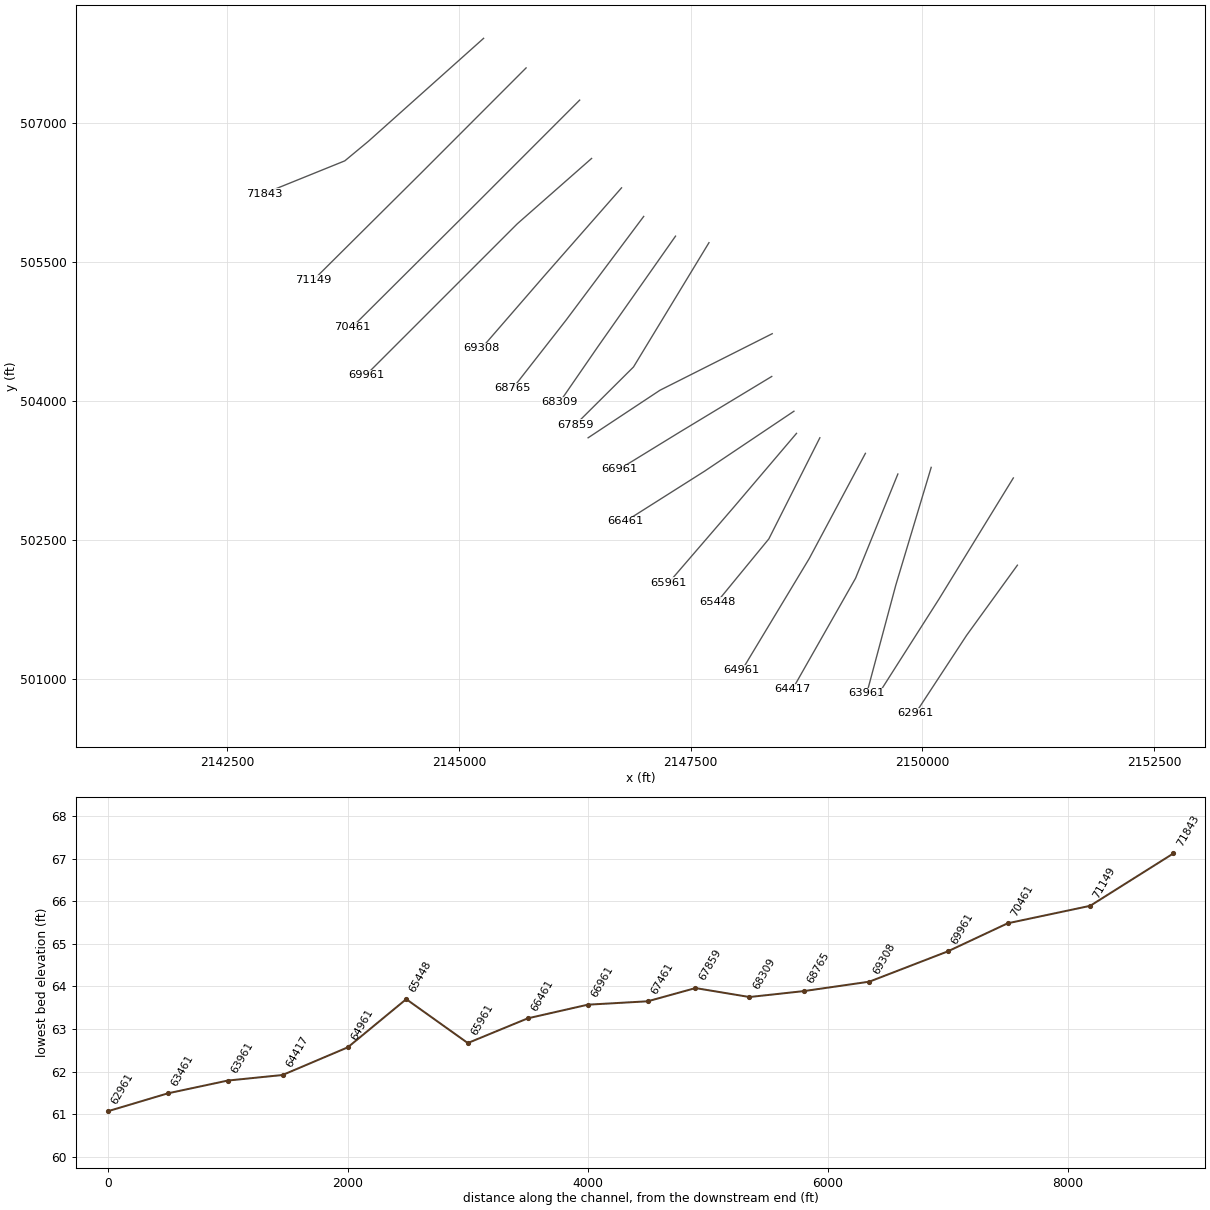
HEC-RAS study IndianFieldsSwamp.prj: S-18-19 over Indian Fields Swamp

--- IndianFieldsSwamp.g02 (geometry) --- (continued)

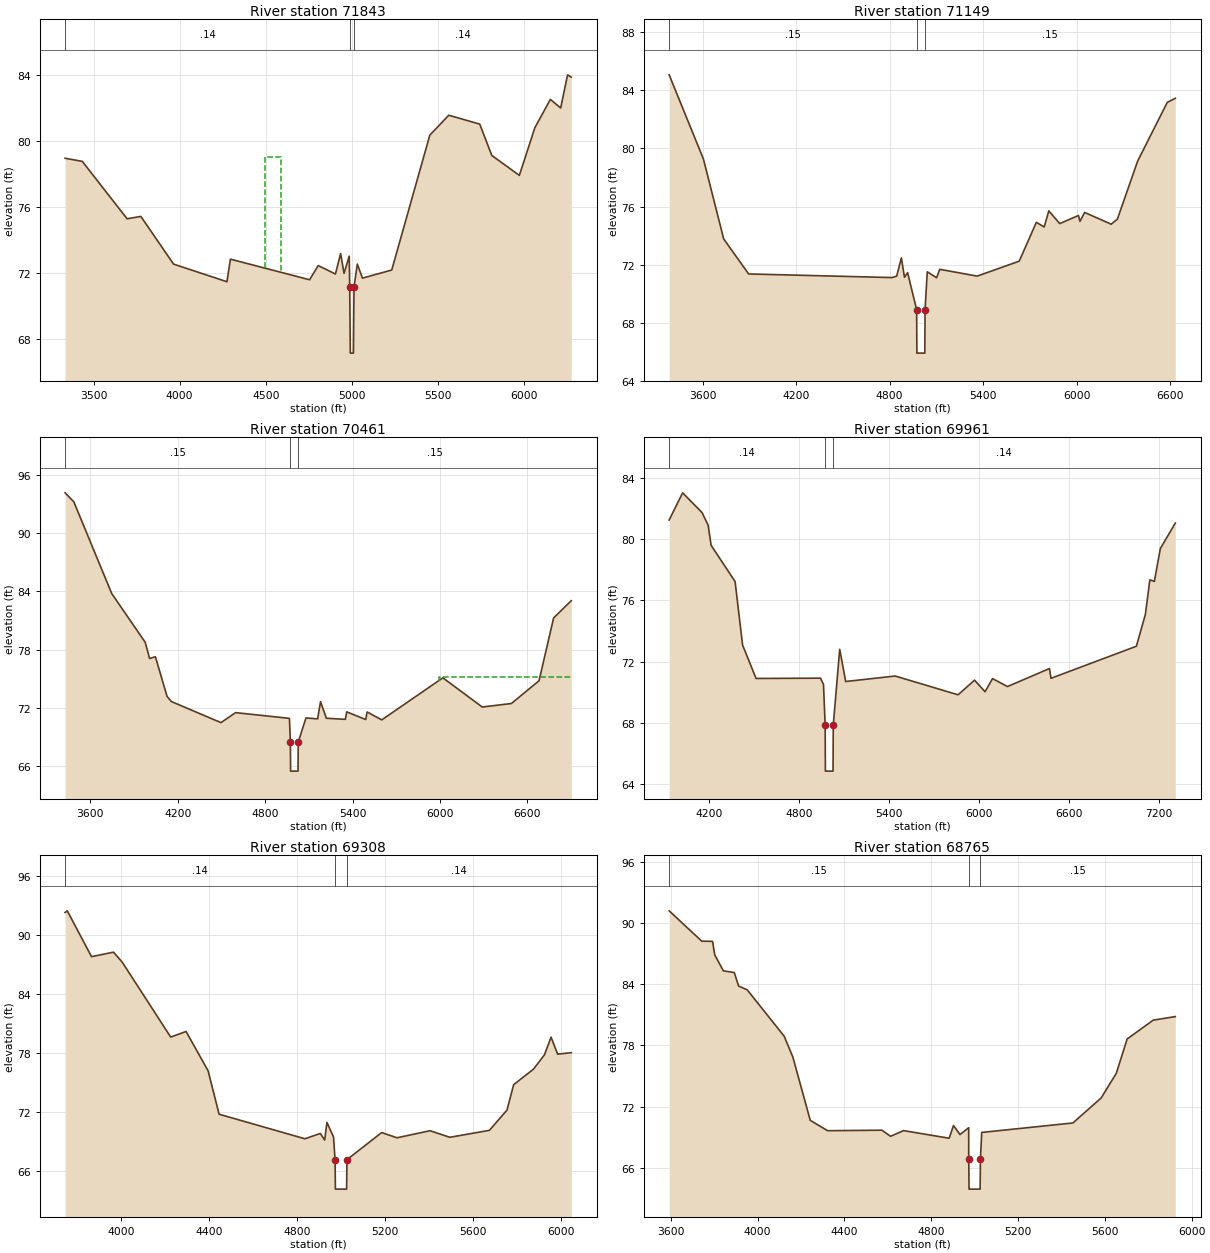
Type RM Length L Ch R = 1 ,71843   ,694,694,694
BEGIN DESCRIPTION:
Gavins Road - DS
END DESCRIPTION:
XS GIS Cut Line= 4
      2145266.01       507913.06      2144023.39       506801.78
       2143768.7       506590.31      2142896.14       506237.18
#Sta/Elev= 30
  3334.6   78.94  3434.6   78.75  3694.6   75.27  3774.6   75.41  3964.6   72.52
  4274.6   71.45  4294.6   72.82  4754.6   71.57  4804.6   72.43  4904.6   71.92
  4934.6   73.16  4954.6   71.96  4984.6      73  4987.5   71.12    4991   67.12
    5009   67.12  5012.5   71.12  5031.6   72.52  5061.6   71.67  5231.6   72.16
  5452.7   80.34  5562.7   81.55  5742.7   81.01  5812.7   79.11  5972.7    77.9
  6062.7   80.79  6152.7   82.51  6212.7   81.99  6252.7      84    6274   83.86
#Mann= 3 ,-1,0
  3334.6     .14       0  4987.5    .045       0  5012.5     .14       0
#XS Ineff= 1 ,-1
  4496.8  4590.5      79
Permanent Ineff=
       F
Bank Sta=4987.5,5012.5
XS Rating Curve= 0 ,0
Exp/Cntr=0.5,0.3

Type RM Length L Ch R = 1 ,71149   ,688,688,688
BEGIN DESCRIPTION:
Indian Field Swamp 142.0
END DESCRIPTION:
XS GIS Cut Line= 3
      2145724.45       507593.74      2144582.68       506449.83
      2143425.74       505299.38
#Sta/Elev= 30
    3385   85.08    3605   79.27    3735   73.76    3895   71.35    4815    71.1
    4845    71.2    4875   72.46    4895   71.12    4915   71.44    4973   68.89
  4974.5   65.89  5025.5   65.89    5027   68.89  5041.2    71.5  5101.2   71.09
  5121.2   71.67  5361.2    71.2  5631.2   72.23  5741.2   74.91  5791.2   74.59
  5821.2    75.7  5891.2   74.82  6011.2   75.38  6021.2   74.98  6051.2   75.59
  6221.2   74.78  6261.2   75.13  6391.2   79.13  6581.2   83.18  6632.8   83.46
#Mann= 3 ,-1,0
    3385     .15       0    4973    .045       0    5027     .15       0
Bank Sta=4973,5027
XS Rating Curve= 0 ,0
Exp/Cntr=0.3,0.1

Type RM Length L Ch R = 1 ,70461   ,500,500,500
BEGIN DESCRIPTION:
Indian Field Swamp 141.0
END DESCRIPTION:
XS GIS Cut Line= 3
      2146302.38       507246.12       2145190.5       506132.88
       2143843.7        504791.4
#Sta/Elev= 30
  3426.6   94.17  3486.6   93.24  3746.6   83.79  3976.6   78.76  4006.6   77.09
  4046.6   77.27  4126.6   73.18  4156.6   72.65  4496.6   70.48  4596.6   71.51
  4966.6   70.92    4973   68.48  4974.5   65.48  5025.5   65.48    5027   68.48
    5080   70.96    5160   70.87    5180   72.64    5220   70.93    5350   70.82
    5360   71.59    5490    70.8    5500   71.58    5600   70.76    6020    75.1
    6290   72.09    6490   72.45    6680    74.8    6780   81.27  6900.9   83.05
#Mann= 3 ,-1,0
  3426.6     .15       0    4973    .045       0    5027     .15       0
#XS Ineff= 2 , 0
       0  4008.9   75.19  5991.1       0   75.19
Permanent Ineff=
       F       F
Bank Sta=4973,5027
XS Rating Curve= 0 ,0
Exp/Cntr=0.3,0.1

Type RM Length L Ch R = 1 ,69961   ,653,653,653
BEGIN DESCRIPTION:
Indian Field Swamp 140.0
END DESCRIPTION:
XS GIS Cut Line= 3
      2146430.94       506616.29      2145629.16       505910.46
      2143996.21       504276.86
#Sta/Elev= 30
  3931.8   81.27  4021.8   83.05  4151.8   81.75  4191.8   80.93  4211.8   79.61
  4371.8   77.24  4421.8   73.08  4511.8   70.89  4941.8   70.91  4961.8    70.5
    4973   67.82  4974.5   64.82  5025.5   64.82    5027   67.82    5070    72.8
    5110   70.69    5440   71.05    5860   69.82    5970   70.78    6040   70.02
    6090   70.88    6190   70.36    6470   71.54    6480    70.9    7050      73
    7110   75.08    7140   77.35    7170   77.25    7210    79.4  7309.8   81.07
#Mann= 3 ,-1,0
  3931.8     .14       0    4973    .045       0    5027     .14       0
Bank Sta=4973,5027
XS Rating Curve= 0 ,0
Exp/Cntr=0.3,0.1

Type RM Length L Ch R = 1 ,69308   ,543,543,543
BEGIN DESCRIPTION:
Indian Field Swamp 139.0
END DESCRIPTION:
XS GIS Cut Line= 3
      2146754.28       506298.83      2145917.67       505344.97
      2145242.11       504565.04
#Sta/Elev= 30
  3745.9   92.29  3755.9   92.46  3865.9   87.79  3965.9   88.25  4005.9   87.22
  4225.9    79.6  4295.9   80.17  4395.9   76.16  4445.9   71.74  4835.9   69.24
  4905.9   69.78  4925.9   69.11  4935.9   70.91  4965.9   69.43    4973   67.11
  4974.5   64.11  5025.5   64.11    5027   67.11  5184.7   69.87  5254.7   69.34
  5404.7   70.06  5494.7   69.39  5674.7    70.1  5754.7   72.17  5784.7   74.75
  5874.7   76.33  5924.7   77.79  5954.7   79.59  5984.7   77.86  6046.5   78.01
#Mann= 3 ,-1,0
  3745.9     .14       0    4973    .045       0    5027     .14       0
Bank Sta=4973,5027
XS Rating Curve= 0 ,0
Exp/Cntr=0.3,0.1

Type RM Length L Ch R = 1 ,68765   ,456,456,456
BEGIN DESCRIPTION:
Indian Field Swamp 138.0
END DESCRIPTION:
XS GIS Cut Line= 3
      2146993.26       505990.29      2146154.62       504869.21
      2145581.02       504134.82
#Sta/Elev= 30
  3592.8   91.23  3742.8   88.25  3792.8   88.23  3802.8    86.9  3842.8   85.33
  3892.8   85.17  3912.8   83.84  3952.8   83.46  4122.8   78.91  4162.8   76.86
  4242.8   70.65  4322.8   69.63  4572.8   69.68  4612.8   69.08  4672.8   69.64
  4882.8   68.89  4902.8   70.14  4932.8   69.25  4972.8   69.92    4973   66.89
  4974.5   63.89  5025.5   63.89    5027   66.89  5032.9   69.46  5452.9   70.39
  5582.9   72.84  5652.9   75.27  5702.9   78.64  5822.9   80.49  5924.7   80.84
#Mann= 3 ,-1,0
  3592.8     .15       0    4973    .045       0    5027     .15       0
Bank Sta=4973,5027
XS Rating Curve= 0 ,0
Exp/Cntr=0.3,0.1

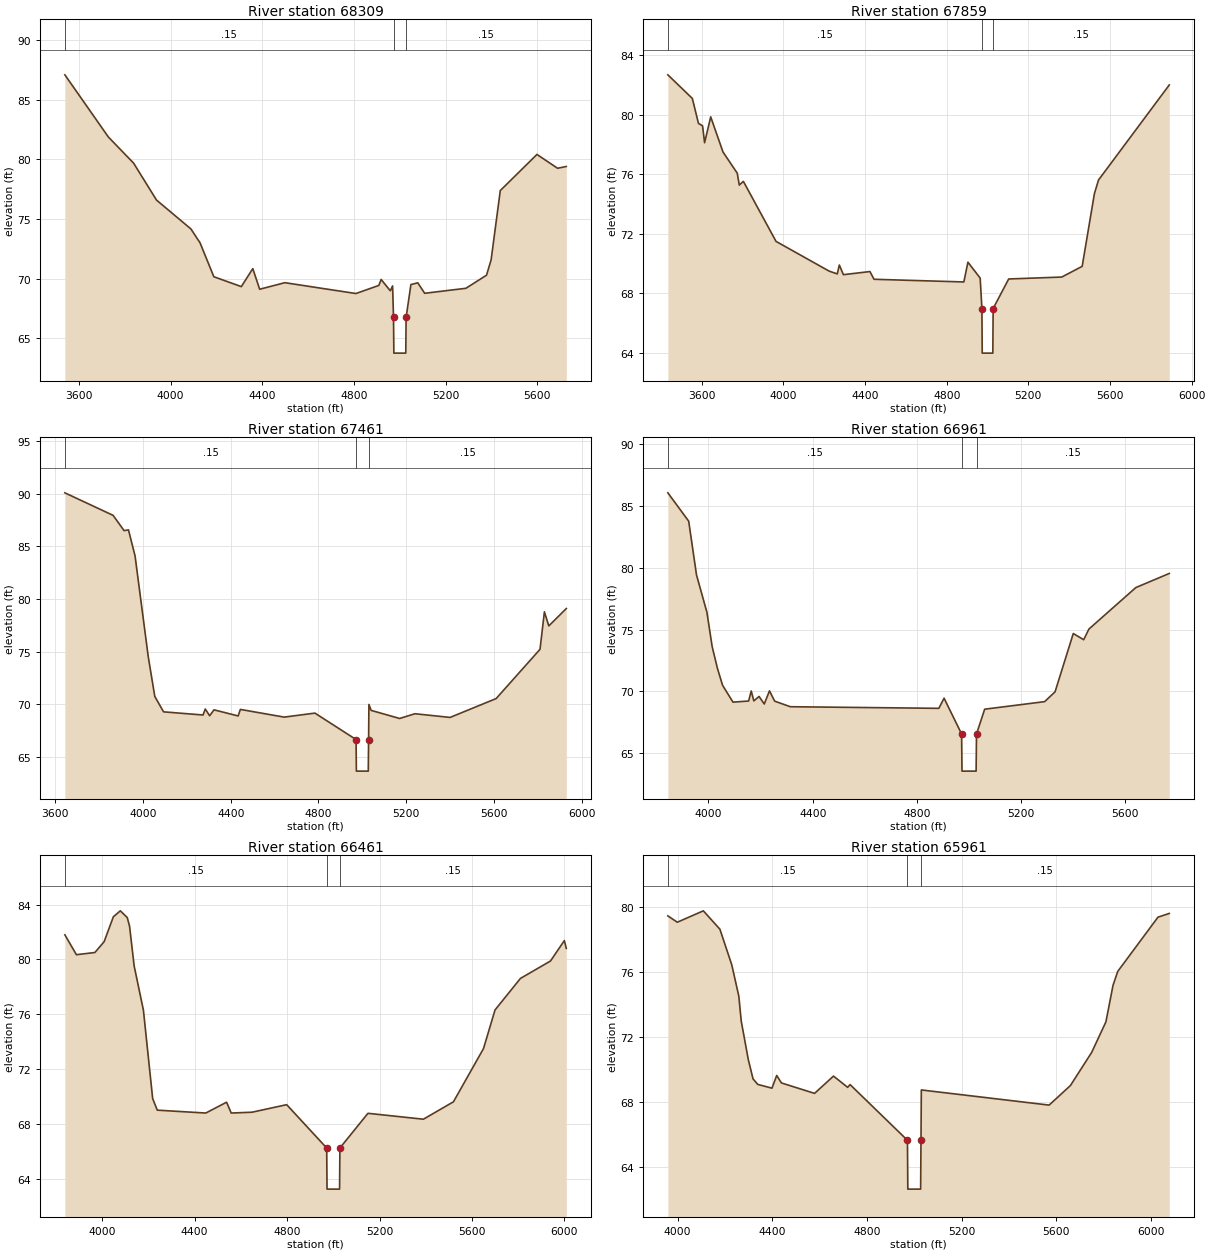
Type RM Length L Ch R = 1 ,68309   ,450,450,450
BEGIN DESCRIPTION:
Indian Field Swamp 137.0
END DESCRIPTION:
XS GIS Cut Line= 3
      2147336.53       505777.36       2146497.9       504582.42
      2146085.07       503982.73
#Sta/Elev= 30
  3538.5    87.1  3728.5   81.88  3838.5   79.69  3938.5   76.59  4088.5   74.17
  4128.5      73  4188.5   70.16  4308.5   69.33  4358.5   70.84  4388.5   69.11
  4498.5   69.66  4808.5   68.75  4908.5   69.43  4918.5   69.93  4958.5   68.98
  4968.5   69.39  4972.5   66.75    4974   63.75    5026   63.75  5027.5   66.75
  5048.4    69.5  5078.4   69.65  5108.4   68.77  5288.4   69.19  5378.4   70.29
  5398.4   71.58  5438.4   77.39  5598.4   80.42  5688.4   79.26  5726.4   79.41
#Mann= 3 ,-1,0
  3538.5     .15       0  4972.5    .045       0  5027.5     .15       0
Bank Sta=4972.5,5027.5
XS Rating Curve= 0 ,0
Exp/Cntr=0.3,0.1

Type RM Length L Ch R = 1 ,67859   ,398,398,398
BEGIN DESCRIPTION:
Indian Field Swamp 136.0
END DESCRIPTION:
XS GIS Cut Line= 3
      2147697.45       505706.82      2146883.16       504364.84
      2146254.59       503739.45
#Sta/Elev= 30
    3434   82.69    3554    81.1    3584   79.42    3604   79.26    3614   78.12
    3644   79.86    3704    77.5    3774   76.07    3784   75.27    3804   75.52
    3964   71.48    4224   69.48    4264   69.29    4274   69.89    4294   69.24
    4424   69.45    4444   68.93    4884   68.75    4904   70.08    4964   69.01
  4972.5   66.96    4974   63.96    5026   63.96  5027.5   66.96  5103.7   68.95
  5363.7   69.08  5463.7    69.8  5523.7    74.7  5543.7   75.61  5890.4   82.01
#Mann= 3 ,-1,0
    3434     .15       0  4972.5    .045       0  5027.5     .15       0
Bank Sta=4972.5,5027.5
XS Rating Curve= 0 ,0
Exp/Cntr=0.3,0.1

Type RM Length L Ch R = 1 ,67461   ,500,500,500
BEGIN DESCRIPTION:
Indian Field Swamp 135.0
END DESCRIPTION:
XS GIS Cut Line= 3
       2148379.8       504724.22       2147168.9       504113.72
      2146393.64       503600.39
#Sta/Elev= 30
  3643.9   90.08  3863.9   87.94  3913.9   86.49  3933.9   86.56  3963.9   84.09
  4023.9   74.54  4053.9   70.74  4093.9   69.28  4273.9   68.98  4283.9   69.55
  4303.9   68.91  4323.9   69.47  4433.9   68.89  4443.9   69.51  4643.9   68.78
  4783.9   69.16  4971.4   66.65  4972.9   63.65  5027.1   63.65  5028.6   66.65
    5030   69.98    5040   69.42    5170   68.65    5240    69.1    5400   68.75
    5610   70.54    5810   75.22    5830   78.78    5850   77.44  5929.8   79.09
#Mann= 3 ,-1,0
  3643.9     .15       0  4971.4    .045       0  5028.6     .15       0
Bank Sta=4971.4,5028.6
XS Rating Curve= 0 ,0
Exp/Cntr=0.3,0.1

Type RM Length L Ch R = 1 ,66961   ,500,500,500
BEGIN DESCRIPTION:
Indian Field Swamp 134.0
END DESCRIPTION:
XS GIS Cut Line= 3
      2148374.84       504262.53      2147385.85       503664.19
      2146731.11       503262.01
#Sta/Elev= 30
  3844.1   86.04  3924.1   83.75  3954.1   79.41  3994.1   76.39  4014.1   73.63
  4034.1   71.89  4054.1    70.5  4094.1   69.14  4154.1   69.23  4164.1   70.04
  4174.1   69.24  4194.1    69.6  4214.1   68.99  4234.1   70.05  4254.1   69.22
  4314.1   68.77  4884.1   68.64  4904.1   69.46  4971.4   66.57  4972.9   63.57
  5027.1   63.57  5028.6   66.57    5060   68.57    5290   69.18    5330   69.97
    5400   74.68    5440   74.18    5460   75.04    5640   78.39  5768.4   79.53
#Mann= 3 ,-1,0
  3844.1     .15       0  4971.4    .045       0  5028.6     .15       0
Bank Sta=4971.4,5028.6
XS Rating Curve= 0 ,0
Exp/Cntr=0.3,0.1

Type RM Length L Ch R = 1 ,66461   ,500,500,500
BEGIN DESCRIPTION:
Indian Field Swamp 133.0
END DESCRIPTION:
XS GIS Cut Line= 3
      2148614.11       503887.19      2147649.57       503239.55
       2146797.8       502699.77
#Sta/Elev= 30
  3838.2    81.8  3888.2   80.35  3968.2   80.51  4008.2    81.3  4048.2   83.12
  4078.2   83.55  4108.2   83.06  4118.2   82.43  4138.2   79.52  4178.2    76.3
  4218.2   69.86  4238.2   69.01  4448.2    68.8  4538.2   69.59  4558.2    68.8
  4648.2   68.86  4798.2   69.41  4971.4   66.25  4972.9   63.25  5027.1   63.25
  5028.6   66.25    5150   68.78    5390   68.35    5520   69.62    5650    73.5
    5700   76.32    5810   78.62    5940   79.89    6000   81.38  6008.4   80.81
#Mann= 3 ,-1,0
  3838.2     .15       0  4971.4    .045       0  5028.6     .15       0
Bank Sta=4971.4,5028.6
XS Rating Curve= 0 ,0
Exp/Cntr=0.3,0.1

Type RM Length L Ch R = 1 ,65961   ,513,513,513
BEGIN DESCRIPTION:
Indian Field Swamp 132.0
END DESCRIPTION:
XS GIS Cut Line= 3
      2148641.71       503647.94      2147967.78        502854.4
      2147264.72       502037.48
#Sta/Elev= 30
  3958.9   79.45  3998.9   79.06  4108.9   79.76  4178.9   78.63  4228.9   76.45
  4258.9   74.51  4268.9      73  4298.9   70.62  4318.9   69.44  4338.9    69.1
  4398.9   68.87  4418.9   69.65  4438.9   69.19  4578.9   68.55  4658.9   69.61
  4718.9   68.92  4728.9   69.09  4971.4   65.67  4972.9   62.67  5027.1   62.67
  5028.6   65.67    5030   68.76    5570   67.83    5660   69.03    5750   71.07
    5810   72.94    5840   75.18    5860   76.04    6030   79.37  6077.8    79.6
#Mann= 3 ,-1,0
  3958.9     .15       0  4971.4    .045       0  5028.6     .15       0
Bank Sta=4971.4,5028.6
XS Rating Curve= 0 ,0
Exp/Cntr=0.3,0.1

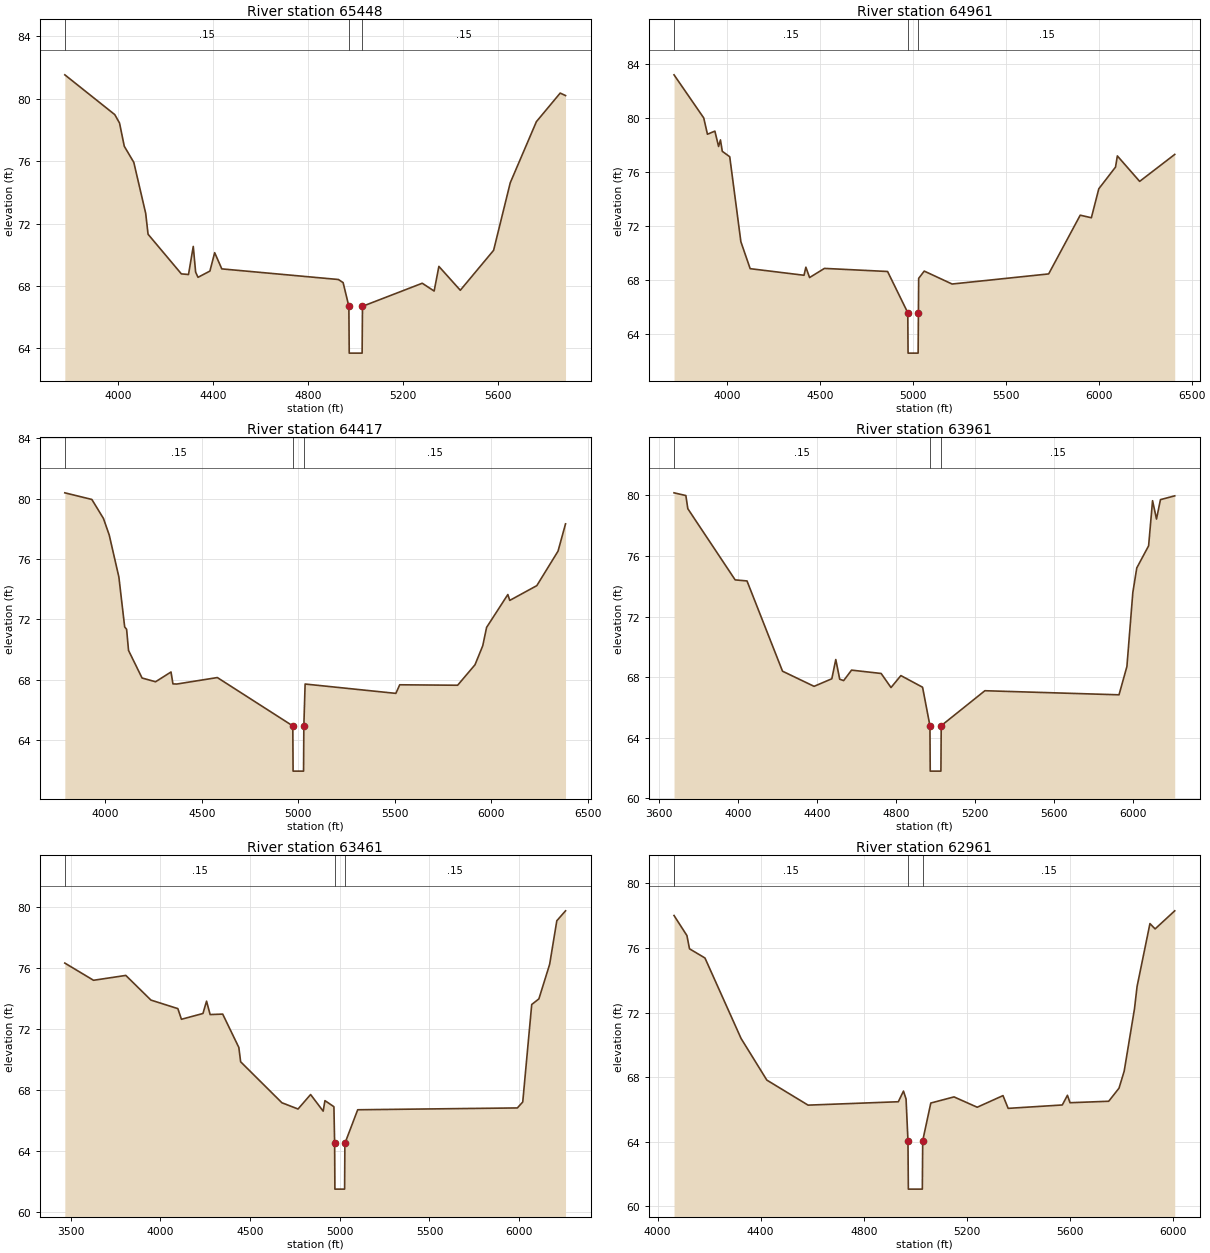
Type RM Length L Ch R = 1 ,65448   ,487,487,487
BEGIN DESCRIPTION:
Indian Field Swamp 131.0
END DESCRIPTION:
XS GIS Cut Line= 3
      2148893.83       503600.59       2148343.4       502508.83
      2147783.87       501826.47
#Sta/Elev= 30
  3777.2   81.54  3987.2   78.99  4007.2   78.45  4027.2   76.96  4067.2   75.93
  4117.2   72.66  4127.2   71.32  4267.2   68.78  4297.2   68.74  4317.2   70.54
  4327.2   68.89  4337.2   68.56  4387.2   68.96  4407.2   70.14  4437.2    69.1
  4927.2   68.42  4947.2   68.22  4971.4    66.7  4972.9    63.7  5027.1    63.7
  5028.6    66.7  5279.9   68.18  5329.9   67.68  5349.9   69.26  5439.9   67.73
  5579.9   70.29  5649.9   74.62  5759.9   78.54  5859.9   80.37  5882.3   80.21
#Mann= 3 ,-1,0
  3777.2     .15       0  4971.4    .045       0  5028.6     .15       0
Bank Sta=4971.4,5028.6
XS Rating Curve= 0 ,0
Exp/Cntr=0.3,0.1

Type RM Length L Ch R = 1 ,64961   ,544,544,544
BEGIN DESCRIPTION:
Indian Field Swamp 130.0
END DESCRIPTION:
XS GIS Cut Line= 3
      2149385.13       503432.29      2148779.12       502296.44
      2148052.26       501089.52
#Sta/Elev= 30
  3712.6   83.23  3872.6   80.03  3892.6   78.82  3932.6   79.05  3952.6   77.91
  3962.6    78.4  3972.6   77.55  4012.6   77.15  4072.6   70.84  4122.6   68.84
  4412.6   68.35  4422.6   68.95  4442.6   68.18  4522.6   68.86  4862.6   68.63
  4971.4   65.57  4972.9   62.57  5027.1   62.57  5028.6   65.57    5030   68.12
    5060   68.66    5210    67.7    5730   68.45    5900   72.81    5960   72.62
    6000   74.77    6090   76.38    6100   77.21    6220   75.32  6408.9   77.32
#Mann= 3 ,-1,0
  3712.6     .15       0  4971.4    .045       0  5028.6     .15       0
Bank Sta=4971.4,5028.6
XS Rating Curve= 0 ,0
Exp/Cntr=0.3,0.1

Type RM Length L Ch R = 1 ,64417   ,456,456,456
BEGIN DESCRIPTION:
Indian Field Swamp 129.0
END DESCRIPTION:
XS GIS Cut Line= 3
       2149735.4       503209.38      2149278.91       502083.85
      2148598.14       500884.81
#Sta/Elev= 30
  3790.6   80.39  3930.6   79.95  3990.6   78.69  4020.6   77.59  4070.6    74.8
  4100.6   71.49  4110.6   71.33  4120.6   69.93  4190.6    68.1  4260.6   67.85
  4340.6    68.5  4350.6   67.71  4370.6    67.7  4580.6   68.13  4971.4   64.92
  4972.9   61.92  5027.1   61.92  5028.6   64.92  5035.2    67.7  5505.2   67.08
  5525.2   67.65  5825.2   67.62  5915.2   68.98  5955.2   70.24  5975.2   71.46
  6085.2   73.64  6095.2   73.25  6235.2   74.23  6345.2   76.52    6384   78.33
#Mann= 3 ,-1,0
  3790.6     .15       0  4971.4    .045       0  5028.6     .15       0
Bank Sta=4971.4,5028.6
XS Rating Curve= 0 ,0
Exp/Cntr=0.3,0.1

Type RM Length L Ch R = 1 ,63961   ,500,500,500
BEGIN DESCRIPTION:
Indian Field Swamp 128.0
END DESCRIPTION:
XS GIS Cut Line= 3
      2150094.91       503281.09      2149713.48       502011.24
      2149399.54       500840.19
#Sta/Elev= 30
  3674.1   80.17  3734.1   79.99  3744.1   79.12  3984.1   74.42  4044.1   74.35
  4224.1   68.39  4384.1   67.39  4474.1   67.89  4494.1   69.16  4514.1   67.86
  4534.1   67.77  4574.1   68.46  4724.1   68.24  4774.1   67.31  4824.1    68.1
  4934.1   67.33  4971.4   64.79  4972.9   61.79  5027.1   61.79  5028.6   64.79
    5250    67.1    5930   66.83    5970    68.7    6000   73.59    6020   75.21
    6080   76.67    6100   79.65    6120   78.44    6140   79.72  6212.4   79.97
#Mann= 3 ,-1,0
  3674.1     .15       0  4971.4    .045       0  5028.6     .15       0
Bank Sta=4971.4,5028.6
XS Rating Curve= 0 ,0
Exp/Cntr=0.3,0.1

Type RM Length L Ch R = 1 ,63461   ,500,500,500
BEGIN DESCRIPTION:
Indian Field Swamp 127.0
END DESCRIPTION:
XS GIS Cut Line= 3
      2150981.14       503166.74      2150179.74       501860.48
      2149504.11       500798.72
#Sta/Elev= 30
  3467.5   76.33  3627.5    75.2  3807.5   75.52  3947.5    73.9  4097.5   73.34
  4117.5   72.64  4237.5   73.02  4257.5   73.83  4277.5   72.95  4347.5   72.98
  4437.5   70.79  4447.5   69.85  4677.5   67.16  4767.5   66.75  4837.5    67.7
  4907.5   66.61  4917.5    67.3  4967.5    66.9  4971.4   64.49  4972.9   61.49
  5027.1   61.49  5028.6   64.49    5100    66.7    5990   66.82    6020   67.21
    6070   73.61    6110   73.98    6170   76.25    6210   79.11  6258.5   79.76
#Mann= 3 ,-1,0
  3467.5     .15       0  4971.4    .045       0  5028.6     .15       0
Bank Sta=4971.4,5028.6
XS Rating Curve= 0 ,0
Exp/Cntr=0.3,0.1

Type RM Length L Ch R = 1 ,62961   ,500,500,500
BEGIN DESCRIPTION:
Indian Field Swamp 126.0
END DESCRIPTION:
XS GIS Cut Line= 3
      2151024.97       502224.96      2150476.24       501466.68
      2149925.02       500625.02
#Sta/Elev= 30
    4064   78.01    4114   76.77    4124   75.95    4184   75.38    4324    70.4
    4424   67.82    4584   66.27    4934   66.48    4954   67.14    4964   66.65
  4971.4   64.07  4972.9   61.07  5027.1   61.07  5028.6   64.07    5060    66.4
    5150   66.78    5240   66.14    5340   66.86    5360   66.07    5570   66.28
    5590   66.88    5600   66.42    5750   66.51    5790   67.32    5810   68.37
    5850   72.23    5860   73.61    5910   77.51    5930   77.18  6006.1    78.3
#Mann= 3 ,-1,0
    4064     .15       0  4971.4    .045       0  5028.6     .15       0
Bank Sta=4971.4,5028.6
XS Rating Curve= 0 ,0
Exp/Cntr=0.3,0.1