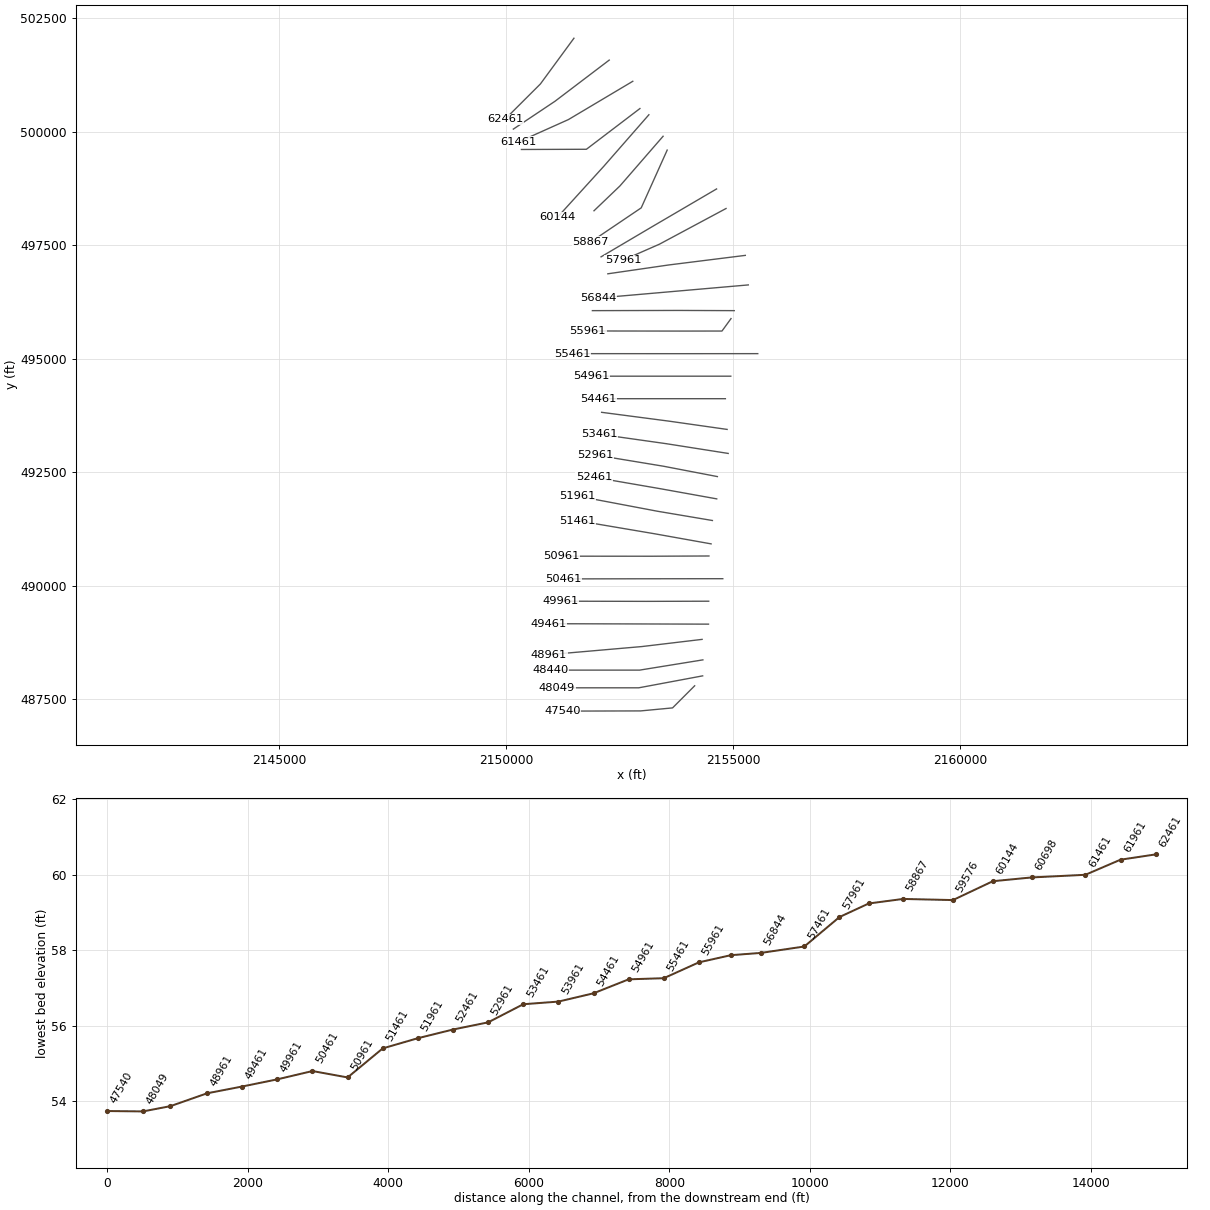
HEC-RAS study IndianFieldsSwamp.prj: S-18-19 over Indian Fields Swamp

--- IndianFieldsSwamp.g02 (geometry) --- (continued)

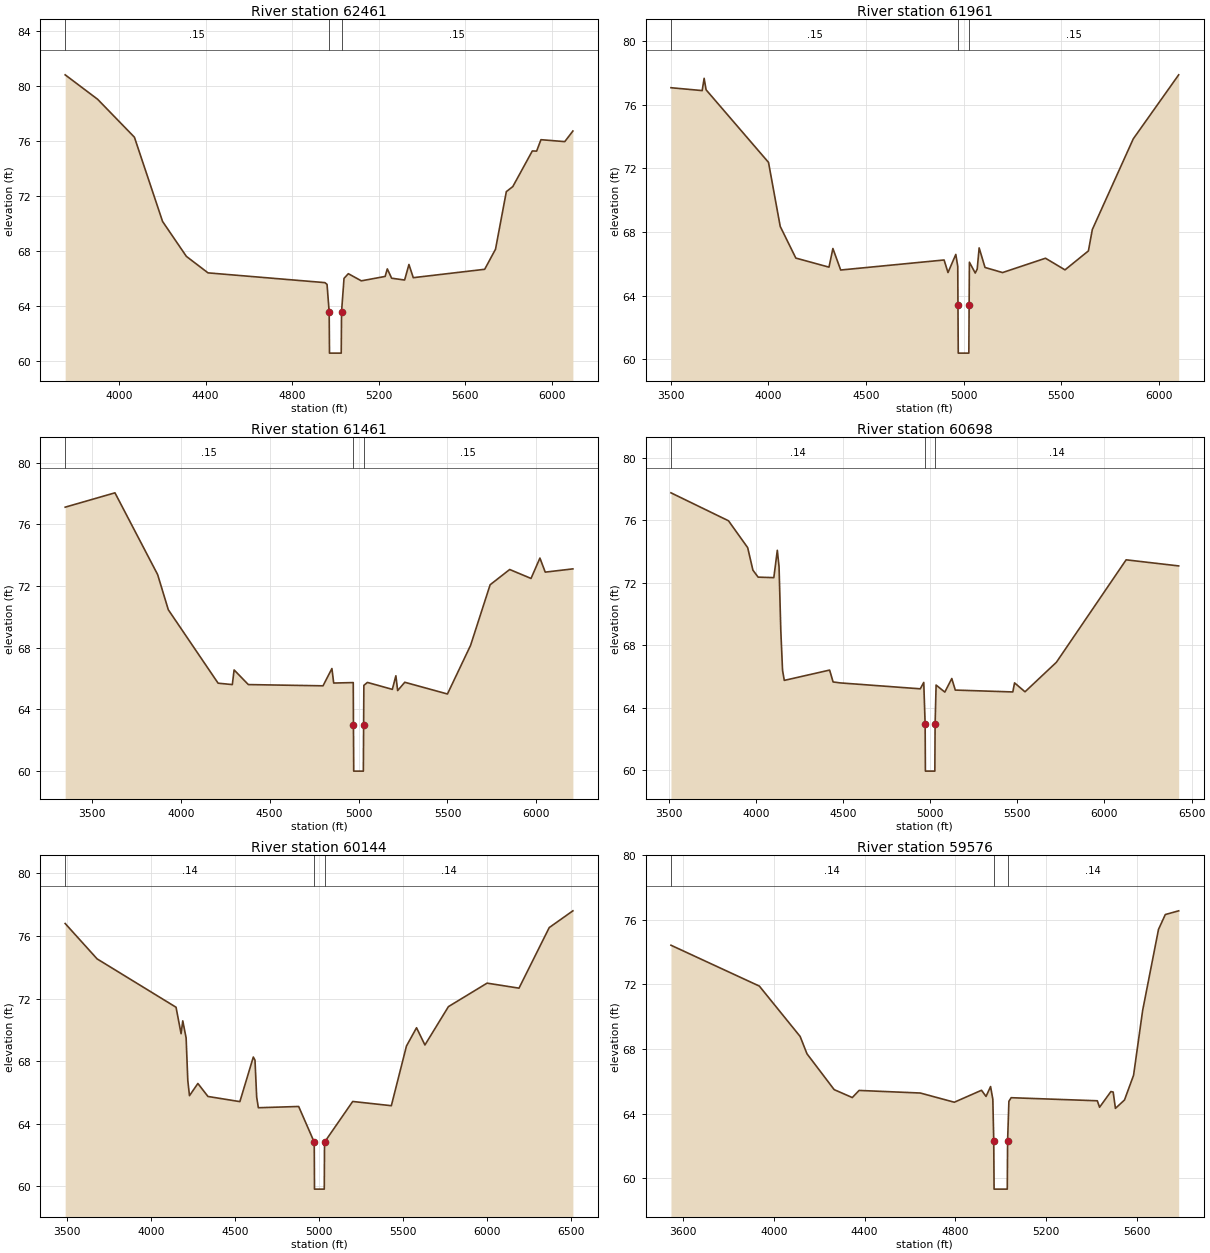
Type RM Length L Ch R = 1 ,62461   ,500,500,500
BEGIN DESCRIPTION:
Indian Field Swamp 125.0
END DESCRIPTION:
XS GIS Cut Line= 3
      2151495.69       502061.31      2150757.46       501054.58
      2149980.57       500279.37
#Sta/Elev= 30
  3751.6   80.79  3901.6   79.01  4071.6   76.25  4201.6   70.12  4311.6   67.58
  4411.6   66.38  4951.6   65.67  4961.6   65.54  4971.4   63.54  4972.9   60.54
  5027.1   60.54  5028.6   63.54    5040   65.98    5060   66.32    5120    65.8
    5230   66.12    5240   66.67    5260   65.99    5320   65.86    5340   66.99
    5360   66.03    5690   66.64    5740    68.1    5790   72.29    5820   72.66
    5910   75.25    5930   75.24    5950   76.07    6060   75.93  6097.5    76.7
#Mann= 3 ,-1,0
  3751.6     .15       0  4971.4    .045       0  5028.6     .15       0
Bank Sta=4971.4,5028.6
XS Rating Curve= 0 ,0
Exp/Cntr=0.3,0.1

Type RM Length L Ch R = 1 ,61961   ,500,500,500
BEGIN DESCRIPTION:
Indian Field Swamp 124.0
END DESCRIPTION:
XS GIS Cut Line= 3
      2152272.83       501579.79       2151078.3       500673.04
       2150161.6       500060.17
#Sta/Elev= 30
  3500.3   77.07  3660.3   76.89  3670.3   77.66  3680.3   76.94  4000.3   72.38
  4060.3   68.36  4140.3   66.37  4310.3    65.8  4330.3   66.97  4370.3   65.62
  4900.3   66.25  4920.3   65.46  4960.3    66.6  4970.3   65.85  4971.4    63.4
  4972.9    60.4  5027.1    60.4  5028.6    63.4    5030   66.11    5060   65.43
    5070   65.68    5080   67.01    5110   65.78    5200   65.46    5420   66.36
    5520   65.63    5640   66.82    5660   68.16    5870   73.86  6102.7   77.88
#Mann= 3 ,-1,0
  3500.3     .15       0  4971.4    .045       0  5028.6     .15       0
Bank Sta=4971.4,5028.6
XS Rating Curve= 0 ,0
Exp/Cntr=0.3,0.1

Type RM Length L Ch R = 1 ,61461   ,763,763,763
BEGIN DESCRIPTION:
Indian Field Swamp 123.0
END DESCRIPTION:
XS GIS Cut Line= 3
      2152791.66       501113.15      2151373.85       500269.75
        2150274.       499776.49
#Sta/Elev= 30
  3350.3   77.11  3630.3   78.04  3870.3   72.74  3930.3   70.46  4210.3    65.7
  4290.3   65.61  4300.3   66.56  4380.3   65.61  4800.3   65.53  4850.3   66.65
  4860.3   65.71  4970.3   65.74  4971.4      63  4972.9      60  5027.1      60
  5028.6      63    5030   65.56    5050   65.75    5190    65.3    5210   66.18
    5220   65.22    5260   65.76    5500      65    5630   68.15    5740   72.08
    5850   73.07    5970   72.49    6020   73.81    6050    72.9  6205.4   73.11
#Mann= 3 ,-1,0
  3350.3     .15       0  4971.4    .045       0  5028.6     .15       0
Bank Sta=4971.4,5028.6
XS Rating Curve= 0 ,0
Exp/Cntr=0.3,0.1

Type RM Length L Ch R = 1 ,60698   ,554,554,554
BEGIN DESCRIPTION:
Indian Field Swamp 122.0
END DESCRIPTION:
XS GIS Cut Line= 3
       2152948.9       500512.82      2151770.56       499615.95
       2150339.2       499611.36
#Sta/Elev= 30
  3513.5   77.75  3843.5   75.96  3953.5   74.24  3983.5    72.8  4013.5   72.35
  4103.5   72.32  4123.5   74.07  4133.5   73.01  4143.5   68.94  4153.5   66.39
  4163.5   65.74  4423.5    66.4  4443.5   65.64  4483.5   65.58  4943.5    65.2
  4963.5   65.61  4971.4   62.93  4972.9   59.93  5027.1   59.93  5028.6   62.93
  5034.3   65.44  5084.3   64.99  5124.3   65.86  5144.3   65.12  5474.3      65
  5484.3   65.58  5544.3   65.01  5724.3    66.9  6124.3   73.46  6425.7   73.07
#Mann= 3 ,-1,0
  3513.5     .14       0  4971.4    .045       0  5028.6     .14       0
Bank Sta=4971.4,5028.6
XS Rating Curve= 0 ,0
Exp/Cntr=0.3,0.1

Type RM Length L Ch R = 1 ,60144   ,568,568,568
BEGIN DESCRIPTION:
Indian Field Swamp 120.0
END DESCRIPTION:
XS GIS Cut Line= 3
      2153146.27       500376.16      2152150.88       499238.62
      2151134.34        498120.9
#Sta/Elev= 30
  3486.7    76.8  3676.7   74.54  4146.7   71.45  4176.7   69.76  4186.7   70.58
  4206.7   69.49  4216.7   66.77  4226.7    65.8  4276.7   66.58  4336.7   65.75
  4526.7   65.42  4606.7   68.27  4616.7   68.07  4626.7   65.71  4636.7   65.03
  4876.7   65.11  4969.4   62.83  4970.9   59.83  5029.1   59.83  5030.6   62.83
  5198.3   65.43  5428.3   65.16  5518.3   68.97  5578.3   70.14  5628.3   69.04
  5768.3   71.49  5998.3   72.99  6188.3   72.67  6368.3   76.54  6509.1   77.61
#Mann= 3 ,-1,0
  3486.7     .14       0  4969.4    .045       0  5030.6     .14       0
Bank Sta=4969.4,5030.6
XS Rating Curve= 0 ,0
Exp/Cntr=0.3,0.1

Type RM Length L Ch R = 1 ,59576   ,709,709,709
BEGIN DESCRIPTION:
Indian Field Swamp 119.0
END DESCRIPTION:
XS GIS Cut Line= 3
      2153459.13       499902.53      2152507.57       498807.19
      2151937.54       498261.73
#Sta/Elev= 30
  3545.4   74.43  3935.4    71.9  4115.4   68.78  4145.4   67.71  4265.4   65.49
  4345.4      65  4375.4   65.44  4645.4   65.28  4795.4   64.71  4915.4   65.45
  4935.4   65.07  4955.4   65.68  4965.4   64.89  4969.4   62.33  4970.9   59.33
  5029.1   59.33  5030.6   62.33  5036.3   64.77  5046.3   64.99  5426.3    64.8
  5436.3    64.4  5486.3   65.37  5496.3   65.34  5506.3   64.33  5546.3   64.85
  5586.3   66.38  5626.3   70.39  5696.3   75.41  5726.3   76.33  5785.3   76.56
#Mann= 3 ,-1,0
  3545.4     .14       0  4969.4    .045       0  5030.6     .14       0
Bank Sta=4969.4,5030.6
XS Rating Curve= 0 ,0
Exp/Cntr=0.3,0.1

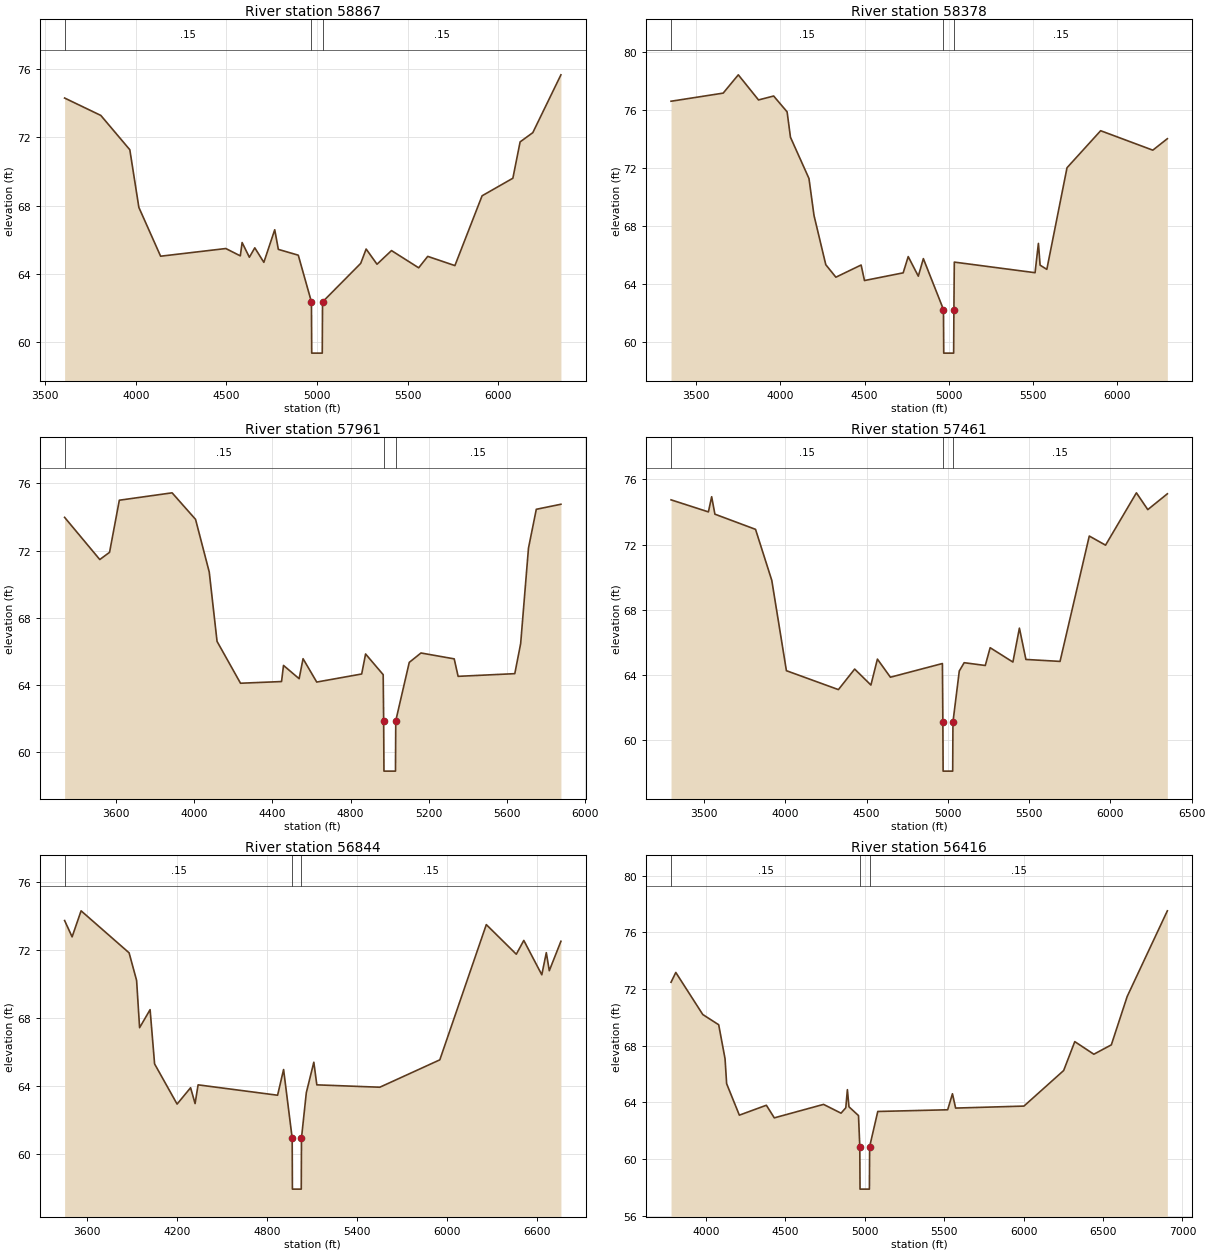
Type RM Length L Ch R = 1 ,58867   ,489,489,489
BEGIN DESCRIPTION:
Indian Field Swamp 118.0
END DESCRIPTION:
XS GIS Cut Line= 3
      2153549.22       499597.98      2152977.49       498325.86
      2151862.54       497573.03
#Sta/Elev= 30
  3606.7   74.31  3806.7   73.29  3966.7   71.28  4016.7    67.9  4136.7   65.04
  4496.7   65.49  4576.7   65.06  4586.7   65.84  4626.7   64.98  4656.7   65.53
  4706.7   64.68  4766.7   66.59  4786.7   65.44  4896.7    65.1  4969.4   62.36
  4970.9   59.36  5029.1   59.36  5030.6   62.36  5241.4   64.62  5271.4   65.46
  5331.4   64.57  5411.4   65.37  5561.4   64.36  5611.4   65.03  5761.4   64.49
  5911.4   68.58  6081.4   69.61  6121.4   71.74  6191.4   72.28  6346.7   75.67
#Mann= 3 ,-1,0
  3606.7     .15       0  4969.4    .045       0  5030.6     .15       0
Bank Sta=4969.4,5030.6
XS Rating Curve= 0 ,0
Exp/Cntr=0.3,0.1

Type RM Length L Ch R = 1 ,58378   ,417,417,417
BEGIN DESCRIPTION:
Indian Field Swamp 117.0
END DESCRIPTION:
XS GIS Cut Line= 3
      2154636.68       498742.29      2153209.58       497906.18
      2152093.11       497247.08
#Sta/Elev= 30
  3349.4   76.59  3659.4   77.15  3749.4   78.41  3869.4   76.68  3959.4   76.95
  4039.4   75.86  4059.4   74.11  4169.4   71.27  4199.4   68.72  4269.4   65.33
  4329.4   64.47  4479.4   65.31  4499.4   64.24  4729.4   64.77  4759.4   65.89
  4819.4   64.54  4849.4   65.75    4969   62.24  4970.5   59.24  5029.5   59.24
    5031   62.24  5033.4   65.51  5513.4   64.78  5533.4    66.8  5543.4    65.3
  5583.4   65.01  5703.4   72.01  5903.4   74.56  6213.4   73.22  6299.9   74.01
#Mann= 3 ,-1,0
  3349.4     .15       0    4969    .045       0    5031     .15       0
Bank Sta=4969,5031
XS Rating Curve= 0 ,0
Exp/Cntr=0.3,0.1

Type RM Length L Ch R = 1 ,57961   ,500,500,500
BEGIN DESCRIPTION:
Indian Field Swamp 116.0
END DESCRIPTION:
XS GIS Cut Line= 3
      2154845.23       498311.58      2153378.99       497526.06
      2152577.01       497173.64
#Sta/Elev= 30
  3336.6   73.98  3516.6   71.47  3566.6    71.9  3616.6      75  3886.6   75.44
  4006.6   73.86  4076.6   70.73  4116.6    66.6  4236.6   64.11  4446.6   64.21
  4456.6   65.17  4536.6   64.38  4556.6   65.57  4626.6   64.18  4856.6   64.66
  4876.6   65.85  4966.6   64.62    4969   61.88  4970.5   58.88  5029.5   58.88
    5031   61.88    5100   65.35    5160   65.91    5330   65.56    5350   64.52
    5640   64.68    5670   66.47    5710   72.15    5750   74.46    5876   74.76
#Mann= 3 ,-1,0
  3336.6     .15       0    4969    .045       0    5031     .15       0
Bank Sta=4969,5031
XS Rating Curve= 0 ,0
Exp/Cntr=0.3,0.1

Type RM Length L Ch R = 1 ,57461   ,617,617,617
BEGIN DESCRIPTION:
Indian Field Swamp 115.0
END DESCRIPTION:
XS GIS Cut Line= 3
      2155269.43       497279.35      2153578.82       497067.73
      2152242.41       496873.81
#Sta/Elev= 30
  3296.2   74.74  3526.2      74  3546.2   74.93  3566.2   73.86  3816.2   72.93
  3916.2    69.8  4006.2   64.26  4326.2    63.1  4426.2   64.36  4526.2   63.38
  4566.2   64.97  4646.2   63.86  4966.2    64.7    4969    61.1  4970.5    58.1
  5029.5    58.1    5031    61.1    5070   64.24    5100   64.75    5230   64.58
    5260   65.67    5400   64.79    5440   66.87    5480   64.95    5690   64.83
    5870   72.52    5970   71.96    6160   75.17    6230   74.14  6350.4   75.11
#Mann= 3 ,-1,0
  3296.2     .15       0    4969    .045       0    5031     .15       0
Bank Sta=4969,5031
XS Rating Curve= 0 ,0
Exp/Cntr=0.3,0.1

Type RM Length L Ch R = 1 ,56844   ,428,428,428
BEGIN DESCRIPTION:
Indian Field Swamp 114.0
END DESCRIPTION:
XS GIS Cut Line= 3
       2155335.8       496628.88      2153800.04       496494.89
      2152039.23       496341.26
#Sta/Elev= 30
  3451.7   73.72  3501.7   72.76  3561.7   74.29  3881.7   71.82  3931.7    70.2
  3951.7   67.42  4021.7   68.48  4051.7   65.29  4201.7   62.93  4291.7   63.89
  4321.7   62.96  4341.7   64.06  4871.7   63.45  4911.7   64.96    4969   60.93
  4970.5   57.93  5029.5   57.93    5031   60.93  5063.3    63.6  5113.3   65.39
  5133.3   64.06  5553.3   63.92  5953.3   65.53  6263.3   73.48  6463.3   71.74
  6513.3   72.55  6633.3   70.53  6663.3   71.83  6683.3   70.77  6760.8    72.5
#Mann= 3 ,-1,0
  3451.7     .15       0    4969    .045       0    5031     .15       0
Bank Sta=4969,5031
XS Rating Curve= 0 ,0
Exp/Cntr=0.3,0.1

Type RM Length L Ch R = 1 ,56416   ,455,455,455
BEGIN DESCRIPTION:
Indian Field Swamp 113.0
END DESCRIPTION:
XS GIS Cut Line= 3
      2155026.05       496062.49      2153804.75       496066.92
      2151902.06       496062.49
#Sta/Elev= 30
  3780.9   72.47  3810.9   73.16  3980.9   70.19  4080.9   69.47  4120.9   67.07
  4130.9   65.31  4210.9   63.09  4380.9   63.79  4430.9    62.9  4740.9   63.85
  4850.9   63.23  4880.9   63.61  4890.9   64.89  4900.9   63.68  4960.9   63.06
    4969   60.87  4970.5   57.87  5029.5   57.87    5031   60.87  5082.2   63.35
  5522.2   63.47  5552.2    64.6  5572.2   63.59  6002.2   63.73  6252.2   66.24
  6322.2   68.28  6442.2   67.39  6552.2   68.05  6652.2   71.47  6904.9   77.51
#Mann= 3 ,-1,0
  3780.9     .15       0    4969    .045       0    5031     .15       0
Bank Sta=4969,5031
XS Rating Curve= 0 ,0
Exp/Cntr=0.3,0.1

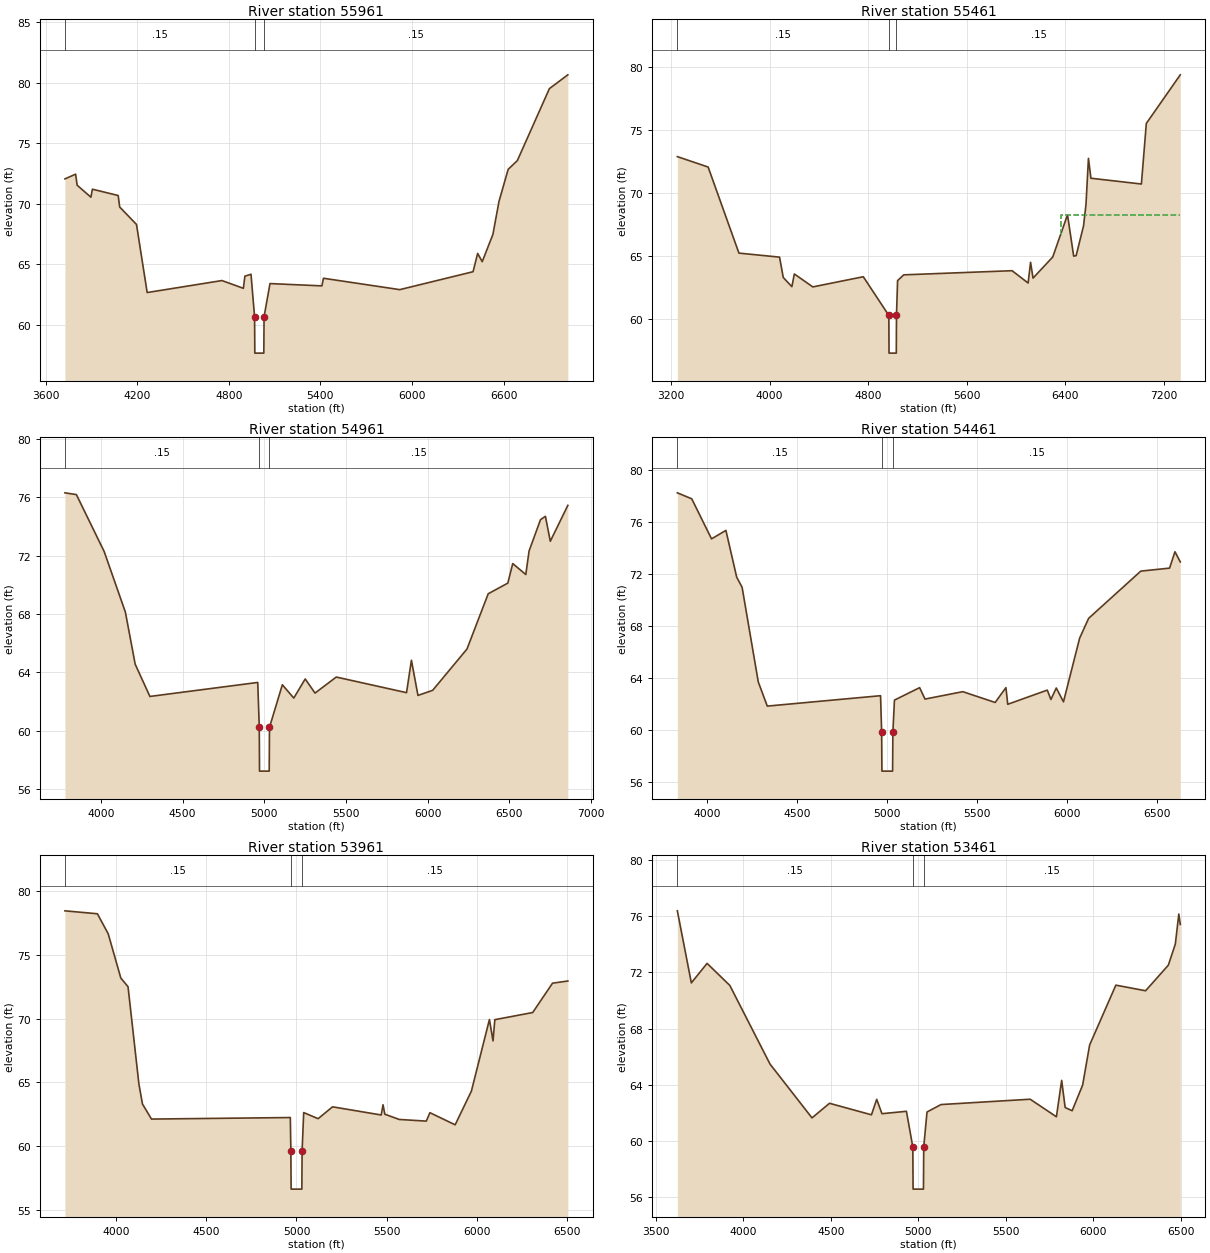
Type RM Length L Ch R = 1 ,55961   ,500,500,500
BEGIN DESCRIPTION:
Indian Field Swamp 112.0
END DESCRIPTION:
XS GIS Cut Line= 4
      2154954.97       495887.31      2154755.89       495613.27
      2153821.41       495612.37      2151800.61        495614.8
#Sta/Elev= 30
  3726.8   72.06  3796.8   72.45  3806.8   71.54  3896.8   70.55  3906.8   71.21
  4075.5   70.69  4085.5   69.74  4195.5    68.3  4265.5   62.68  4755.5   63.67
  4895.5   63.03  4905.5   64.03  4945.5   64.19    4969   60.68  4970.5   57.68
  5029.5   57.68    5031   60.68    5070   63.42    5410   63.23    5420   63.86
    5920   62.92    6400    64.4    6430   65.91    6460   65.23    6530   67.48
    6570   70.21    6630   72.85    6690   73.57    6900   79.51  7020.8   80.65
#Mann= 3 ,-1,0
  3726.8     .15       0    4969    .045       0    5031     .15       0
Bank Sta=4969,5031
XS Rating Curve= 0 ,0
Exp/Cntr=0.3,0.1

Type RM Length L Ch R = 1 ,55461   ,500,500,500
BEGIN DESCRIPTION:
Indian Field Swamp 111.0
END DESCRIPTION:
XS GIS Cut Line= 3
      2155543.72       495115.56      2153795.22       495114.74
      2151459.52       495115.56
#Sta/Elev= 30
  3251.5    72.9  3501.5   72.07  3751.5   65.22  4081.5    64.9  4111.5   63.28
  4181.5   62.55  4201.5   63.56  4351.5   62.53  4761.5   63.34    4969   60.26
  4970.5   57.26  5029.5   57.26    5031   60.26    5040   63.03    5090   63.49
    5970   63.82    6100   62.84    6120   64.49    6140   63.23    6300   64.91
    6420   68.27    6470   64.98    6490   65.02    6550   67.38    6570   69.09
    6590   72.76    6610   71.18    7020   70.72    7060   75.54  7335.7   79.41
#Mann= 3 ,-1,0
  3251.5     .15       0    4969    .045       0    5031     .15       0
#XS Ineff= 2 , 0
       0  3636.1   68.22  6363.9       0   68.22
Permanent Ineff=
       F       F
Bank Sta=4969,5031
XS Rating Curve= 0 ,0
Exp/Cntr=0.3,0.1

Type RM Length L Ch R = 1 ,54961   ,500,500,500
BEGIN DESCRIPTION:
Indian Field Swamp 110.0
END DESCRIPTION:
XS GIS Cut Line= 3
        2154950.         494619.       2153729.4       494619.09
       2151872.1         494619.
#Sta/Elev= 30
  3779.4   76.31  3849.4   76.19  4019.4   72.29  4149.4   68.13  4209.4   64.56
  4299.4   62.35  4959.4   63.31  4968.8   60.23  4970.3   57.23  5029.7   57.23
  5031.2   60.23    5110   63.15    5180   62.24    5250   63.55    5310   62.58
    5440   63.68    5870   62.61    5900   64.83    5940   62.42    6030   62.77
    6240    65.6    6370   69.39    6490   70.12    6520   71.46    6600   70.71
    6620   72.32    6690   74.47    6720    74.7    6750   72.99  6857.3   75.45
#Mann= 3 ,-1,0
  3779.4     .15       0  4968.8    .045       0  5031.2     .15       0
Bank Sta=4968.8,5031.2
XS Rating Curve= 0 ,0
Exp/Cntr=0.3,0.1

Type RM Length L Ch R = 1 ,54461   ,500,500,500
BEGIN DESCRIPTION:
Indian Field Swamp 109.0
END DESCRIPTION:
XS GIS Cut Line= 3
      2154830.88       494123.48      2153663.58       494123.44
      2152034.08       494123.48
#Sta/Elev= 30
  3832.7   78.26  3912.7    77.8  4022.7   74.72  4102.7   75.37  4162.7   71.77
  4192.7      71  4282.7   63.72  4332.7   61.86  4962.7   62.66  4968.8   59.86
  4970.3   56.86  5029.7   56.86  5031.2   59.86    5040   62.32    5180   63.28
    5210    62.4    5420   62.97    5600   62.14    5660   63.28    5670      62
    5890   63.09    5910   62.37    5940   63.25    5980   62.19    6070   67.09
    6120   68.61    6410   72.24    6570   72.47    6600   73.73  6629.5   72.95
#Mann= 3 ,-1,0
  3832.7     .15       0  4968.8    .045       0  5031.2     .15       0
Bank Sta=4968.8,5031.2
XS Rating Curve= 0 ,0
Exp/Cntr=0.3,0.1

Type RM Length L Ch R = 1 ,53961   ,500,500,500
BEGIN DESCRIPTION:
Indian Field Swamp 108.0
END DESCRIPTION:
XS GIS Cut Line= 3
      2154869.05        493446.9      2153597.75       493627.79
      2152105.61        493823.3
#Sta/Elev= 30
  3715.9   78.45  3895.9   78.22  3955.9   76.65  4025.9   73.18  4065.9    72.5
  4125.9    64.9  4145.9   63.31  4195.9   62.13  4965.9   62.25  4968.8   59.64
  4970.3   56.64  5029.7   56.64  5031.2   59.64    5040   62.64    5120   62.16
    5200   63.09    5470   62.45    5480   63.25    5490   62.51    5570    62.1
    5720   61.97    5740   62.63    5880   61.68    5970   64.32    6070   69.93
    6090   68.26    6100   69.92    6310   70.48    6420   72.78  6504.9   72.95
#Mann= 3 ,-1,0
  3715.9     .15       0  4968.8    .045       0  5031.2     .15       0
Bank Sta=4968.8,5031.2
XS Rating Curve= 0 ,0
Exp/Cntr=0.3,0.1

Type RM Length L Ch R = 1 ,53461   ,500,500,500
BEGIN DESCRIPTION:
Indian Field Swamp 107.0
END DESCRIPTION:
XS GIS Cut Line= 3
      2154892.89       492918.03      2153531.93       493132.14
      2152048.41       493342.08
#Sta/Elev= 30
  3622.3   76.38  3702.3   71.25  3792.3   72.64  3922.3   71.07  4152.3   65.47
  4392.3   61.64  4492.3   62.68  4732.3   61.86  4762.3   62.96  4792.3   61.94
  4932.3   62.11  4968.8   59.57  4970.3   56.57  5029.7   56.57  5031.2   59.57
    5050   62.06    5130   62.59    5640   62.97    5790   61.72    5820   64.31
    5840   62.38    5880   62.15    5940   63.98    5980   66.83    6130   71.09
    6300   70.69    6430   72.51    6470   74.01    6490   76.15  6498.3   75.41
#Mann= 3 ,-1,0
  3622.3     .15       0  4968.8    .045       0  5031.2     .15       0
Bank Sta=4968.8,5031.2
XS Rating Curve= 0 ,0
Exp/Cntr=0.3,0.1

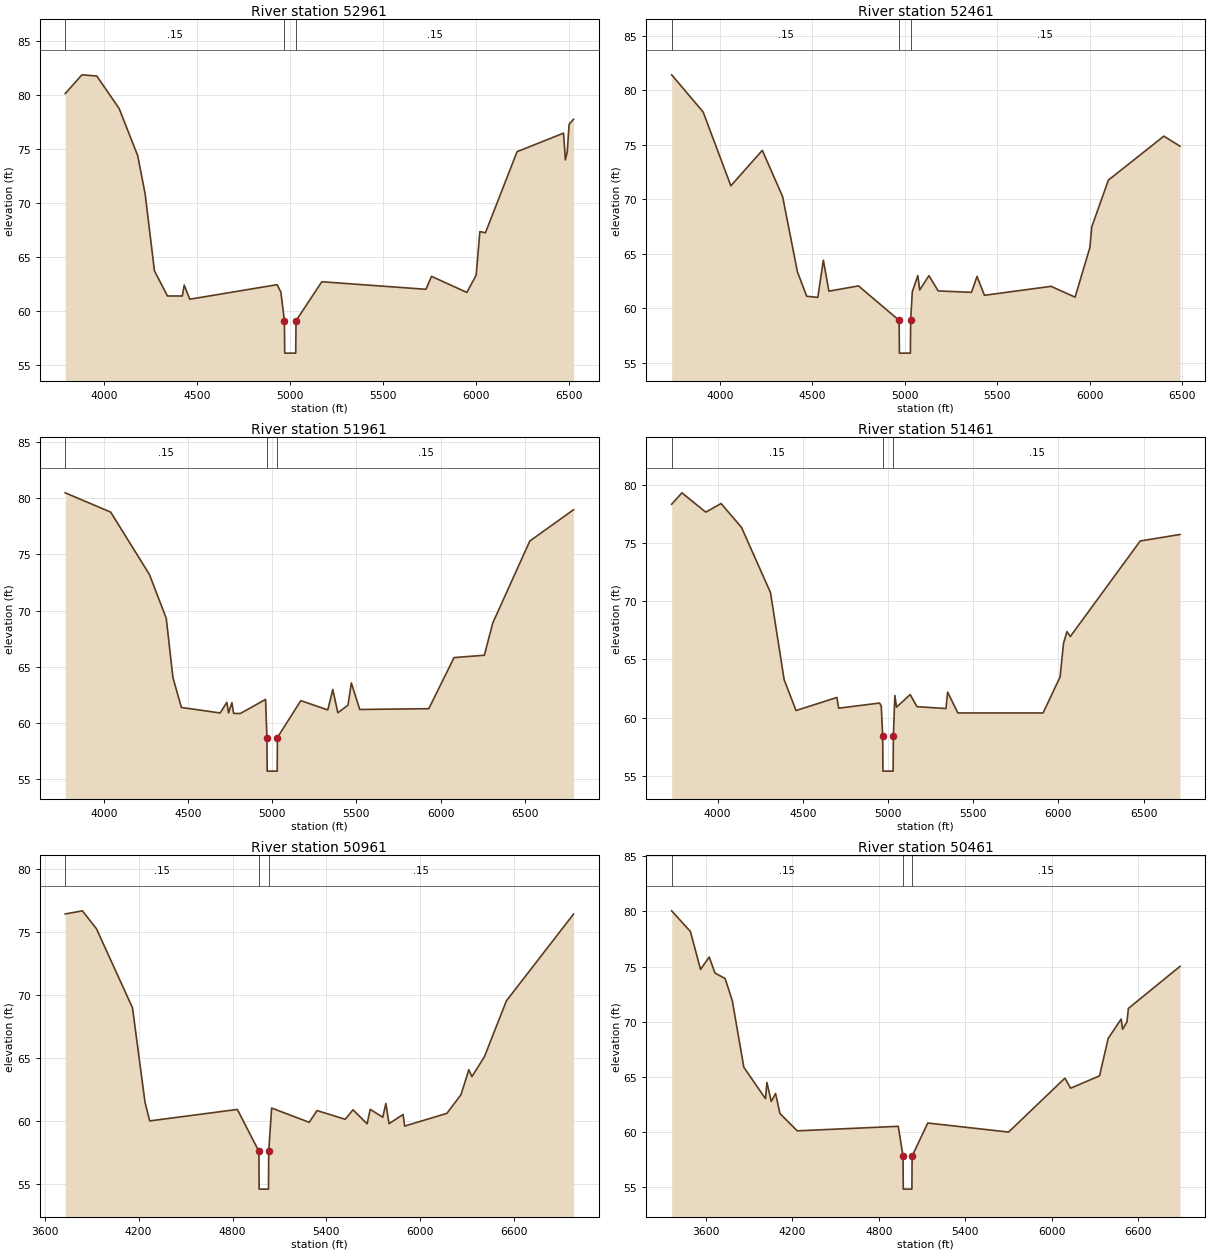
Type RM Length L Ch R = 1 ,52961   ,500,500,500
BEGIN DESCRIPTION:
Indian Field Swamp 106.0
END DESCRIPTION:
XS GIS Cut Line= 3
      2154654.58       492408.23       2153466.1       492636.49
      2151962.65       492884.68
#Sta/Elev= 30
  3789.8   80.16  3879.8    81.9  3959.8   81.79  4079.8   78.78  4179.8    74.4
  4219.8   70.85  4269.8   63.72  4339.8   61.39  4419.8   61.39  4429.8    62.4
  4459.8   61.09  4929.8   62.44  4949.8   61.74  4968.8   59.09  4970.3   56.09
  5029.7   56.09  5031.2   59.09    5170   62.71    5730   62.01    5760   63.21
    5950   61.72    6000   63.31    6020   67.36    6050   67.25    6220   74.77
    6470   76.49    6480   74.01    6490   74.75    6500   77.31  6523.8   77.78
#Mann= 3 ,-1,0
  3789.8     .15       0  4968.8    .045       0  5031.2     .15       0
Bank Sta=4968.8,5031.2
XS Rating Curve= 0 ,0
Exp/Cntr=0.3,0.1

Type RM Length L Ch R = 1 ,52461   ,500,500,500
BEGIN DESCRIPTION:
Indian Field Swamp 105.0
END DESCRIPTION:
XS GIS Cut Line= 3
      2154640.37       491917.46      2153399.53       492140.95
      2151934.01       492393.93
#Sta/Elev= 30
  3739.2    81.4  3909.2      78  4059.2   71.23  4229.2   74.48  4339.2   70.23
  4419.2   63.34  4469.2   61.11  4529.2   61.01  4559.2   64.41  4589.2   61.58
  4749.2   62.06  4968.8    58.9  4970.3    55.9  5029.7    55.9  5031.2    58.9
    5040   61.53    5070   63.01    5080   61.69    5130      63    5180    61.6
    5360   61.47    5390   62.93    5430    61.2    5790   62.02    5920   61.03
    6000   65.57    6010   67.46    6100   71.75    6400   75.78  6487.2   74.86
#Mann= 3 ,-1,0
  3739.2     .15       0  4968.8    .045       0  5031.2     .15       0
Bank Sta=4968.8,5031.2
XS Rating Curve= 0 ,0
Exp/Cntr=0.3,0.1

Type RM Length L Ch R = 1 ,51961   ,500,500,500
BEGIN DESCRIPTION:
Indian Field Swamp 104.0
END DESCRIPTION:
XS GIS Cut Line= 3
      2154545.02       491441.01      2153332.93        491645.4
      2151574.57       491978.31
#Sta/Elev= 30
  3770.8    80.5  4040.8   78.78  4270.8   73.22  4370.8   69.31  4410.8      64
  4460.8   61.35  4690.8   60.86  4730.8   61.81  4740.8   60.86  4760.8   61.78
  4770.8   60.82  4810.8   60.81  4960.8   62.07  4968.8   58.67  4970.3   55.67
  5029.7   55.67  5031.2   58.67    5170   61.96    5330   61.13    5360   62.95
    5390   60.88    5450   61.55    5470   63.54    5520   61.17    5930   61.24
    6080    65.8    6260   66.01    6310   68.89    6530    76.2  6789.6   78.99
#Mann= 3 ,-1,0
  3770.8     .15       0  4968.8    .045       0  5031.2     .15       0
Bank Sta=4968.8,5031.2
XS Rating Curve= 0 ,0
Exp/Cntr=0.3,0.1

Type RM Length L Ch R = 1 ,51461   ,500,500,500
BEGIN DESCRIPTION:
Indian Field Swamp 103.0
END DESCRIPTION:
XS GIS Cut Line= 3
      2154516.42       490926.43      2153266.33       491149.86
      2151576.73       491436.23
#Sta/Elev= 30
  3730.1   78.34  3790.1   79.32  3930.1   77.66  4020.1    78.4  4140.1   76.35
  4310.1   70.75  4390.1   63.27  4460.1   60.61  4700.1   61.73  4710.1   60.81
  4950.1   61.25  4960.1      61  4968.6    58.4  4970.1    55.4  5029.9    55.4
  5031.4    58.4    5040    61.9    5050    60.9    5130   61.98    5170   60.94
    5340   60.78    5350   62.19    5410    60.4    5910    60.4    6010    63.5
    6030   66.38    6050   67.39    6070   66.97    6480   75.18  6713.7   75.74
#Mann= 3 ,-1,0
  3730.1     .15       0  4968.6    .045       0  5031.4     .15       0
Bank Sta=4968.6,5031.4
XS Rating Curve= 0 ,0
Exp/Cntr=0.3,0.1

Type RM Length L Ch R = 1 ,50961   ,500,500,500
BEGIN DESCRIPTION:
Indian Field Swamp 102.0
END DESCRIPTION:
XS GIS Cut Line= 3
      2154468.82       490659.61      2153199.73       490654.31
      2151220.63       490655.25
#Sta/Elev= 30
  3730.9   76.45  3840.9    76.7  3930.9   75.27  4160.9   69.01  4240.9   61.51
  4270.9   60.04  4830.9   60.95  4968.6   57.63  4970.1   54.63  5029.9   54.63
  5031.4   57.63    5050   61.06    5290   59.93    5340   60.86    5520   60.17
    5570   60.92    5660   59.81    5680   60.96    5760   60.33    5780   61.42
    5800   59.82    5890   60.55    5900   59.63    6170   60.64    6260   62.12
    6310    64.1    6330   63.55    6410   65.14    6550   69.56  6979.1   76.44
#Mann= 3 ,-1,0
  3730.9     .15       0  4968.6    .045       0  5031.4     .15       0
Bank Sta=4968.6,5031.4
XS Rating Curve= 0 ,0
Exp/Cntr=0.3,0.1

Type RM Length L Ch R = 1 ,50461   ,500,500,500
BEGIN DESCRIPTION:
Indian Field Swamp 101.0
END DESCRIPTION:
XS GIS Cut Line= 3
       2154773.8       490159.66       2153139.2       490158.06
      2151251.61       490155.24
#Sta/Elev= 30
  3365.4   80.06  3495.4   78.18  3565.4   74.74  3625.4   75.87  3665.4   74.41
  3735.4   73.92  3785.4   71.91  3865.4   65.86  4015.4   63.01  4025.4   64.48
  4055.4   62.76  4085.4   63.48  4115.4   61.67  4235.4   60.09  4935.4    60.5
  4968.6    57.8  4970.1    54.8  5029.9    54.8  5031.4    57.8    5140    60.8
    5700   59.98    6090   64.87    6130   63.96    6330   65.08    6390   68.48
    6480   70.24    6490   69.31    6520   69.97    6530    71.2  6887.6   75.02
#Mann= 3 ,-1,0
  3365.4     .15       0  4968.6    .045       0  5031.4     .15       0
Bank Sta=4968.6,5031.4
XS Rating Curve= 0 ,0
Exp/Cntr=0.3,0.1

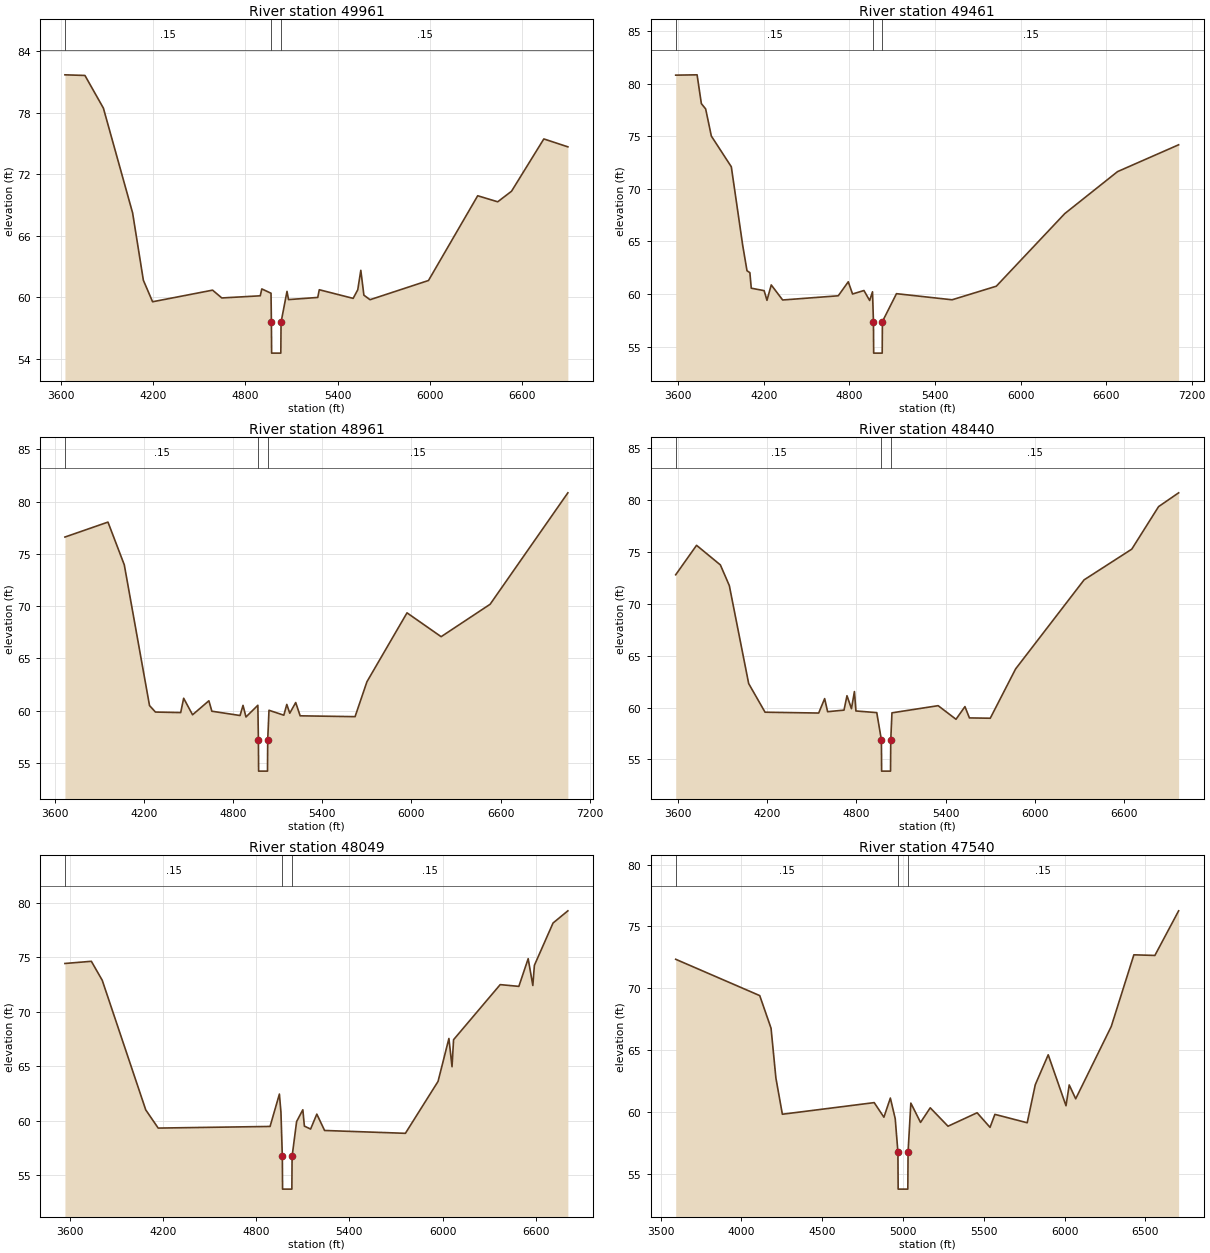
Type RM Length L Ch R = 1 ,49961   ,500,500,500
BEGIN DESCRIPTION:
Indian Field Swamp 100.0
END DESCRIPTION:
XS GIS Cut Line= 3
      2154464.06       489663.81      2153090.26       489660.46
      2151194.07       489664.07
#Sta/Elev= 30
  3626.2   81.67  3756.2   81.61  3876.2   78.43  4066.2   68.23  4136.2   61.67
  4196.2   59.58  4586.2   60.71  4646.2   59.95  4896.2   60.16  4906.2   60.83
  4966.2   60.41  4968.6   57.58  4970.1   54.58  5029.9   54.58  5031.4   57.58
    5070   60.59    5080   59.79    5270      60    5280   60.75    5500   59.91
    5530   60.74    5550   62.64    5570   60.22    5610   59.78    5990   61.65
    6310    69.9    6440   69.31    6530   70.34    6740   75.43  6896.2   74.66
#Mann= 3 ,-1,0
  3626.2     .15       0  4968.6    .045       0  5031.4     .15       0
Bank Sta=4968.6,5031.4
XS Rating Curve= 0 ,0
Exp/Cntr=0.3,0.1

Type RM Length L Ch R = 1 ,49461   ,500,500,500
BEGIN DESCRIPTION:
Indian Field Swamp 99.0
END DESCRIPTION:
XS GIS Cut Line= 3
      2154459.32       489158.76      2153041.33       489162.86
      2150932.93       489168.48
#Sta/Elev= 30
    3582   80.81    3732   80.84    3762    78.1    3792    77.6    3832   75.02
    3972    72.1    4052   64.62    4082   62.22    4102   62.04    4112   60.56
    4202   60.33    4222   59.41    4252   60.87    4332   59.44    4722   59.84
    4792   61.17    4822   60.01    4902   60.34    4942   59.39    4962   60.22
  4968.6   57.39  4970.1   54.39  5029.9   54.39  5031.4   57.39    5130   60.04
    5520   59.46    5830   60.75    6310   67.65    6680   71.64  7108.4   74.19
#Mann= 3 ,-1,0
    3582     .15       0  4968.6    .045       0  5031.4     .15       0
Bank Sta=4968.6,5031.4
XS Rating Curve= 0 ,0
Exp/Cntr=0.3,0.1

Type RM Length L Ch R = 1 ,48961   ,521,521,521
BEGIN DESCRIPTION:
Indian Field Swamp 98.0
END DESCRIPTION:
XS GIS Cut Line= 3
        2154318.       488823.34      2152992.39       488665.26
      2150946.23       488487.05
#Sta/Elev= 30
    3665    76.6    3955   78.03    4065   73.94    4235   60.48    4275   59.86
    4445   59.81    4465   61.18    4525    59.6    4635   60.94    4655   59.94
    4845   59.53    4865    60.5    4885   59.39    4965   60.51  4968.6   57.21
  4970.1   54.21  5029.9   54.21  5031.4   57.21    5040   60.03    5140   59.56
    5160   60.59    5180   59.75    5220   60.77    5250    59.5    5620   59.42
    5700   62.76    5970   69.35    6200   67.07    6530   70.17  7053.9   80.83
#Mann= 3 ,-1,0
    3665     .15       0  4968.6    .045       0  5031.4     .15       0
Bank Sta=4968.6,5031.4
XS Rating Curve= 0 ,0
Exp/Cntr=0.3,0.1

Type RM Length L Ch R = 1 ,48440   ,391,391,391
BEGIN DESCRIPTION:
Indian Field Swamp 97.0
END DESCRIPTION:
XS GIS Cut Line= 3
       2154335.7       488371.99      2152941.89       488146.33
      2150977.25       488146.33
#Sta/Elev= 30
  3587.5    72.8  3727.5   75.64  3887.5   73.75  3947.5   71.76  4077.5   62.31
  4187.5   59.55  4547.5   59.47  4587.5   60.86  4607.5    59.6  4717.5   59.75
  4737.5   61.14  4767.5   59.89  4787.5   61.54  4797.5   59.67  4937.5   59.51
  4968.6   56.87  4970.1   53.87  5029.9   53.87  5031.4   56.87  5039.5   59.49
  5349.5   60.18  5469.5   58.87  5529.5   60.09  5559.5      59  5699.5   58.97
  5869.5   63.72  6329.5   72.31  6649.5   75.27  6829.5   79.37  6964.1    80.7
#Mann= 3 ,-1,0
  3587.5     .15       0  4968.6    .045       0  5031.4     .15       0
Bank Sta=4968.6,5031.4
XS Rating Curve= 0 ,0
Exp/Cntr=0.3,0.1

Type RM Length L Ch R = 1 ,48049   ,509,509,509
BEGIN DESCRIPTION:
Indian Field Swamp 96.0
END DESCRIPTION:
XS GIS Cut Line= 3
      2154330.63       488020.02      2152924.19       487756.94
      2151118.83       487756.94
#Sta/Elev= 30
  3569.7   74.43  3739.7   74.63  3809.7   72.89  4089.7      61  4169.7   59.33
  4889.7   59.48  4949.7   62.45  4959.7   60.78  4968.6   56.73  4970.1   53.73
  5029.9   53.73  5031.4   56.73  5060.5   59.93  5100.5   61.01  5110.5   59.51
  5150.5   59.24  5190.5   60.61  5240.5   59.11  5760.5   58.85  5970.5   63.61
  6040.5   67.55  6060.5   64.96  6070.5   67.44  6370.5   72.49  6490.5   72.33
  6550.5   74.87  6580.5   72.41  6590.5   74.26  6710.5   78.14  6805.9   79.26
#Mann= 3 ,-1,0
  3569.7     .15       0  4968.6    .045       0  5031.4     .15       0
Bank Sta=4968.6,5031.4
XS Rating Curve= 0 ,0
Exp/Cntr=0.3,0.1

Type RM Length L Ch R = 1 ,47540   ,600,600,600
BEGIN DESCRIPTION:
Indian Field Swamp 95.0
END DESCRIPTION:
XS GIS Cut Line= 4
      2154154.31       487801.18      2153667.58       487314.45
      2152964.01       487248.07      2151247.15       487243.65
#Sta/Elev= 30
  3593.6   72.34  4113.6    69.4  4183.6   66.76  4213.6   62.73  4253.6    59.8
  4821.9   60.74  4881.9   59.56  4921.9   61.11  4951.9   59.44  4968.6   56.74
  4970.1   53.74  5029.9   53.74  5031.4   56.74  5048.6    60.7  5108.6   59.14
  5168.6   60.32  5278.6   58.83  5458.6   59.92  5538.6   58.74  5568.6   59.79
  5768.6   59.11  5818.6   62.19  5898.6   64.61  6008.6   60.49  6028.6   62.17
  6068.6   61.05  6288.6    66.9  6428.6    72.7  6558.6   72.65  6705.5   76.26
#Mann= 3 ,-1,0
  3593.6     .15       0  4968.6    .045       0  5031.4     .15       0
Bank Sta=4968.6,5031.4
XS Rating Curve= 0 ,0
Exp/Cntr=0.3,0.1