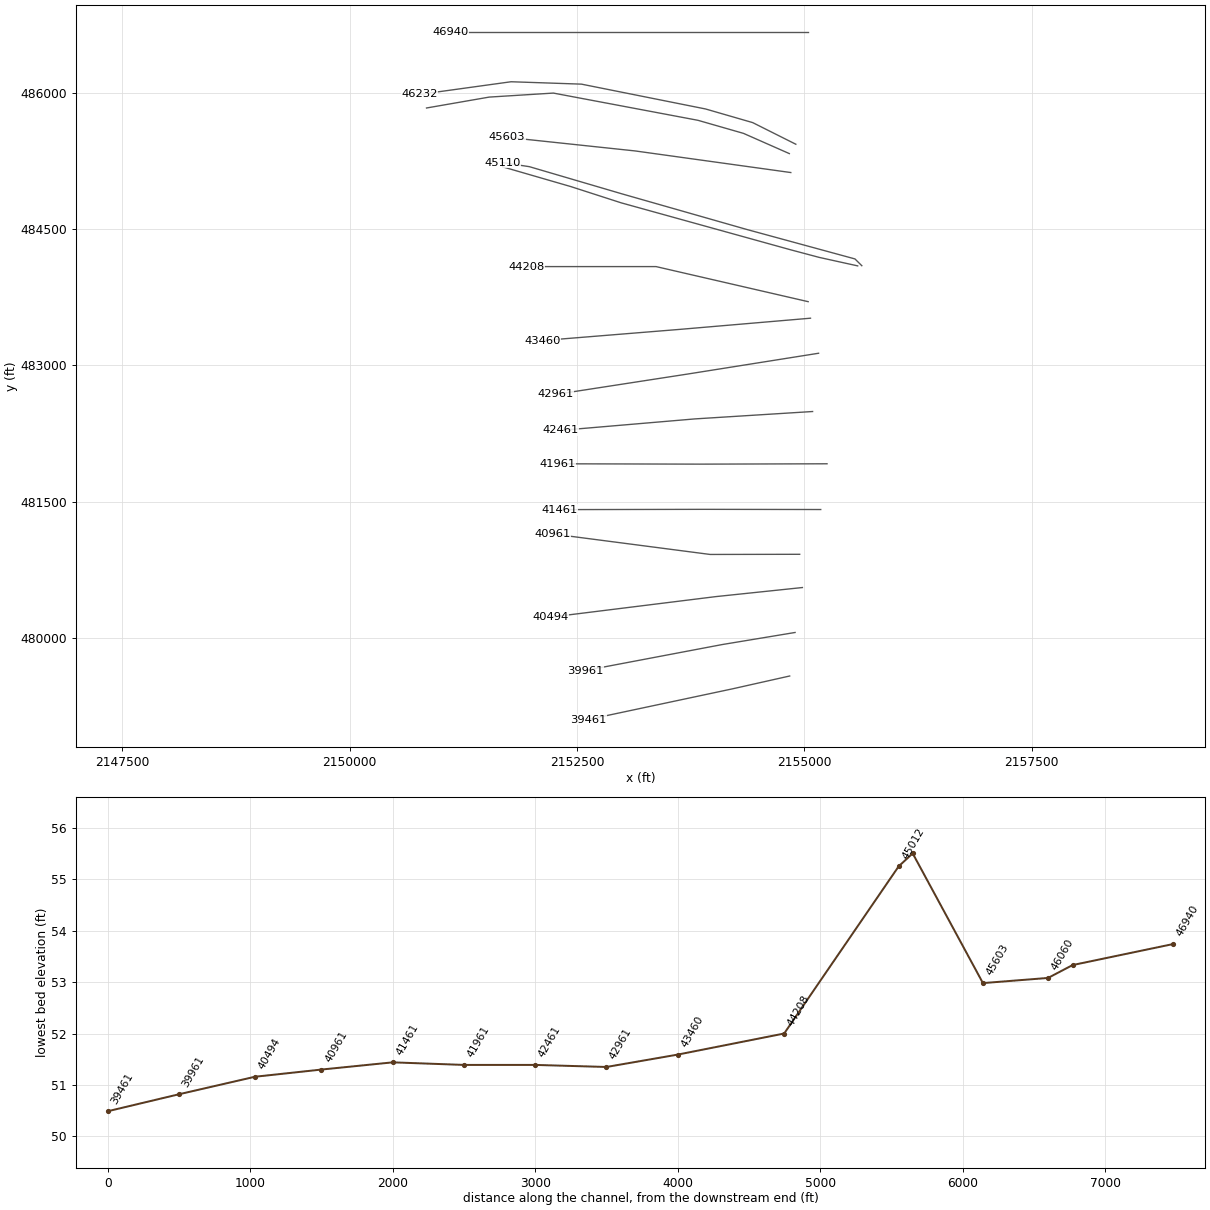
HEC-RAS study IndianFieldsSwamp.prj: S-18-19 over Indian Fields Swamp

--- IndianFieldsSwamp.g02 (geometry) --- (continued)

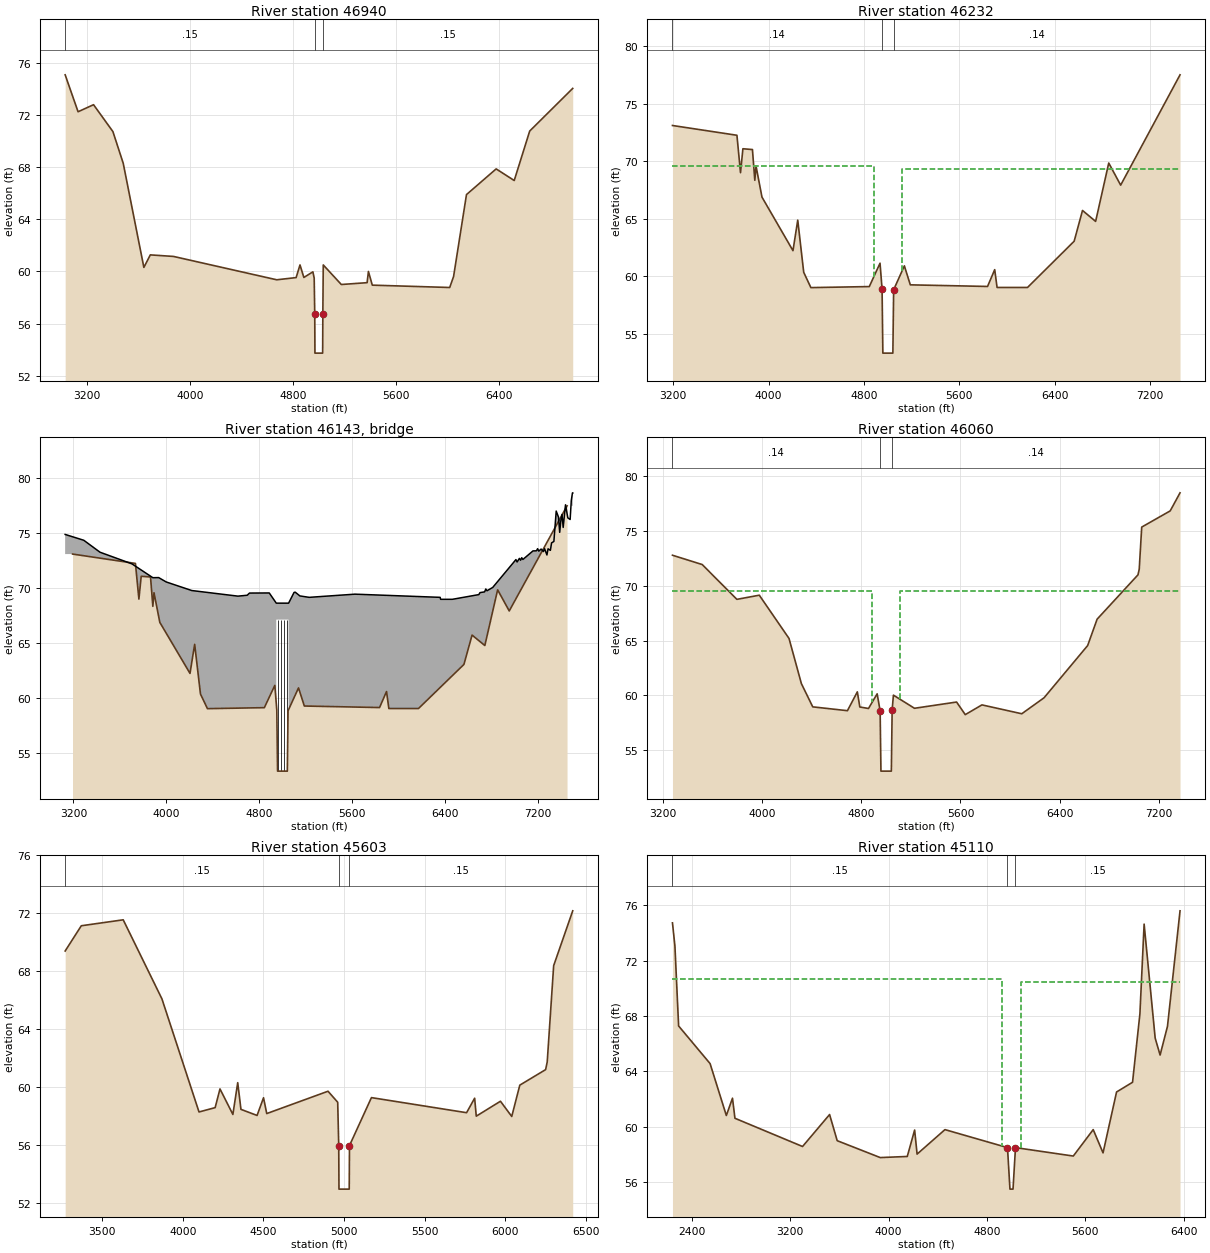
Type RM Length L Ch R = 1 ,46940   ,708,708,708
BEGIN DESCRIPTION:
Indian Field Swamp 94.0
END DESCRIPTION:
XS GIS Cut Line= 3
      2155039.33       486663.98      2153079.06       486663.98
      2151105.53       486663.98
#Sta/Elev= 30
  3034.3   75.07  3134.3   72.24  3254.3   72.78  3404.3   70.72  3484.3   68.29
  3644.3   60.31  3694.3   61.27  3874.3   61.15  4674.3   59.36  4824.3   59.53
  4854.3    60.5  4884.3   59.54  4954.3   59.97  4964.3   59.49  4968.6   56.74
  4970.1   53.74  5029.9   53.74  5031.4   56.74  5034.6    60.5  5174.6      59
  5374.6   59.14  5384.6      60  5414.6   58.95  6014.6   58.77  6044.6   59.61
  6144.6   65.89  6374.6   67.86  6514.6   66.97  6634.6   70.76  6968.1   74.03
#Mann= 3 ,-1,0
  3034.3     .15       0  4968.6    .045       0  5031.4     .15       0
Bank Sta=4968.6,5031.4
XS Rating Curve= 0 ,0
Exp/Cntr=0.5,0.3

Type RM Length L Ch R = 1 ,46232   ,172,172,172
BEGIN DESCRIPTION:
Highway 78 at Indian Field - US
END DESCRIPTION:
XS GIS Cut Line= 6
      2154905.63       485431.82       2154431.2       485669.72
      2153912.43       485819.86      2152548.03       486092.77
      2151774.41       486119.06      2150766.09       485979.59
#Sta/Elev= 30
  3193.5    73.1  3734.2   72.25  3764.2      69  3784.2   71.08  3864.2   71.01
  3884.2   68.34  3894.2   69.58  3944.2   66.88  4204.2   62.23  4244.2   64.88
  4294.3   60.35  4354.3   59.02  4844.3   59.11  4934.3   61.14  4951.5   58.89
    4958   53.33    5042   53.33  5048.5   58.83  5138.4   60.91  5188.4   59.26
  5836.1   59.12  5896.1   60.58  5916.1   59.03  6171.1   59.03  6562.6   63.05
  6632.6   65.72  6742.6   64.77  6852.6   69.84  6952.6   67.92  7450.5    77.5
#Mann= 3 ,-1,0
  3193.5     .14       0  4951.5    .045       0  5048.5     .14       0
#XS Ineff= 2 , 0
       0  4881.5   69.56  5118.5       0   69.34
Permanent Ineff=
       F       F
Bank Sta=4951.5,5048.5
XS Rating Curve= 0 ,0
Exp/Cntr=0.5,0.3

Type RM Length L Ch R = 3 ,46143   ,,,
BEGIN DESCRIPTION:
Highway 78 at Indian Field - TOR
Structure ID: LDS_IFS_03
Approximate Survey Structure
END DESCRIPTION:
Bridge Culvert--1,0,-1,-1, 0
Deck Dist Width WeirC Skew NumUp NumDn MinLoCord MaxHiCord MaxSubmerge Is_Ogee
65.5,47,3,0, 60, 60, , , 0.95, 0, 1,1,,
  3129.4  3289.4  3429.4  3704.2  3884.2  3934.2  3999.6  4219.6  4616.4  4696.4
  4716.4  4886.4    4947    4947    5053    5053  5100.1  5110.1  5150.1  5230.1
  5624.1  6357.8  6362.1  6462.1  6690.7  6700.7  6740.7  6750.7  6760.7  6810.1
  7010.1  7020.1  7040.1  7050.1  7060.1  7070.1  7156.9  7186.9  7196.9  7206.9
  7226.9  7246.9  7256.9  7276.9  7286.9  7306.9  7316.9  7336.9  7356.9  7376.9
  7386.9  7396.9  7406.9  7416.9  7436.9  7456.9  7476.9  7486.9  7496.9  7499.2
   74.89   74.36   73.27   72.21   70.95   70.96   70.56   69.78   69.27   69.35
   69.55   69.56   68.63   68.63   68.63   68.63   69.61   69.63   69.29   69.16
   69.45   69.16   68.98   68.98   69.41   69.59   69.66   69.92   69.76   70.06
    72.6   72.38   72.71   72.54   72.77   72.61   73.39    73.4   73.59   73.37
   73.56   73.33   73.59   73.02   73.58   73.44   74.12   74.25   77.02   76.46
   75.08   76.16   76.71   75.53   77.59    76.4   76.25      78   78.68   78.67
   33.33   33.33   33.33   33.33   33.33   33.33   33.33   33.33   33.33   33.33
   33.33   33.33   33.33   67.13   67.13   33.33   33.33   33.33   33.33   33.33
   33.33   33.33   33.33   33.33   33.33   33.33   33.33   33.33   33.33   33.33
   33.33   33.33   33.33   33.33   33.33   33.33   33.33   33.33   33.33   33.33
   33.33   33.33   33.33   33.33   33.33   33.33   33.33   33.33   33.33   33.33
   33.33   33.33   33.33   33.33   33.33   33.33   33.33   33.33   33.33   33.33
  3129.4  3289.4  3429.4  3704.2  3884.2  3934.2  3999.6  4219.6  4616.4  4696.4
  4716.4  4886.4    4947    4947    5053    5053  5100.1  5110.1  5150.1  5230.1
  5624.1  6357.8  6362.1  6462.1  6690.7  6700.7  6740.7  6750.7  6760.7  6810.1
  7010.1  7020.1  7040.1  7050.1  7060.1  7070.1  7156.9  7186.9  7196.9  7206.9
  7226.9  7246.9  7256.9  7276.9  7286.9  7306.9  7316.9  7336.9  7356.9  7376.9
  7386.9  7396.9  7406.9  7416.9  7436.9  7456.9  7476.9  7486.9  7496.9  7499.2
   74.89   74.36   73.27   72.21   70.95   70.96   70.56   69.78   69.27   69.35
   69.55   69.56   68.63   68.63   68.63   68.63   69.61   69.63   69.29   69.16
   69.45   69.16   68.98   68.98   69.41   69.59   69.66   69.92   69.76   70.06
    72.6   72.38   72.71   72.54   72.77   72.61   73.39    73.4   73.59   73.37
   73.56   73.33   73.59   73.02   73.58   73.44   74.12   74.25   77.02   76.46
   75.08   76.16   76.71   75.53   77.59    76.4   76.25      78   78.68   78.67
   33.33   33.33   33.33   33.33   33.33   33.33   33.33   33.33   33.33   33.33
   33.33   33.33   33.33   67.13   67.13   33.33   33.33   33.33   33.33   33.33
   33.33   33.33   33.33   33.33   33.33   33.33   33.33   33.33   33.33   33.33
   33.33   33.33   33.33   33.33   33.33   33.33   33.33   33.33   33.33   33.33
   33.33   33.33   33.33   33.33   33.33   33.33   33.33   33.33   33.33   33.33
   33.33   33.33   33.33   33.33   33.33   33.33   33.33   33.33   33.33   33.33
Pier Skew, UpSta & Num, DnSta & Num=  ,4960.3, 2 ,4960.3, 2 , 0 , 0 , 0 ,0,0
     1.5     1.5
   53.33   67.13
     1.5     1.5
   53.08   67.13
Pier Skew, UpSta & Num, DnSta & Num=  ,4986.8, 2 ,4986.8, 2 , 0 , 0 , 0 ,0,0
     1.5     1.5
   53.33   67.13
     1.5     1.5
   53.08   67.13
Pier Skew, UpSta & Num, DnSta & Num=  ,5013.3, 2 ,5013.3, 2 , 0 , 0 , 0 ,0,0
     1.5     1.5
   53.33   67.13
     1.5     1.5
   53.08   67.13
Pier Skew, UpSta & Num, DnSta & Num=  ,5039.8, 2 ,5039.8, 2 , 0 , 0 , 0 ,0,0
     1.5     1.5
   53.33   67.13
     1.5     1.5
   53.08   67.13
Abutment Skew #Up #Dn= , 2 , 2
    4947    4958
   67.13   53.33
    4947    4958
   67.13   53.08
Abutment Skew #Up #Dn= , 2 , 2
    5042    5053
   53.33   67.13
    5042    5053
   53.08   67.13
BR Coef= 1 , 1 , 0 ,1.25, 0 ,,,0.8,0,2,0,
WSPro=,,,, 1 ,,,, 0 ,,,, 0 ,,,,-1 ,-1 ,-1 , 0 , 0 , 0 , 0 , 0
BC Design=,, 0 ,, 0 ,,,,,,
BC HTab HWMax=77.5
BC Use User HTab Curves=0
BC User HTab FreeFlow(D)= 0

Type RM Length L Ch R = 1 ,46060   ,457,457,457
BEGIN DESCRIPTION:
Highway 78 at Indian Field - DS
END DESCRIPTION:
XS GIS Cut Line= 6
      2154834.12       485328.93       2154330.1       485551.29
      2153828.72       485695.17      2152239.22       485994.47
       2151533.5        485950.3      2150844.49       485830.45
#Sta/Elev= 30
    3275    72.8    3515   71.95    3795   68.77  3975.9   69.15  4215.9    65.2
  4315.9   61.07  4407.5   58.95  4687.5    58.6  4767.5   60.32  4787.5   58.94
  4857.5    58.8  4927.5   60.14  4951.5   58.58    4958   53.08    5042   53.08
  5048.5   58.67  5058.8   60.02  5228.8   58.82  5568.8   59.39  5638.8   58.24
  5773.4   59.13    6095   58.32    6275   59.78  6626.9   64.55  6703.3   66.96
  7033.3   71.01  7043.3   71.53  7063.3   75.37  7293.3   76.85  7372.7    78.5
#Mann= 3 ,-1,0
    3275     .14       0  4951.5    .045       0  5048.5     .14       0
#XS Ineff= 2 , 0
       0  4887.5   69.55  5112.5       0   69.55
Permanent Ineff=
       F       F
Bank Sta=4951.5,5048.5
XS Rating Curve= 0 ,0
Exp/Cntr=0.5,0.3

Type RM Length L Ch R = 1 ,45603   ,493,493,493
BEGIN DESCRIPTION:
Indian Field Swamp 91.0
END DESCRIPTION:
XS GIS Cut Line= 3
      2154850.26       485120.64      2153137.46       485358.37
       2151727.2       485508.09
#Sta/Elev= 30
  3270.3    69.4  3370.3   71.14  3630.3   71.55  3870.3    66.1  4100.3    58.3
  4200.3    58.6  4230.3   59.89  4310.3   58.13  4340.3   60.32  4360.3   58.48
  4460.3   58.06  4500.3   59.28  4520.3   58.19  4900.3   59.73  4960.3   58.97
  4966.7   55.98  4968.2   52.98  5031.8   52.98  5033.3   55.98  5169.5   59.29
  5759.5   58.25  5809.5   59.25  5819.5   58.01  5969.5   59.04  6039.5   57.99
  6089.5   60.15  6249.5   61.22  6259.5   61.75  6299.5   68.39  6417.7   72.17
#Mann= 3 ,-1,0
  3270.3     .15       0  4966.7    .045       0  5033.3     .15       0
Bank Sta=4966.7,5033.3
XS Rating Curve= 0 ,0
Exp/Cntr=0.5,0.3

Type RM Length L Ch R = 1 ,45110   ,98,98,98
BEGIN DESCRIPTION:
Railroad at Indian Field - US
END DESCRIPTION:
XS GIS Cut Line= 6
      2155631.11       484096.08      2155555.64       484170.72
      2154364.91         484495.      2152998.56       484884.78
      2151975.48       485185.17      2151676.68       485230.47
#Sta/Elev= 30
  2241.7   74.74  2261.7   73.06  2291.7   67.29  2547.8   64.57    2680   60.82
    2730   62.07    2750   60.62    3300   58.58    3520   60.89    3582      59
    3932   57.78    4152   57.86    4212   59.77    4232   58.03  4458.7    59.8
  4967.5    58.5  4987.5    55.5  5012.5    55.5  5032.5    58.5  5502.8   57.89
  5664.9    59.8  5744.9   58.12  5854.9   62.52  5984.9   63.22  6044.9   68.17
  6079.1   74.65  6169.1   66.41  6209.1   65.19  6269.1   67.26  6371.3   75.61
#Mann= 3 ,-1,0
  2241.7     .15       0  4967.5    .045       0  5032.5     .15       0
#XS Ineff= 2 , 0
       0    4919   70.67    5081       0   70.49
Permanent Ineff=
       F       F
Bank Sta=4967.5,5032.5
XS Rating Curve= 0 ,0
Exp/Cntr=0.5,0.3

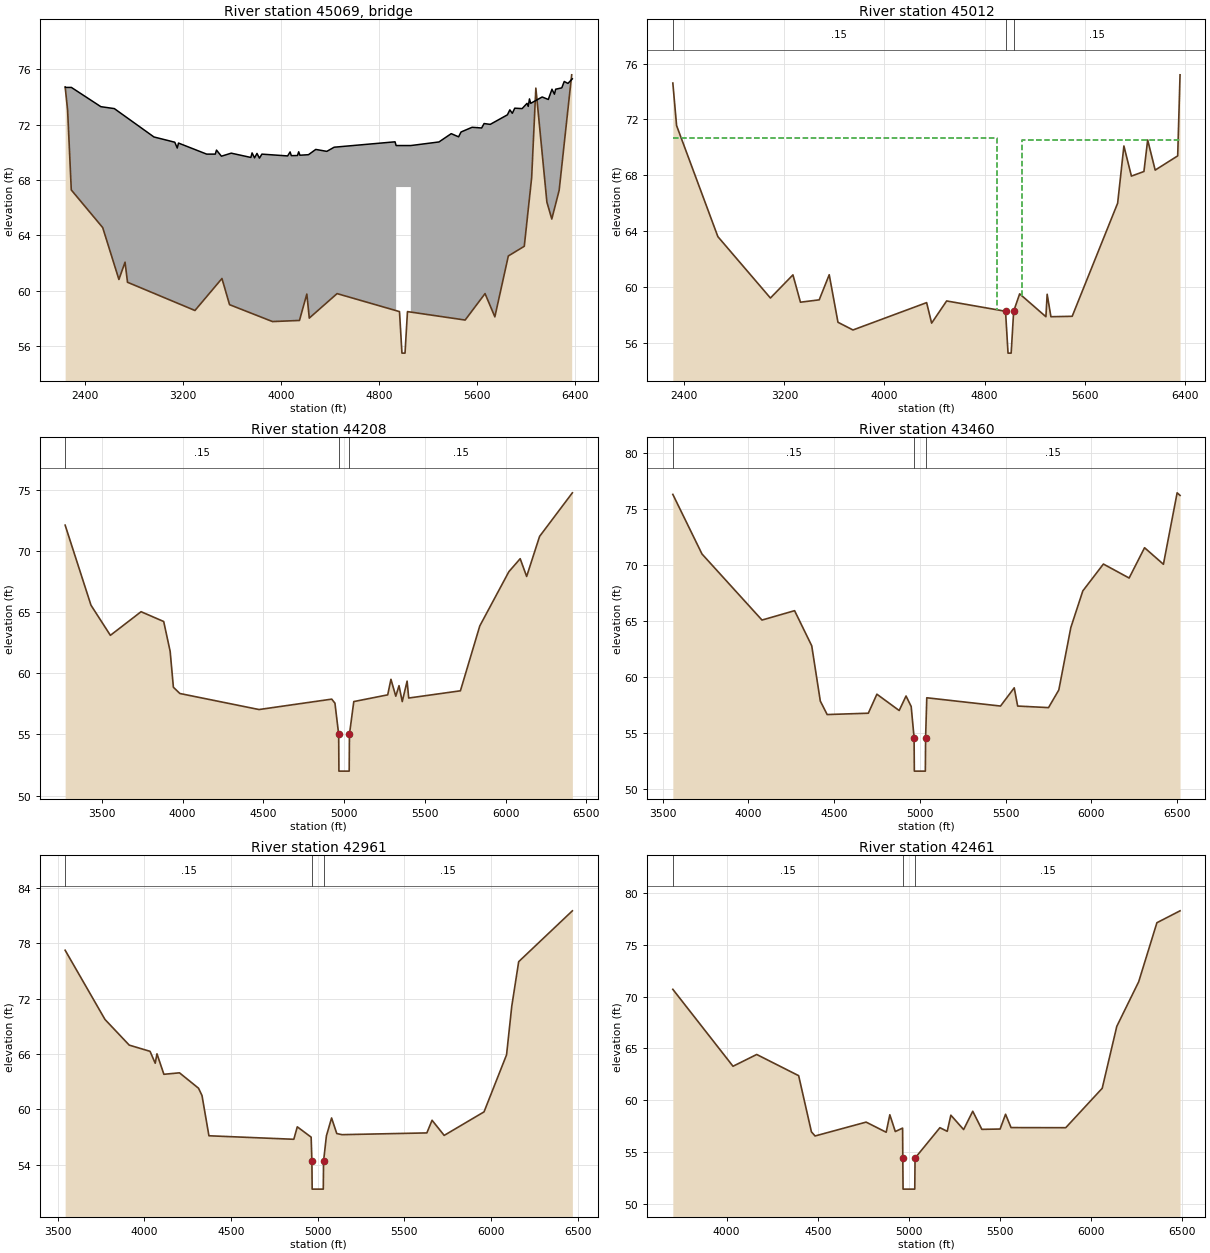
Type RM Length L Ch R = 3 ,45069   ,,,
BEGIN DESCRIPTION:
Railroad at Indian Field - TOR
Structure ID: LDS_IFS_RR
Approximate Survey Structure
END DESCRIPTION:
Bridge Culvert--1,0,-1,-1, 0
Deck Dist Width WeirC Skew NumUp NumDn MinLoCord MaxHiCord MaxSubmerge Is_Ogee
21,40,3,0, 60, 60, , , 0.95, 0, 1,1,,
    2244  2292.6  2532.6  2642.6  2965.6  3135.6  3155.6  3165.6  3395.6  3465.6
  3475.6  3515.6  3595.6  3755.6  3765.6  3785.6  3805.6  3825.6  3845.6  4055.6
  4075.6  4085.6  4135.6  4145.6  4155.6  4225.6  4284.8  4374.8  4434.8  4931.1
    4940    4940    5060    5060  5289.2  5389.2  5449.2  5469.2  5559.2  5637.1
  5657.1  5707.1  5847.1  5867.1  5887.1  5907.1  5967.1  6007.1  6017.1  6027.1
  6037.1  6130.5  6180.5  6210.5  6230.5  6240.5  6290.5  6310.5  6340.5  6376.8
    74.7    74.7   73.31   73.17   71.12   70.74   70.32   70.68   69.88   69.88
   70.17   69.73   69.95   69.64   69.97   69.61   69.93   69.59   69.88   69.75
   70.04   69.77   69.78   70.05    69.8   69.84   70.22   70.08   70.38   70.77
    70.5    70.5    70.5    70.5   70.76   71.36   71.13   71.48   71.82   71.77
   72.09   72.03   72.72   73.08   72.83    73.2   73.17   73.55   73.33   73.87
   73.55   74.01   73.83   74.57   74.21   74.57   74.67   75.13   74.99   75.32
    35.5    35.5    35.5    35.5    35.5    35.5    35.5    35.5    35.5    35.5
    35.5    35.5    35.5    35.5    35.5    35.5    35.5    35.5    35.5    35.5
    35.5    35.5    35.5    35.5    35.5    35.5    35.5    35.5    35.5    35.5
    35.5    67.5    67.5    35.5    35.5    35.5    35.5    35.5    35.5    35.5
    35.5    35.5    35.5    35.5    35.5    35.5    35.5    35.5    35.5    35.5
    35.5    35.5    35.5    35.5    35.5    35.5    35.5    35.5    35.5    35.5
    2244  2292.6  2532.6  2642.6  2965.6  3135.6  3155.6  3165.6  3395.6  3465.6
  3475.6  3515.6  3595.6  3755.6  3765.6  3785.6  3805.6  3825.6  3845.6  4055.6
  4075.6  4085.6  4135.6  4145.6  4155.6  4225.6  4284.8  4374.8  4434.8  4931.1
    4940    4940    5060    5060  5289.2  5389.2  5449.2  5469.2  5559.2  5637.1
  5657.1  5707.1  5847.1  5867.1  5887.1  5907.1  5967.1  6007.1  6017.1  6027.1
  6037.1  6130.5  6180.5  6210.5  6230.5  6240.5  6290.5  6310.5  6340.5  6376.8
    74.7    74.7   73.31   73.17   71.12   70.74   70.32   70.68   69.88   69.88
   70.17   69.73   69.95   69.64   69.97   69.61   69.93   69.59   69.88   69.75
   70.04   69.77   69.78   70.05    69.8   69.84   70.22   70.08   70.38   70.77
    70.5    70.5    70.5    70.5   70.76   71.36   71.13   71.48   71.82   71.77
   72.09   72.03   72.72   73.08   72.83    73.2   73.17   73.55   73.33   73.87
   73.55   74.01   73.83   74.57   74.21   74.57   74.67   75.13   74.99   75.32
    35.5    35.5    35.5    35.5    35.5    35.5    35.5    35.5    35.5    35.5
    35.5    35.5    35.5    35.5    35.5    35.5    35.5    35.5    35.5    35.5
    35.5    35.5    35.5    35.5    35.5    35.5    35.5    35.5    35.5    35.5
    35.5    67.5    67.5    35.5    35.5    35.5    35.5    35.5    35.5    35.5
    35.5    35.5    35.5    35.5    35.5    35.5    35.5    35.5    35.5    35.5
    35.5    35.5    35.5    35.5    35.5    35.5    35.5    35.5    35.5    35.5
Abutment Skew #Up #Dn= , 2 , 2
    4940    4960
    67.5    58.5
    4940    4960
    67.5    58.4
Abutment Skew #Up #Dn= , 2 , 2
    5040    5060
    58.7    67.5
    5040    5060
    58.3    67.5
BR Coef= 1 , 1 , 0 ,1.25, 0 ,,,0.8,0,2,0,
WSPro=,,,, 1 ,,,, 0 ,,,, 0 ,,,,-1 ,-1 ,-1 , 0 , 0 , 0 , 0 , 0
BC Design=,, 0 ,, 0 ,,,,,,
BC HTab HWMax=75.61
BC Use User HTab Curves=0
BC User HTab FreeFlow(D)= 0

Type RM Length L Ch R = 1 ,45012   ,804,804,804
BEGIN DESCRIPTION:
Railroad at Indian Field - DS
END DESCRIPTION:
XS GIS Cut Line= 6
      2155585.67        484094.2      2155163.49       484187.34
       2154846.8       484271.54      2152984.91       484787.55
      2152429.67       484966.66      2151681.63       485183.31
#Sta/Elev= 30
  2308.2   74.61  2338.2   71.56  2668.2    63.6  3088.2    59.2  3268.2   60.86
  3328.2    58.9  3478.2   59.07  3558.2   60.87  3628.2   57.46  3748.2   56.91
  4336.8   58.87  4376.8    57.4  4496.8   58.99  4967.5   58.25  4987.5   55.25
  5012.5   55.25  5032.5   58.25  5080.3    59.5  5290.3   57.86  5300.3   59.47
  5330.3   57.86  5500.3   57.89  5863.7      66  5913.7    70.1  5973.7   67.94
  6073.7   68.27  6103.7   70.53  6163.7   68.37  6343.7   69.39  6362.5    75.2
#Mann= 3 ,-1,0
  2308.2     .15       0  4967.5    .045       0  5032.5     .15       0
#XS Ineff= 2 , 0
       0    4903   70.66    5097       0   70.53
Permanent Ineff=
       F       F
Bank Sta=4967.5,5032.5
XS Rating Curve= 0 ,0
Exp/Cntr=0.5,0.3

Type RM Length L Ch R = 1 ,44208   ,748,748,748
BEGIN DESCRIPTION:
Indian Field Swamp 88.0
END DESCRIPTION:
XS GIS Cut Line= 3
      2155041.14       483700.69      2153368.45       484086.45
      2151945.44       484086.45
#Sta/Elev= 30
  3273.6   72.09  3433.6   65.55  3553.6   63.09  3743.6   65.02  3883.6   64.22
  3923.6   61.78  3943.6   58.85  3983.6   58.34  4473.6   57.03  4923.6   57.88
  4943.6   57.55  4966.7      55  4968.2      52  5031.8      52  5033.3      55
  5060.2   57.68  5270.2   58.23  5290.2    59.5  5320.2   58.12  5340.2   58.98
  5360.2   57.68  5390.2   59.35  5400.2   57.97  5720.2   58.56  5840.2   63.86
  6020.2   68.29  6090.2   69.35  6130.2    67.9  6210.2   71.17  6413.2   74.73
#Mann= 3 ,-1,0
  3273.6     .15       0  4966.7    .045       0  5033.3     .15       0
Bank Sta=4966.7,5033.3
XS Rating Curve= 0 ,0
Exp/Cntr=0.3,0.1

Type RM Length L Ch R = 1 ,43460   ,499,499,499
BEGIN DESCRIPTION:
Indian Field Swamp 87.0
END DESCRIPTION:
XS GIS Cut Line= 3
      2155066.79       483518.94      2153631.03       483396.11
      2152119.01       483273.29
#Sta/Elev= 30
  3559.5   76.34  3729.5   71.01  4079.5    65.1  4269.5   65.94  4369.5    62.8
  4419.5   57.86  4459.5   56.65  4699.5   56.77  4749.5   58.47  4879.5   57.01
  4919.5   58.31  4949.5   57.37  4966.4   54.59  4967.9   51.59  5032.1   51.59
  5033.6   54.59  5040.5   58.15  5470.5   57.41  5550.5   59.04  5570.5   57.41
  5750.5   57.27  5810.5   58.85  5880.5   64.43  5950.5   67.71  6070.5   70.11
  6220.5   68.86  6310.5   71.57  6420.5   70.09  6500.5   76.48  6517.5   76.25
#Mann= 3 ,-1,0
  3559.5     .15       0  4966.4    .045       0  5033.6     .15       0
Bank Sta=4966.4,5033.6
XS Rating Curve= 0 ,0
Exp/Cntr=0.3,0.1

Type RM Length L Ch R = 1 ,42961   ,500,500,500
BEGIN DESCRIPTION:
Indian Field Swamp 86.0
END DESCRIPTION:
XS GIS Cut Line= 3
      2155155.71       483133.53      2153715.76       482904.82
       2152263.1       482680.37
#Sta/Elev= 30
    3542   77.23    3772   69.73    3912   66.95    4032   66.28    4062   64.99
    4072   66.01    4112   63.79    4202   63.95    4312   62.28    4332   61.49
    4372   57.13    4862   56.75    4882    58.1    4962   56.98  4966.4   54.35
  4967.9   51.35  5032.1   51.35  5033.6   54.35    5050   57.11    5080   59.06
    5110   57.37    5140   57.25    5630   57.44    5660   58.81    5730   57.17
    5960   59.72    6090    65.9    6120   71.15    6160   75.99  6469.9    81.5
#Mann= 3 ,-1,0
    3542     .15       0  4966.4    .045       0  5033.6     .15       0
Bank Sta=4966.4,5033.6
XS Rating Curve= 0 ,0
Exp/Cntr=0.3,0.1

Type RM Length L Ch R = 1 ,42461   ,500,500,500
BEGIN DESCRIPTION:
Indian Field Swamp 85.0
END DESCRIPTION:
XS GIS Cut Line= 3
      2155089.99       482492.79      2153797.83       482411.69
      2152316.31       482285.38
#Sta/Elev= 30
  3705.3   70.71  4035.3   63.27  4165.3   64.41  4395.3   62.36  4465.3   56.93
  4485.3   56.53  4765.3   57.87  4875.3   56.89  4895.3   58.58  4925.3   56.96
  4965.3   57.29  4966.4   54.39  4967.9   51.39  5032.1   51.39  5033.6   54.39
    5170   57.33    5210   56.98    5230   58.54    5300   57.15    5350   58.92
    5400   57.17    5500    57.2    5530   58.63    5560   57.34    5860   57.33
    6060   61.14    6140   67.13    6260   71.44    6360   77.15  6486.9    78.3
#Mann= 3 ,-1,0
  3705.3     .15       0  4966.4    .045       0  5033.6     .15       0
Bank Sta=4966.4,5033.6
XS Rating Curve= 0 ,0
Exp/Cntr=0.3,0.1

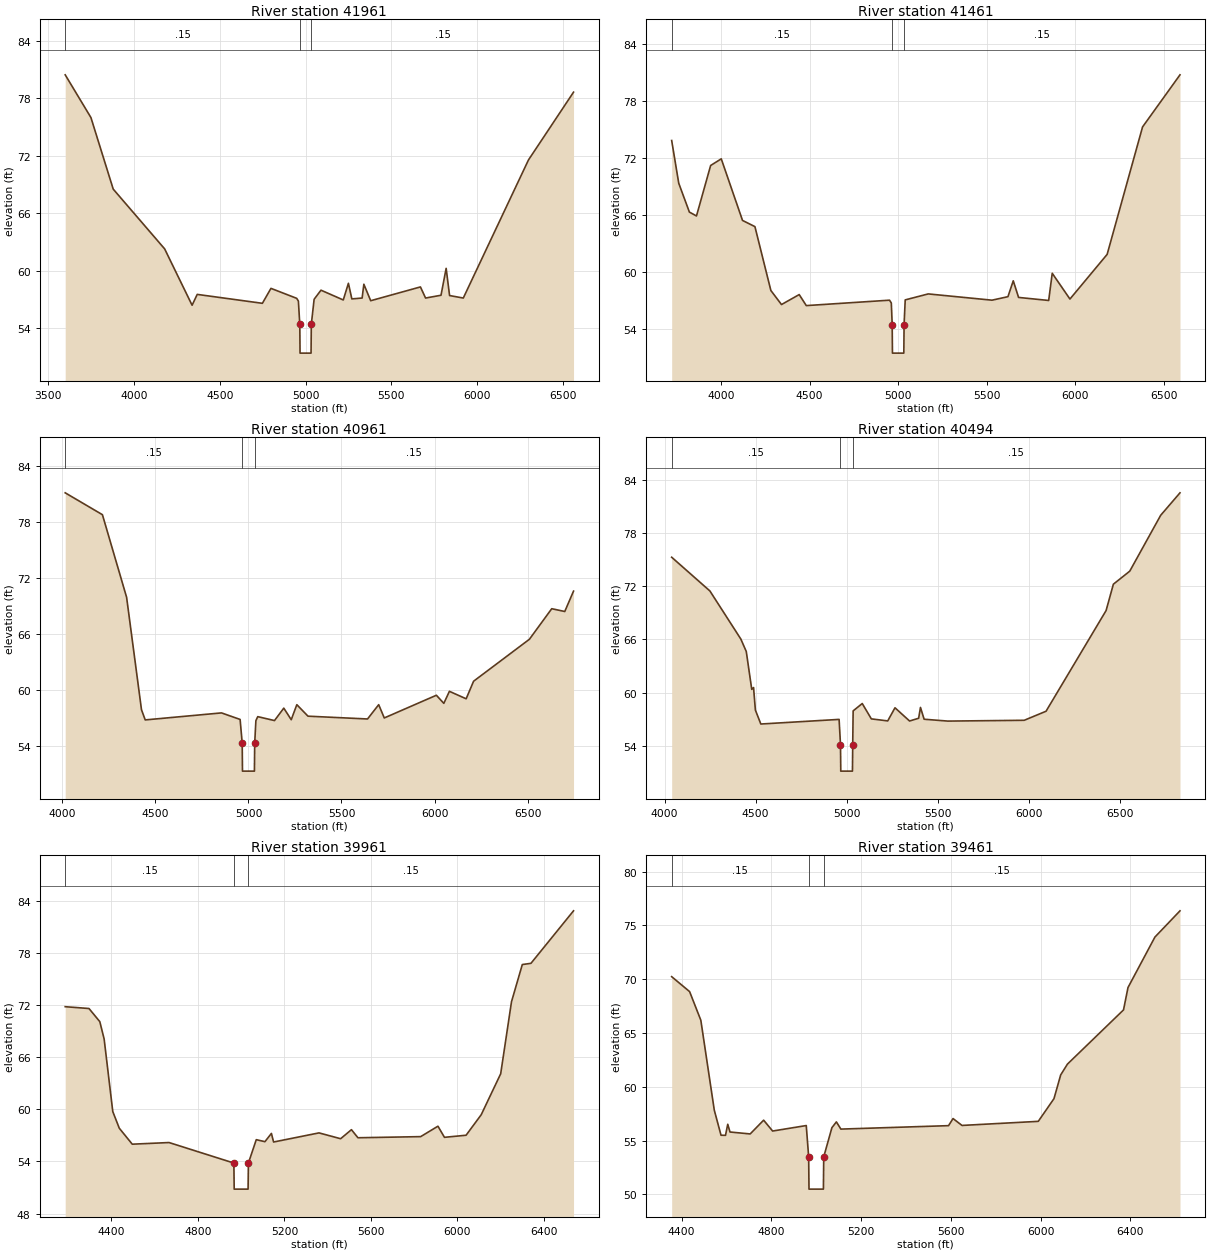
Type RM Length L Ch R = 1 ,41961   ,500,500,500
BEGIN DESCRIPTION:
Indian Field Swamp 84.0
END DESCRIPTION:
XS GIS Cut Line= 3
      2155248.87       481918.03      2153847.17       481914.13
      2152284.28       481918.03
#Sta/Elev= 30
  3598.3   80.44  3748.3   75.98  3878.3   68.51  4178.3   62.27  4338.3   56.39
  4368.3   57.52  4748.3   56.59  4798.3   58.15  4948.3   57.11  4958.3   56.82
  4966.4   54.39  4967.9   51.39  5032.1   51.39  5033.6   54.39    5050   57.01
    5090   57.96    5220   56.94    5250   58.68    5270   57.05    5330   57.14
    5340   58.58    5380   56.86    5670    58.3    5700   57.14    5790   57.43
    5820   60.24    5840    57.4    5920   57.14    6300   71.55  6562.9   78.63
#Mann= 3 ,-1,0
  3598.3     .15       0  4966.4    .045       0  5033.6     .15       0
Bank Sta=4966.4,5033.6
XS Rating Curve= 0 ,0
Exp/Cntr=0.3,0.1

Type RM Length L Ch R = 1 ,41461   ,500,500,500
BEGIN DESCRIPTION:
Indian Field Swamp 83.0
END DESCRIPTION:
XS GIS Cut Line= 3
      2155179.44       481415.05      2153900.94       481417.07
      2152309.64       481414.04
#Sta/Elev= 30
  3721.5   73.81  3761.5   69.31  3821.5   66.28  3861.5   65.87  3941.5   71.18
  4001.5   71.88  4121.5    65.4  4191.5   64.75  4281.5   58.03  4341.5   56.55
  4441.5    57.6  4481.5   56.44  4951.5   57.01  4961.5   56.71  4966.4   54.44
  4967.9   51.44  5032.1   51.44  5033.6   54.44    5040   57.04    5170   57.67
    5530   57.01    5620   57.38    5650   59.05    5680    57.3    5850   56.98
    5870   59.84    5970   57.13    6180   61.83    6380   75.24  6591.3   80.72
#Mann= 3 ,-1,0
  3721.5     .15       0  4966.4    .045       0  5033.6     .15       0
Bank Sta=4966.4,5033.6
XS Rating Curve= 0 ,0
Exp/Cntr=0.3,0.1

Type RM Length L Ch R = 1 ,40961   ,467,467,467
BEGIN DESCRIPTION:
Indian Field Swamp 82.0
END DESCRIPTION:
XS GIS Cut Line= 3
      2154948.16       480922.75      2153963.36       480920.98
       2152230.9       481146.63
#Sta/Elev= 30
  4015.2   81.08  4215.2   78.74  4345.2    69.9  4425.2   57.87  4445.2   56.78
  4855.2   57.53  4955.2   56.83  4966.4    54.3  4967.9    51.3  5032.1    51.3
  5033.6    54.3    5040    56.7    5050   57.13    5140   56.71    5190   58.04
    5230    56.8    5260   58.41    5320   57.18    5640   56.88    5700   58.41
    5730   56.99    6010   59.42    6050   58.55    6080   59.84    6170   59.04
    6210   60.92    6510   65.41    6630   68.68    6700   68.38  6747.1   70.56
#Mann= 3 ,-1,0
  4015.2     .15       0  4966.4    .045       0  5033.6     .15       0
Bank Sta=4966.4,5033.6
XS Rating Curve= 0 ,0
Exp/Cntr=0.3,0.1

Type RM Length L Ch R = 1 ,40494   ,533,533,533
BEGIN DESCRIPTION:
Indian Field Swamp 81.0
END DESCRIPTION:
XS GIS Cut Line= 3
      2154977.81       480557.18      2154025.78       480457.42
      2152203.73       480231.07
#Sta/Elev= 30
  4038.7   75.27  4248.7   71.47  4418.7   66.05  4448.7   64.64  4478.7   60.38
  4488.7   60.58  4498.7   58.04  4528.7   56.47  4958.7   56.99  4966.4   54.16
  4967.9   51.16  5032.1   51.16  5033.6   54.16  5035.9   57.95  5085.9   58.78
  5135.9   57.05  5225.9   56.82  5265.9    58.3  5345.9   56.81  5395.9   57.12
  5405.9   58.34  5425.9   57.01  5555.9    56.8  5975.9   56.89  6095.9   57.91
  6425.9   69.26  6465.9   72.23  6555.9    73.7  6725.9      80    6832   82.53
#Mann= 3 ,-1,0
  4038.7     .15       0  4966.4    .045       0  5033.6     .15       0
Bank Sta=4966.4,5033.6
XS Rating Curve= 0 ,0
Exp/Cntr=0.3,0.1

Type RM Length L Ch R = 1 ,39961   ,500,500,500
BEGIN DESCRIPTION:
Indian Field Swamp 80.0
END DESCRIPTION:
XS GIS Cut Line= 3
      2154897.33         480063.      2154094.88         479930.
      2152584.98       479643.73
#Sta/Elev= 30
  4186.6   71.81  4296.6    71.6  4346.6   70.09  4366.6   68.09  4406.6   59.74
  4436.6   57.83  4496.6   55.99  4666.6   56.18  4966.4   53.82  4967.9   50.82
  5032.1   50.82  5033.6   53.82    5070   56.51    5110   56.28    5140   57.23
    5150   56.24    5360   57.29    5460   56.62    5510   57.66    5540   56.73
    5830   56.86    5910   58.06    5940   56.78    6040   57.02    6110   59.38
    6200   64.09    6250   72.38    6300   76.66    6340    76.8  6536.8   82.84
#Mann= 3 ,-1,0
  4186.6     .15       0  4966.4    .045       0  5033.6     .15       0
Bank Sta=4966.4,5033.6
XS Rating Curve= 0 ,0
Exp/Cntr=0.3,0.1

Type RM Length L Ch R = 1 ,39461   ,610,610,610
BEGIN DESCRIPTION:
Indian Field Swamp 79.0
END DESCRIPTION:
XS GIS Cut Line= 3
      2154838.05       479584.43       2154209.4       479443.29
      2152623.09       479105.86
#Sta/Elev= 30
  4355.7   70.24  4435.7   68.85  4485.7   66.19  4545.7   57.83  4575.7    55.5
  4595.7   55.49  4605.7   56.52  4615.7    55.8  4705.7   55.62  4765.7    56.9
  4805.7   55.89  4955.7    56.4  4966.4   53.49  4967.9   50.49  5032.1   50.49
  5033.6   53.49    5070    56.2    5090   56.74    5110   56.07    5590   56.39
    5610   57.05    5650   56.41    5990   56.79    6060    58.9    6090   61.11
    6120   62.11    6370   67.15    6390   69.23    6510   73.92  6621.8   76.36
#Mann= 3 ,-1,0
  4355.7     .15       0  4966.4    .045       0  5033.6     .15       0
Bank Sta=4966.4,5033.6
XS Rating Curve= 0 ,0
Exp/Cntr=0.3,0.1