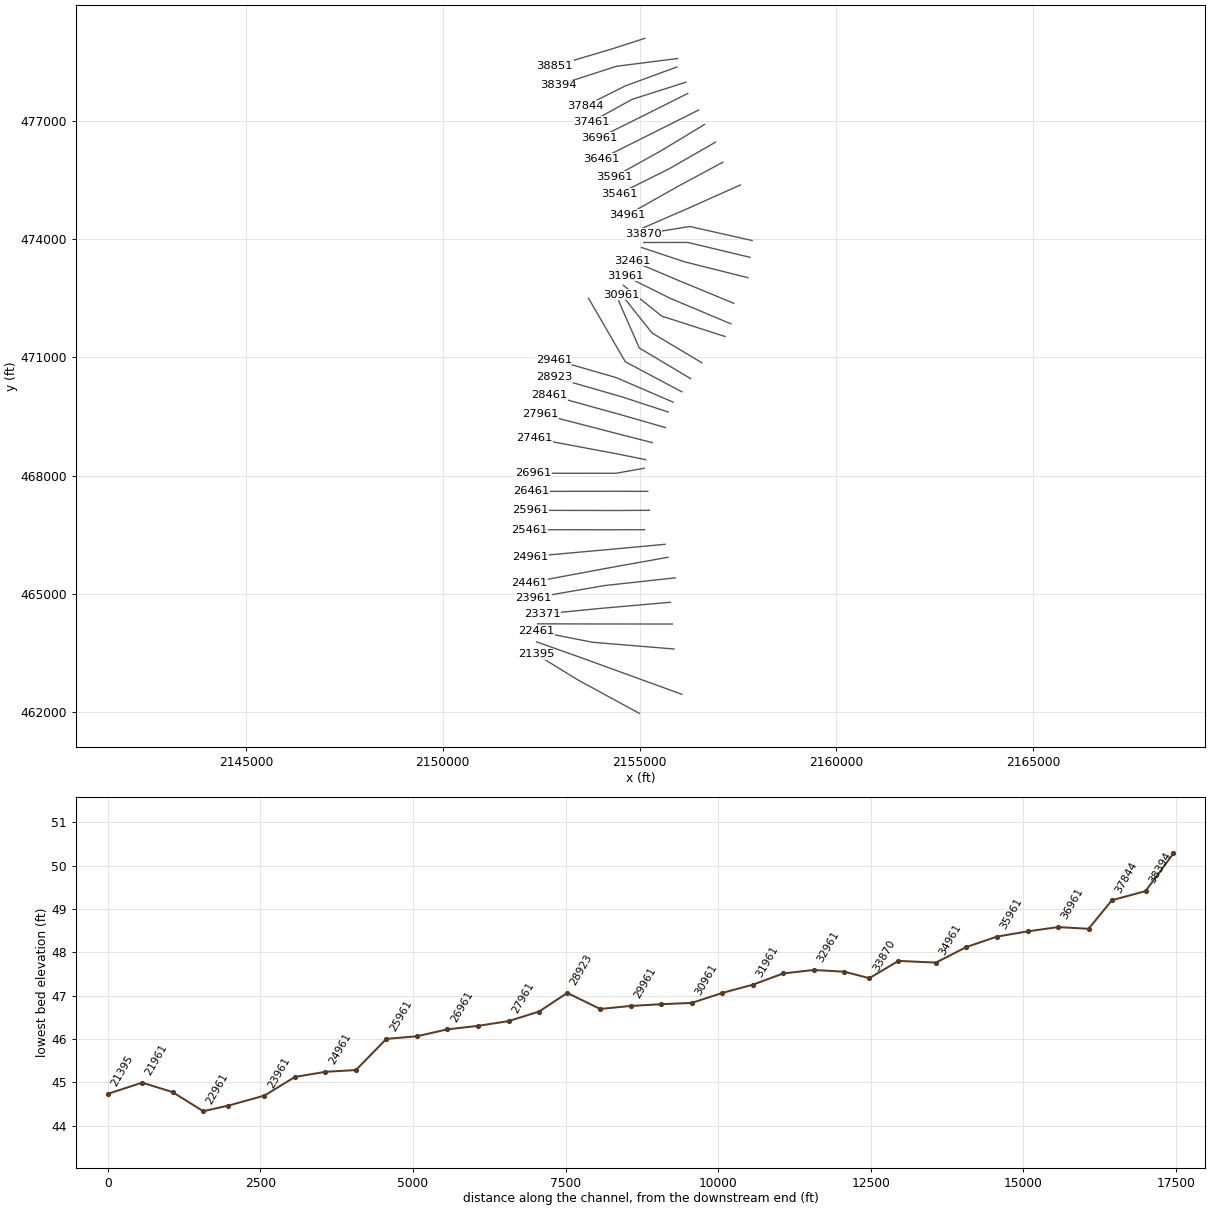
HEC-RAS study IndianFieldsSwamp.prj: S-18-19 over Indian Fields Swamp

--- IndianFieldsSwamp.g02 (geometry) --- (continued)

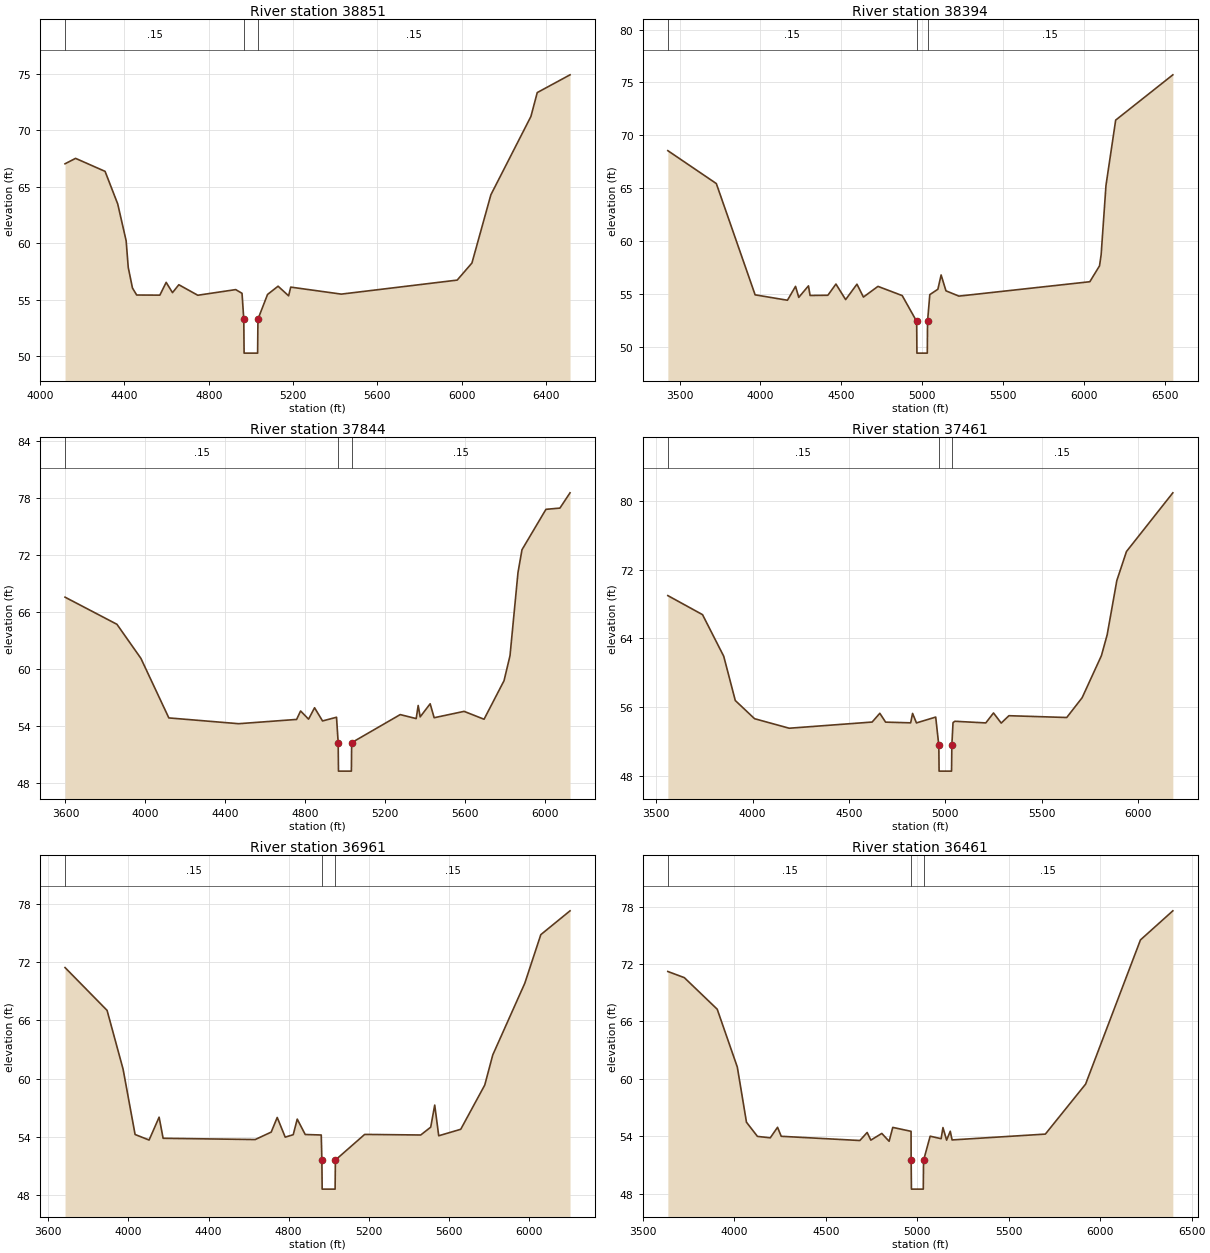
Type RM Length L Ch R = 1 ,38851   ,457,457,457
BEGIN DESCRIPTION:
Indian Field Swamp 78.0
END DESCRIPTION:
XS GIS Cut Line= 3
      2155134.69       479109.07      2154295.96       478839.03
      2152843.26       478407.04
#Sta/Elev= 30
  4118.1   67.03  4168.1   67.51  4308.1   66.36  4368.1   63.48  4408.1   60.22
  4418.1   57.86  4438.1   56.04  4458.1   55.42  4568.1   55.41  4598.1   56.54
  4628.1   55.63  4658.1   56.33  4748.1    55.4  4928.1    55.9  4958.1   55.57
  4966.4   53.28  4967.9   50.28  5032.1   50.28  5033.6   53.28  5079.2   55.47
  5129.2    56.2  5179.2   55.35  5189.2   56.12  5429.2    55.5  5979.2   56.74
  6049.2   58.25  6139.2   64.29  6329.2   71.22  6359.2   73.33  6514.8    74.9
#Mann= 3 ,-1,0
  4118.1     .15       0  4966.4    .045       0  5033.6     .15       0
Bank Sta=4966.4,5033.6
XS Rating Curve= 0 ,0
Exp/Cntr=0.3,0.1

Type RM Length L Ch R = 1 ,38394   ,550,550,550
BEGIN DESCRIPTION:
Indian Field Swamp 77.0
END DESCRIPTION:
XS GIS Cut Line= 3
      2155968.48       478596.65      2154410.31       478398.57
      2152932.26       477920.01
#Sta/Elev= 30
  3426.9   68.55  3726.9   65.44  3966.9   54.92  4166.9   54.41  4216.9   55.72
  4236.9   54.68  4296.9   55.77  4306.9   54.86  4416.9   54.88  4466.9   55.94
  4526.9   54.47  4596.9   55.93  4636.9   54.71  4726.9   55.72  4876.9   54.85
  4966.4   52.41  4967.9   49.41  5032.1   49.41  5033.6   52.41  5047.6   54.94
  5097.6   55.45  5117.6    56.8  5147.6    55.3  5227.6    54.8  6037.6   56.16
  6097.6   57.66  6107.6   58.71  6137.6   65.27  6197.6   71.44  6551.2   75.72
#Mann= 3 ,-1,0
  3426.9     .15       0  4966.4    .045       0  5033.6     .15       0
Bank Sta=4966.4,5033.6
XS Rating Curve= 0 ,0
Exp/Cntr=0.3,0.1

Type RM Length L Ch R = 1 ,37844   ,383,383,383
BEGIN DESCRIPTION:
Indian Field Swamp 76.0
END DESCRIPTION:
XS GIS Cut Line= 3
      2155948.11       478381.09      2154634.77       477898.82
      2153622.59       477394.84
#Sta/Elev= 30
  3597.9   67.54  3857.9   64.68  3977.9   61.09  4117.9   54.81  4467.9    54.2
  4757.9   54.65  4777.9   55.54  4817.9   54.68  4847.9   55.88  4887.9   54.49
  4957.9   54.88  4966.2    52.2  4967.7    49.2  5032.3    49.2  5033.8    52.2
    5277   55.16    5357   54.74    5367   56.12    5377   54.92    5427    56.3
    5447   54.83    5597    55.5    5697   54.67    5797   58.73    5827   61.37
    5867   70.14    5887   72.54    6007    76.8    6077   76.93  6127.7   78.54
#Mann= 3 ,-1,0
  3597.9     .15       0  4966.2    .045       0  5033.8     .15       0
Bank Sta=4966.2,5033.8
XS Rating Curve= 0 ,0
Exp/Cntr=0.3,0.1

Type RM Length L Ch R = 1 ,37461   ,500,500,500
BEGIN DESCRIPTION:
Indian Field Swamp 75.0
END DESCRIPTION:
XS GIS Cut Line= 3
      2156180.59       477996.22      2154808.87        477558.4
      2153775.06       476988.27
#Sta/Elev= 30
  3560.1      69  3740.1   66.78  3850.1   61.93  3910.1   56.77  4010.1   54.65
  4190.1   53.54  4620.1   54.26  4660.1   55.28  4690.1   54.25  4820.1   54.17
  4830.1   55.27  4850.1   54.16  4950.1   54.84  4966.2   51.54  4967.7   48.54
  5032.3   48.54  5033.8   51.54    5040    54.2    5050   54.35    5210   54.16
    5250   55.32    5290   54.14    5330      55    5630   54.79    5710    57.1
    5810      62    5840   64.45    5890   70.76    5940   74.14  6180.6   80.98
#Mann= 3 ,-1,0
  3560.1     .15       0  4966.2    .045       0  5033.8     .15       0
Bank Sta=4966.2,5033.8
XS Rating Curve= 0 ,0
Exp/Cntr=0.3,0.1

Type RM Length L Ch R = 1 ,36961   ,500,500,500
BEGIN DESCRIPTION:
Indian Field Swamp 74.0
END DESCRIPTION:
XS GIS Cut Line= 3
      2156223.02       477708.26      2155045.77       477118.08
      2153965.63       476581.68
#Sta/Elev= 30
  3683.1   71.46  3893.1   67.04  3973.1   60.97  4033.1   54.22  4103.1   53.65
  4153.1   56.01  4173.1   53.83  4633.1    53.7  4713.1   54.47  4743.1   55.98
  4783.1   53.95  4823.1    54.2  4843.1   55.81  4883.1   54.22  4963.1   54.17
  4966.2   51.58  4967.7   48.58  5032.3   48.58  5033.8   51.58    5180   54.23
    5460   54.17    5510   54.98    5530   57.26    5550   54.09    5660   54.76
    5780   59.33    5820   62.44    5980   69.84    6060   74.86    6206   77.32
#Mann= 3 ,-1,0
  3683.1     .15       0  4966.2    .045       0  5033.8     .15       0
Bank Sta=4966.2,5033.8
XS Rating Curve= 0 ,0
Exp/Cntr=0.3,0.1

Type RM Length L Ch R = 1 ,36461   ,500,500,500
BEGIN DESCRIPTION:
Indian Field Swamp 73.0
END DESCRIPTION:
XS GIS Cut Line= 3
      2156502.52       477288.96      2155282.67       476677.77
       2154033.4       476052.28
#Sta/Elev= 30
  3635.6   71.22  3725.6   70.58  3905.6   67.28  4015.6   61.23  4065.6   55.47
  4125.6   53.99  4195.6   53.84  4235.6   54.94  4255.6      54  4685.6   53.56
  4725.6    54.4  4745.6    53.6  4805.6    54.3  4845.6   53.48  4865.6   54.93
  4965.6   54.52  4966.1   51.48  4967.6   48.48  5032.4   48.48  5033.9   51.48
    5070   54.01    5130   53.75    5140   54.91    5160    53.6    5180   54.53
    5190   53.62    5700   54.23    5920   59.45    6220   74.52  6397.1   77.56
#Mann= 3 ,-1,0
  3635.6     .15       0  4966.1    .045       0  5033.9     .15       0
Bank Sta=4966.1,5033.9
XS Rating Curve= 0 ,0
Exp/Cntr=0.3,0.1

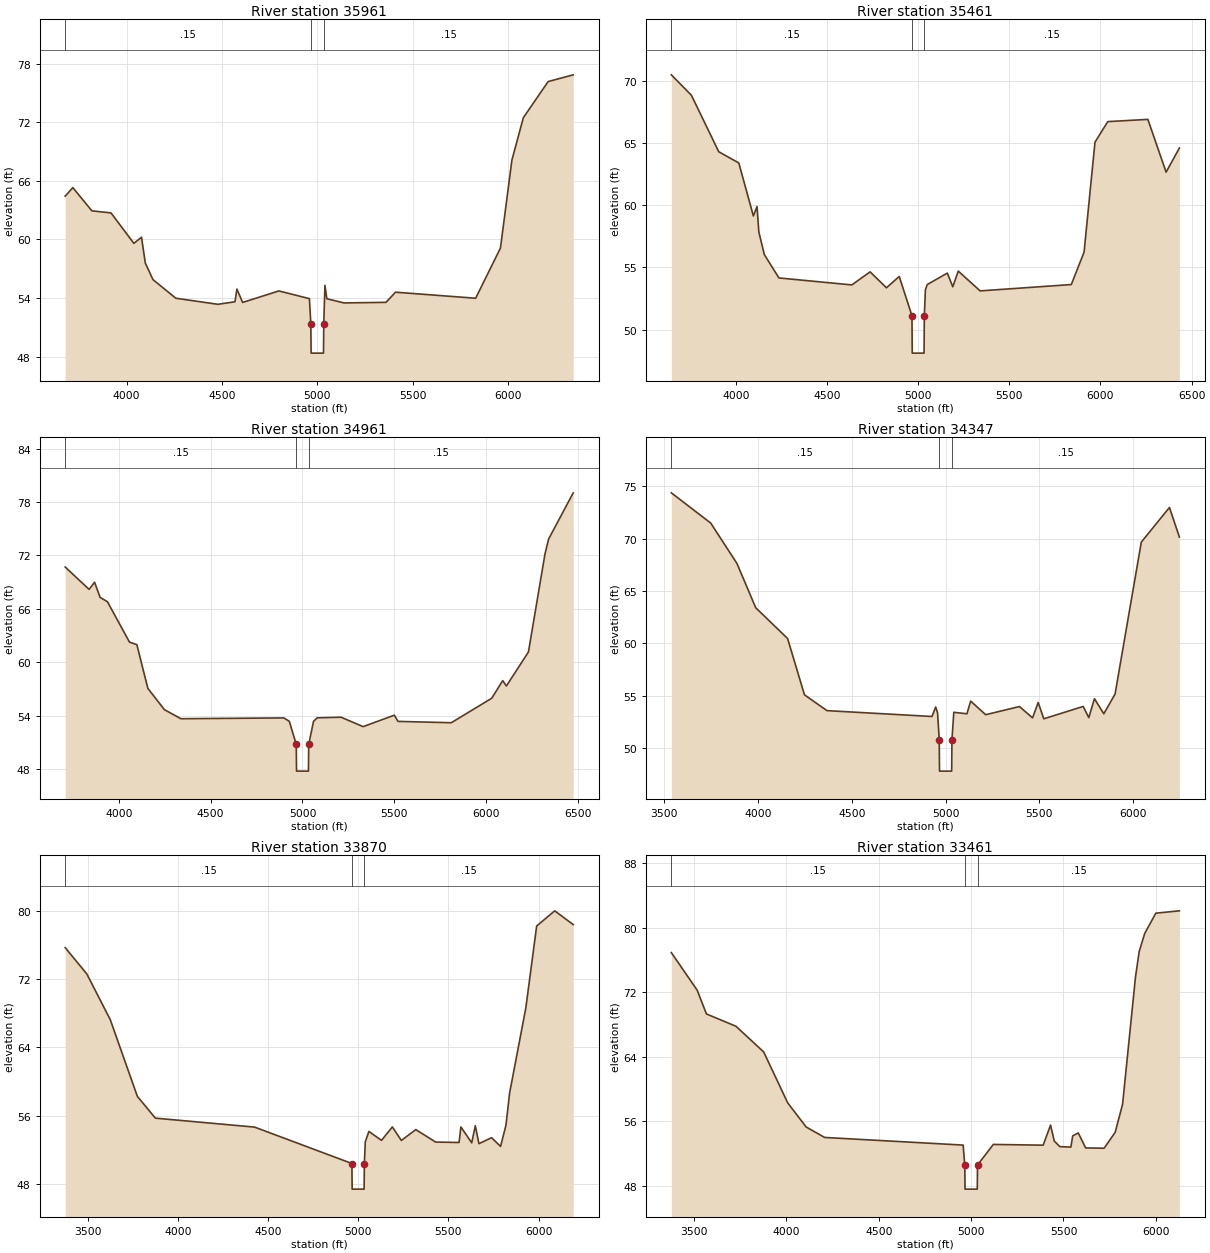
Type RM Length L Ch R = 1 ,35961   ,500,500,500
BEGIN DESCRIPTION:
Indian Field Swamp 72.0
END DESCRIPTION:
XS GIS Cut Line= 3
      2156650.74       476920.49      2155519.57       476237.45
      2154346.76       475586.39
#Sta/Elev= 30
  3678.6   64.44  3718.6   65.31  3818.6   62.93  3918.6   62.72  4038.6    59.6
  4078.6   60.23  4098.6   57.58  4138.6   55.89  4258.6   53.98  4478.6   53.36
  4568.6   53.62  4578.6   54.92  4608.6   53.55  4798.6   54.73  4958.6   53.94
  4966.1   51.36  4967.6   48.36  5032.4   48.36  5033.9   51.36    5040    55.3
    5050   53.93    5140    53.5    5360   53.56    5410    54.6    5830   53.98
    5960   59.12    6020   68.13    6080   72.47    6210   76.17  6341.4   76.86
#Mann= 3 ,-1,0
  3678.6     .15       0  4966.1    .045       0  5033.9     .15       0
Bank Sta=4966.1,5033.9
XS Rating Curve= 0 ,0
Exp/Cntr=0.3,0.1

Type RM Length L Ch R = 1 ,35461   ,500,500,500
BEGIN DESCRIPTION:
Indian Field Swamp 71.0
END DESCRIPTION:
XS GIS Cut Line= 3
      2156930.21       476471.53      2155756.47       475797.13
       2154473.8       475158.62
#Sta/Elev= 30
  3646.3   70.48  3756.3   68.84  3906.3    64.3  4016.3    63.4  4096.3   59.14
  4116.3    59.9  4126.3   57.85  4156.3   56.04  4236.3   54.16  4636.3    53.6
  4736.3   54.65  4826.3   53.37  4896.3   54.28  4966.1   51.12  4967.6   48.12
  5032.4   48.12  5033.9   51.12    5040   53.23    5050   53.63    5160   54.55
    5190   53.45    5220   54.71    5340   53.12    5840   53.63    5910   56.23
    5970   65.07    6040   66.72    6260    66.9    6360   62.66  6432.8    64.6
#Mann= 3 ,-1,0
  3646.3     .15       0  4966.1    .045       0  5033.9     .15       0
Bank Sta=4966.1,5033.9
XS Rating Curve= 0 ,0
Exp/Cntr=0.3,0.1

Type RM Length L Ch R = 1 ,34961   ,614,614,614
BEGIN DESCRIPTION:
Indian Field Swamp 70.0
END DESCRIPTION:
XS GIS Cut Line= 3
      2157115.32       475961.25      2155977.74       475349.16
      2154694.11       474625.03
#Sta/Elev= 30
  3708.2    70.7  3838.2   68.19  3868.2   68.99  3898.2   67.29  3938.2    66.8
  4058.2   62.26  4098.2   61.98  4158.2   57.06  4248.2   54.67  4338.2   53.65
  4898.2   53.74  4928.2   53.36  4966.1   50.76  4967.6   47.76  5032.4   47.76
  5033.9   50.76    5060   53.35    5080   53.75    5210   53.82    5330   52.76
    5500   54.05    5520   53.35    5810    53.2    6030   55.95    6090   57.93
    6110   57.33    6230   61.15    6320   72.16    6340   73.85  6473.8   79.04
#Mann= 3 ,-1,0
  3708.2     .15       0  4966.1    .045       0  5033.9     .15       0
Bank Sta=4966.1,5033.9
XS Rating Curve= 0 ,0
Exp/Cntr=0.3,0.1

Type RM Length L Ch R = 1 ,34347   ,477,477,477
BEGIN DESCRIPTION:
Indian Field Swamp 69.0
END DESCRIPTION:
XS GIS Cut Line= 3
      2157562.66       475383.73       2156232.8       474789.97
      2155083.68       474290.41
#Sta/Elev= 30
  3537.4   74.39  3747.4    71.5  3887.4   67.64  3987.4   63.41  4157.4   60.47
  4247.4   55.09  4367.4   53.58  4927.4   53.02  4947.4   53.93  4957.4   53.34
  4966.1    50.8  4967.6    47.8  5032.4    47.8  5033.9    50.8  5043.8   53.42
  5113.8   53.28  5133.8   54.49  5213.8   53.19  5393.8   53.97  5463.8   52.89
  5493.8   54.36  5523.8    52.8  5733.8   53.98  5763.8   52.91  5793.8   54.72
  5843.8   53.28  5903.8   55.16  6043.8   69.68  6193.8   72.99  6246.8   70.17
#Mann= 3 ,-1,0
  3537.4     .15       0  4966.1    .045       0  5033.9     .15       0
Bank Sta=4966.1,5033.9
XS Rating Curve= 0 ,0
Exp/Cntr=0.3,0.1

Type RM Length L Ch R = 1 ,33870   ,409,409,409
BEGIN DESCRIPTION:
Indian Field Swamp 68.0
END DESCRIPTION:
XS GIS Cut Line= 3
      2157857.73       473972.79       2156273.8       474328.54
      2155096.41       474137.96
#Sta/Elev= 30
  3376.2   75.67  3496.2   72.59  3626.2   67.23  3776.2   58.26  3876.2   55.71
  4426.2   54.66  4965.4    50.4  4966.9    47.4  5033.1    47.4  5034.6    50.4
  5039.6   52.94  5059.6   54.15  5129.6   53.11  5189.6   54.68  5239.6    53.1
  5319.6   54.37  5429.6   52.91  5559.6   52.86  5569.6   54.68  5629.6   52.82
  5649.6   54.82  5669.6   52.72  5739.6   53.42  5789.6    52.4  5819.6    54.9
  5839.6   58.64  5929.6   68.61  5989.6    78.2  6089.6   79.98  6192.3   78.37
#Mann= 3 ,-1,0
  3376.2     .15       0  4965.4    .045       0  5034.6     .15       0
Bank Sta=4965.4,5034.6
XS Rating Curve= 0 ,0
Exp/Cntr=0.3,0.1

Type RM Length L Ch R = 1 ,33461   ,500,500,500
BEGIN DESCRIPTION:
Indian Field Swamp 67.0
END DESCRIPTION:
XS GIS Cut Line= 3
      2157806.93       473545.03      2156228.11       473922.83
      2155100.61       473921.96
#Sta/Elev= 30
  3376.6   76.93  3516.6   72.26  3566.6   69.31  3726.6   67.78  3876.6   64.59
  4006.6   58.27  4106.6   55.27  4206.6   53.97  4956.6   53.02  4965.4   50.55
  4966.9   47.55  5033.1   47.55  5034.6   50.55    5120    53.1    5390   53.01
    5430    55.5    5450   53.53    5480   52.83    5540   52.77    5550   54.17
    5580   54.53    5620   52.67    5720   52.63    5780   54.61    5820    58.1
    5890   73.93    5910   77.07    5940   79.32    6000   81.83  6127.5   82.12
#Mann= 3 ,-1,0
  3376.6     .15       0  4965.4    .045       0  5034.6     .15       0
Bank Sta=4965.4,5034.6
XS Rating Curve= 0 ,0
Exp/Cntr=0.3,0.1

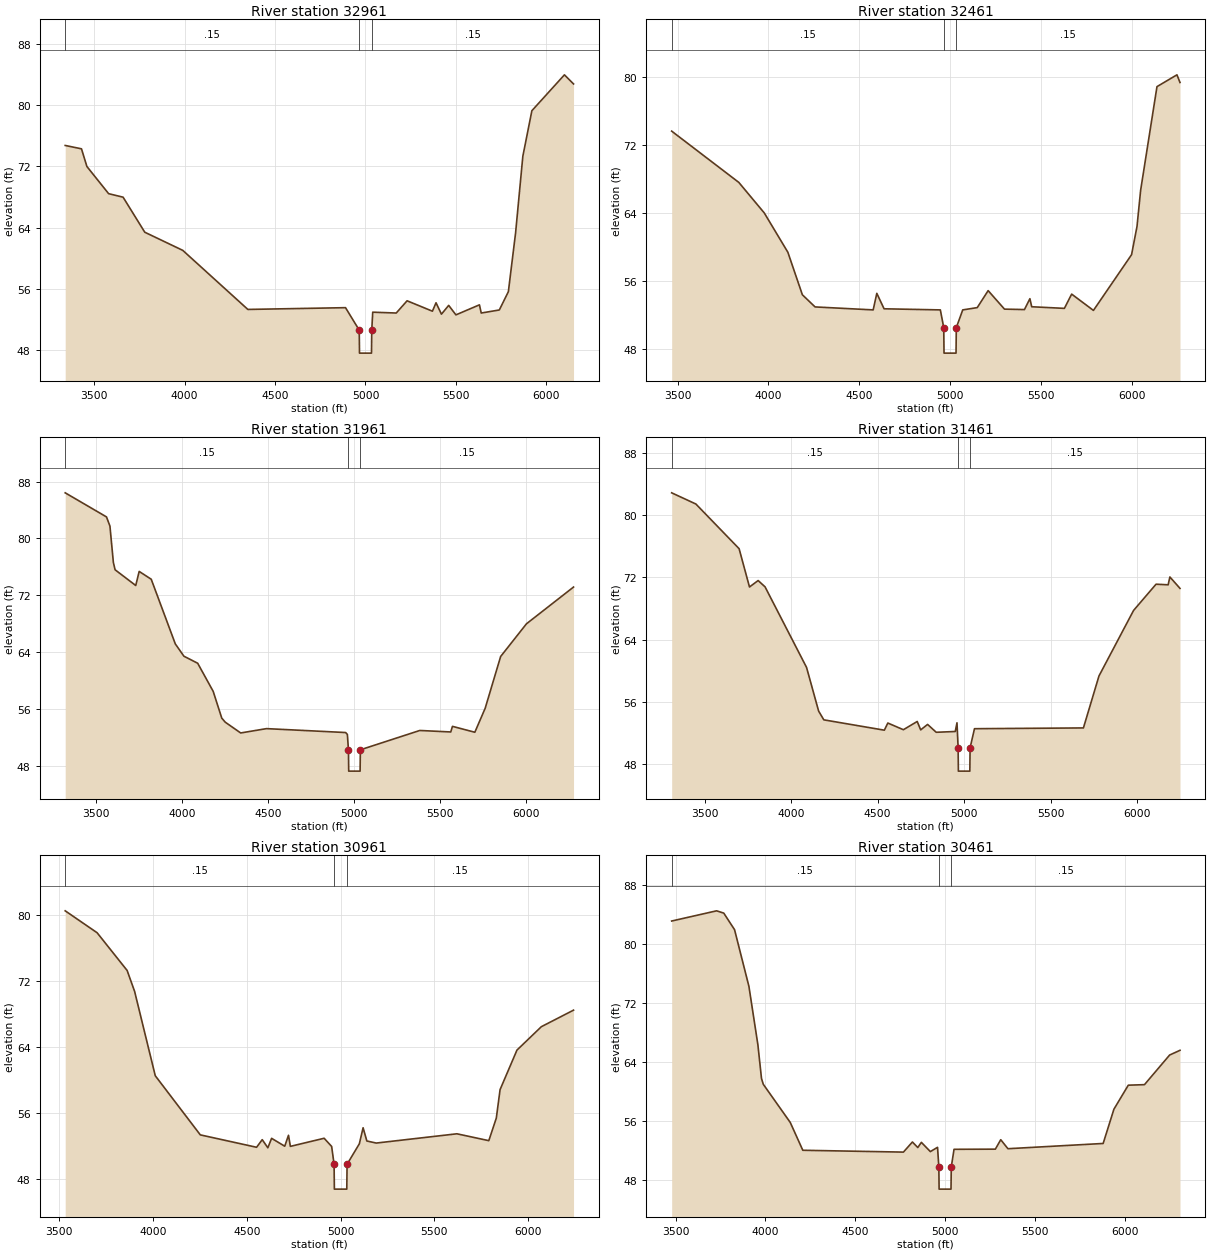
Type RM Length L Ch R = 1 ,32961   ,500,500,500
BEGIN DESCRIPTION:
Indian Field Swamp 66.0
END DESCRIPTION:
XS GIS Cut Line= 3
      2157751.86       473028.34      2156141.07       473431.21
      2155049.79       473794.92
#Sta/Elev= 30
  3339.6   74.73  3429.6   74.29  3459.6   71.98  3579.6   68.43  3659.6   67.97
  3779.6   63.39  3989.6   61.02  4349.6    53.3  4889.6   53.53  4965.4   50.59
  4966.9   47.59  5033.1   47.59  5034.6   50.59    5040   52.94    5170   52.83
    5230   54.43    5370   53.07    5390   54.17    5420   52.68    5460   53.83
    5500   52.59    5630    53.9    5640   52.83    5740   53.23    5790   55.62
    5830   63.32    5870   73.32    5920   79.27    6100   83.96  6150.3   82.77
#Mann= 3 ,-1,0
  3339.6     .15       0  4965.4    .045       0  5034.6     .15       0
Bank Sta=4965.4,5034.6
XS Rating Curve= 0 ,0
Exp/Cntr=0.3,0.1

Type RM Length L Ch R = 1 ,32461   ,500,500,500
BEGIN DESCRIPTION:
Indian Field Swamp 65.0
END DESCRIPTION:
XS GIS Cut Line= 3
       2157396.1       472376.12      2155978.79       472961.14
      2154812.67       473456.08
#Sta/Elev= 30
  3466.7   73.65  3836.7   67.61  3976.7   64.02  4106.7   59.39  4186.7   54.38
  4256.7   52.95  4576.7    52.6  4596.7   54.55  4636.7   52.73  4946.7    52.6
  4965.4   50.51  4966.9   47.51  5033.1   47.51  5034.6   50.51    5070    52.6
    5150   52.87    5210   54.87    5300   52.69    5410   52.64    5440   53.92
    5450   52.97    5630   52.78    5670   54.46    5790   52.54    6000    59.1
    6030   62.43    6050   66.69    6140   78.89    6250   80.28  6266.8   79.38
#Mann= 3 ,-1,0
  3466.7     .15       0  4965.4    .045       0  5034.6     .15       0
Bank Sta=4965.4,5034.6
XS Rating Curve= 0 ,0
Exp/Cntr=0.3,0.1

Type RM Length L Ch R = 1 ,31961   ,500,500,500
BEGIN DESCRIPTION:
Indian Field Swamp 64.0
END DESCRIPTION:
XS GIS Cut Line= 3
       2157319.9       471855.18      2155770.38       472506.65
      2154630.58        473074.9
#Sta/Elev= 30
  3319.1   86.41  3559.1   83.02  3579.1   81.73  3599.1    76.6  3609.1   75.58
  3729.1   73.37  3749.1   75.35  3819.1   74.25  3959.1   65.15  4009.1   63.42
  4089.1   62.43  4179.1   58.48  4229.1   54.71  4249.1   54.14  4339.1   52.62
  4489.1   53.23  4949.1   52.68  4959.1   52.41  4965.4   50.25  4966.9   47.25
  5033.1   47.25  5034.6   50.25    5380   52.97    5560   52.76    5570   53.55
    5700   52.72    5760   56.09    5850   63.38    6000   67.98  6273.6   73.15
#Mann= 3 ,-1,0
  3319.1     .15       0  4965.4    .045       0  5034.6     .15       0
Bank Sta=4965.4,5034.6
XS Rating Curve= 0 ,0
Exp/Cntr=0.3,0.1

Type RM Length L Ch R = 1 ,31461   ,500,500,500
BEGIN DESCRIPTION:
Indian Field Swamp 63.0
END DESCRIPTION:
XS GIS Cut Line= 3
      2157171.62       471533.32      2155561.97       472052.15
      2154588.19       472833.51
#Sta/Elev= 30
  3308.8   82.88  3448.8   81.44  3698.8   75.69  3758.8   70.76  3808.8   71.59
  3848.8   70.78  4088.8   60.41  4158.8   54.78  4188.8   53.66  4538.8   52.33
  4558.8   53.25  4648.8   52.39  4728.8   53.45  4748.8   52.37  4788.8   53.07
  4838.8   52.06  4948.8   52.16  4958.8   53.28  4965.4   50.06  4966.9   47.06
  5033.1   47.06  5034.6   50.06    5060   52.52    5690   52.62    5780   59.31
    5980   67.74    6110   71.12    6180   71.04    6190   72.05  6248.5   70.58
#Mann= 3 ,-1,0
  3308.8     .15       0  4965.4    .045       0  5034.6     .15       0
Bank Sta=4965.4,5034.6
XS Rating Curve= 0 ,0
Exp/Cntr=0.3,0.1

Type RM Length L Ch R = 1 ,30961   ,500,500,500
BEGIN DESCRIPTION:
Indian Field Swamp 62.0
END DESCRIPTION:
XS GIS Cut Line= 3
      2156578.73       470868.38      2155318.35       471620.24
      2154545.83       472592.11
#Sta/Elev= 30
  3532.4   80.48  3702.4   77.83  3862.4   73.27  3902.4   70.73  4012.4   60.54
  4252.4   53.39  4552.4   51.89  4582.4   52.81  4612.4   51.83  4632.4   52.97
  4702.4   52.02  4722.4   53.34  4732.4      52  4912.4   52.98  4952.4   51.99
  4965.4   49.83  4966.9   46.83  5033.1   46.83  5034.6   49.83    5100   52.31
    5120   54.25    5140   52.65    5190    52.4    5620   53.52    5790   52.69
    5830   55.42    5850   58.86    5940   63.64    6070   66.47  6241.5   68.47
#Mann= 3 ,-1,0
  3532.4     .15       0  4965.4    .045       0  5034.6     .15       0
Bank Sta=4965.4,5034.6
XS Rating Curve= 0 ,0
Exp/Cntr=0.3,0.1

Type RM Length L Ch R = 1 ,30461   ,500,500,500
BEGIN DESCRIPTION:
Indian Field Swamp 61.0
END DESCRIPTION:
XS GIS Cut Line= 3
      2156299.23       470461.79      2154992.21       471241.25
      2154467.73       472439.28
#Sta/Elev= 30
  3478.2   83.09  3728.2   84.47  3768.2   84.16  3828.2   81.92  3908.2   74.25
  3958.2   66.33  3978.2   61.78  3988.2   60.99  4138.2   55.83  4208.2   52.06
  4768.2   51.81  4818.2   53.18  4848.2   52.43  4868.2   53.13  4918.2   51.88
  4958.2   52.46  4965.4    49.8  4966.9    46.8  5033.1    46.8  5034.6    49.8
    5050   52.19    5280   52.21    5310   53.49    5350   52.27    5880   52.98
    5940   57.62    6020   60.87    6110   60.94    6250   64.95  6307.8   65.59
#Mann= 3 ,-1,0
  3478.2     .15       0  4965.4    .045       0  5034.6     .15       0
Bank Sta=4965.4,5034.6
XS Rating Curve= 0 ,0
Exp/Cntr=0.3,0.1

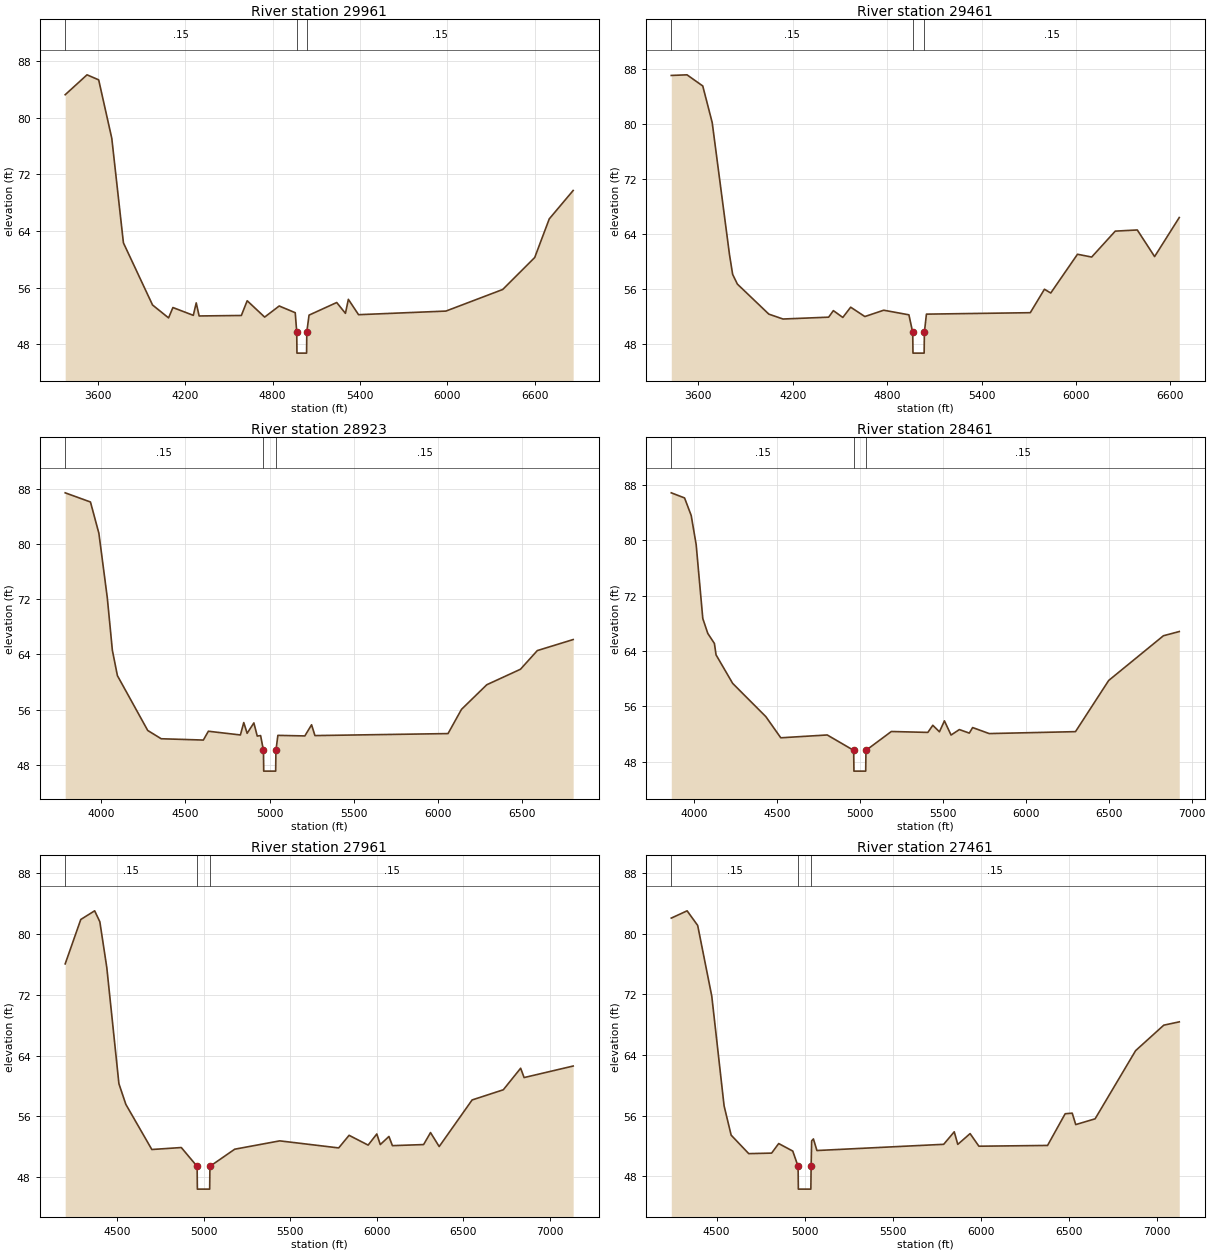
Type RM Length L Ch R = 1 ,29961   ,500,500,500
BEGIN DESCRIPTION:
Indian Field Swamp 60.0
END DESCRIPTION:
XS GIS Cut Line= 3
      2156072.21       470128.79      2154637.23       470891.11
      2153703.17        472504.3
#Sta/Elev= 30
  3375.1   83.27  3525.1   86.08  3605.1   85.37  3695.1   77.12  3775.1   62.34
  3975.1   53.56  4085.1   51.74  4115.1    53.2  4255.1    52.1  4275.1   53.86
  4295.1   52.01  4585.1   52.08  4625.1   54.16  4745.1   51.85  4845.1   53.42
  4955.1   52.47  4965.4   49.76  4966.9   46.76  5033.1   46.76  5034.6   49.76
    5050   52.13    5240   53.91    5300   52.38    5320   54.36    5390   52.19
    5990    52.7    6380   55.75    6600   60.27    6700   65.73  6864.1   69.74
#Mann= 3 ,-1,0
  3375.1     .15       0  4965.4    .045       0  5034.6     .15       0
Bank Sta=4965.4,5034.6
XS Rating Curve= 0 ,0
Exp/Cntr=0.3,0.1

Type RM Length L Ch R = 1 ,29461   ,538,538,538
BEGIN DESCRIPTION:
Indian Field Swamp 59.0
END DESCRIPTION:
XS GIS Cut Line= 3
      2155853.86       469864.95      2154411.07       470487.33
       2152819.6       470947.63
#Sta/Elev= 30
  3428.7   87.07  3528.7   87.16  3628.7   85.54  3688.7   80.22  3798.7      61
  3818.7   58.14  3848.7   56.73  4048.7   52.36  4138.7   51.65  4428.7   51.92
  4458.7   52.87  4518.7   51.88  4568.7   53.37  4658.7   52.01  4778.7   52.93
  4938.7   52.26    4963   49.69  4964.5   46.69  5035.5   46.69    5037   49.69
    5050   52.36    5710   52.57    5800   55.98    5840   55.43    6010   61.07
    6100   60.66    6250   64.43    6390    64.6    6500   60.73  6656.7   66.41
#Mann= 3 ,-1,0
  3428.7     .15       0    4963    .045       0    5037     .15       0
Bank Sta=4963,5037
XS Rating Curve= 0 ,0
Exp/Cntr=0.3,0.1

Type RM Length L Ch R = 1 ,28923   ,462,462,462
BEGIN DESCRIPTION:
Indian Field Swamp 58.0
END DESCRIPTION:
XS GIS Cut Line= 3
      2155726.52       469614.74      2154564.99       469995.96
      2152842.37       470492.72
#Sta/Elev= 30
  3786.1   87.46  3936.1   86.13  3986.1   81.59  4036.1   72.22  4066.1   64.61
  4096.1   60.92  4276.1   52.96  4356.1   51.76  4606.1   51.57  4636.1   52.85
  4826.1   52.31  4846.1   54.11  4866.1   52.55  4906.1   54.06  4926.1   52.15
  4946.1   52.22    4963   50.06  4964.5   47.06  5035.5   47.06    5037   50.06
  5048.6   52.25  5208.6   52.17  5248.6   53.79  5268.6   52.22  6058.6   52.51
  6138.6   56.03  6288.6    59.6  6488.6   61.85  6588.6   64.56  6801.4   66.16
#Mann= 3 ,-1,0
  3786.1     .15       0    4963    .045       0    5037     .15       0
Bank Sta=4963,5037
XS Rating Curve= 0 ,0
Exp/Cntr=0.3,0.1

Type RM Length L Ch R = 1 ,28461   ,500,500,500
BEGIN DESCRIPTION:
Indian Field Swamp 57.0
END DESCRIPTION:
XS GIS Cut Line= 3
      2155658.26       469218.98      2154566.25       469533.51
      2152710.46       470046.91
#Sta/Elev= 30
  3863.6   86.88  3943.6   86.14  3983.6   83.61  4013.6   79.39  4053.6    68.7
  4083.6   66.55  4123.6   65.09  4133.6   63.44  4233.6   59.32  4433.6   54.51
  4523.6   51.45  4803.6   51.86    4963   49.63  4964.5   46.63  5035.5   46.63
    5037   49.63    5190   52.36    5410   52.23    5440   53.26    5480   52.32
    5510    53.9    5550   51.85    5600   52.64    5660   52.13    5680   52.93
    5780   52.06    6300   52.34    6500   59.74    6830   66.21  6925.5   66.82
#Mann= 3 ,-1,0
  3863.6     .15       0    4963    .045       0    5037     .15       0
Bank Sta=4963,5037
XS Rating Curve= 0 ,0
Exp/Cntr=0.3,0.1

Type RM Length L Ch R = 1 ,27961   ,500,500,500
BEGIN DESCRIPTION:
Indian Field Swamp 56.0
END DESCRIPTION:
XS GIS Cut Line= 3
      2155326.13       468836.87      2154552.49       469033.73
       2152487.6       469569.25
#Sta/Elev= 30
  4201.7   76.09  4291.7   81.94  4371.7   83.08  4401.7   81.64  4441.7   75.63
  4511.7   60.31  4551.7   57.58  4701.7   51.63  4871.7   51.89    4963   49.41
  4964.5   46.41  5035.5   46.41    5037   49.41    5180   51.67    5440   52.77
    5780   51.84    5840    53.5    5950   52.21    6000   53.68    6020   52.28
    6070   53.35    6090   52.14    6270   52.28    6310   53.86    6360   52.02
    6550   58.16    6730    59.5    6830   62.34    6850   61.11  7133.2   62.63
#Mann= 3 ,-1,0
  4201.7     .15       0    4963    .045       0    5037     .15       0
Bank Sta=4963,5037
XS Rating Curve= 0 ,0
Exp/Cntr=0.3,0.1

Type RM Length L Ch R = 1 ,27461   ,500,500,500
BEGIN DESCRIPTION:
Indian Field Swamp 55.0
END DESCRIPTION:
XS GIS Cut Line= 3
      2155153.33        468404.7        2154411.       468554.54
      2152319.22       468946.05
#Sta/Elev= 30
  4242.7   82.04  4332.7      83  4392.7   81.07  4472.7   71.75  4542.7   57.28
  4582.7   53.42  4682.7   50.98  4812.7   51.05  4852.7   52.31  4932.7   51.32
    4963    49.3  4964.5    46.3  5035.5    46.3    5037    49.3    5040   52.66
    5050   52.92    5070   51.39    5790   52.21    5850   53.86    5870    52.2
    5940   53.62    5990   51.96    6380   52.06    6480   56.24    6520   56.32
    6540   54.81    6650   55.57    6880   64.56    7040   67.92  7128.1   68.36
#Mann= 3 ,-1,0
  4242.7     .15       0    4963    .045       0    5037     .15       0
Bank Sta=4963,5037
XS Rating Curve= 0 ,0
Exp/Cntr=0.3,0.1

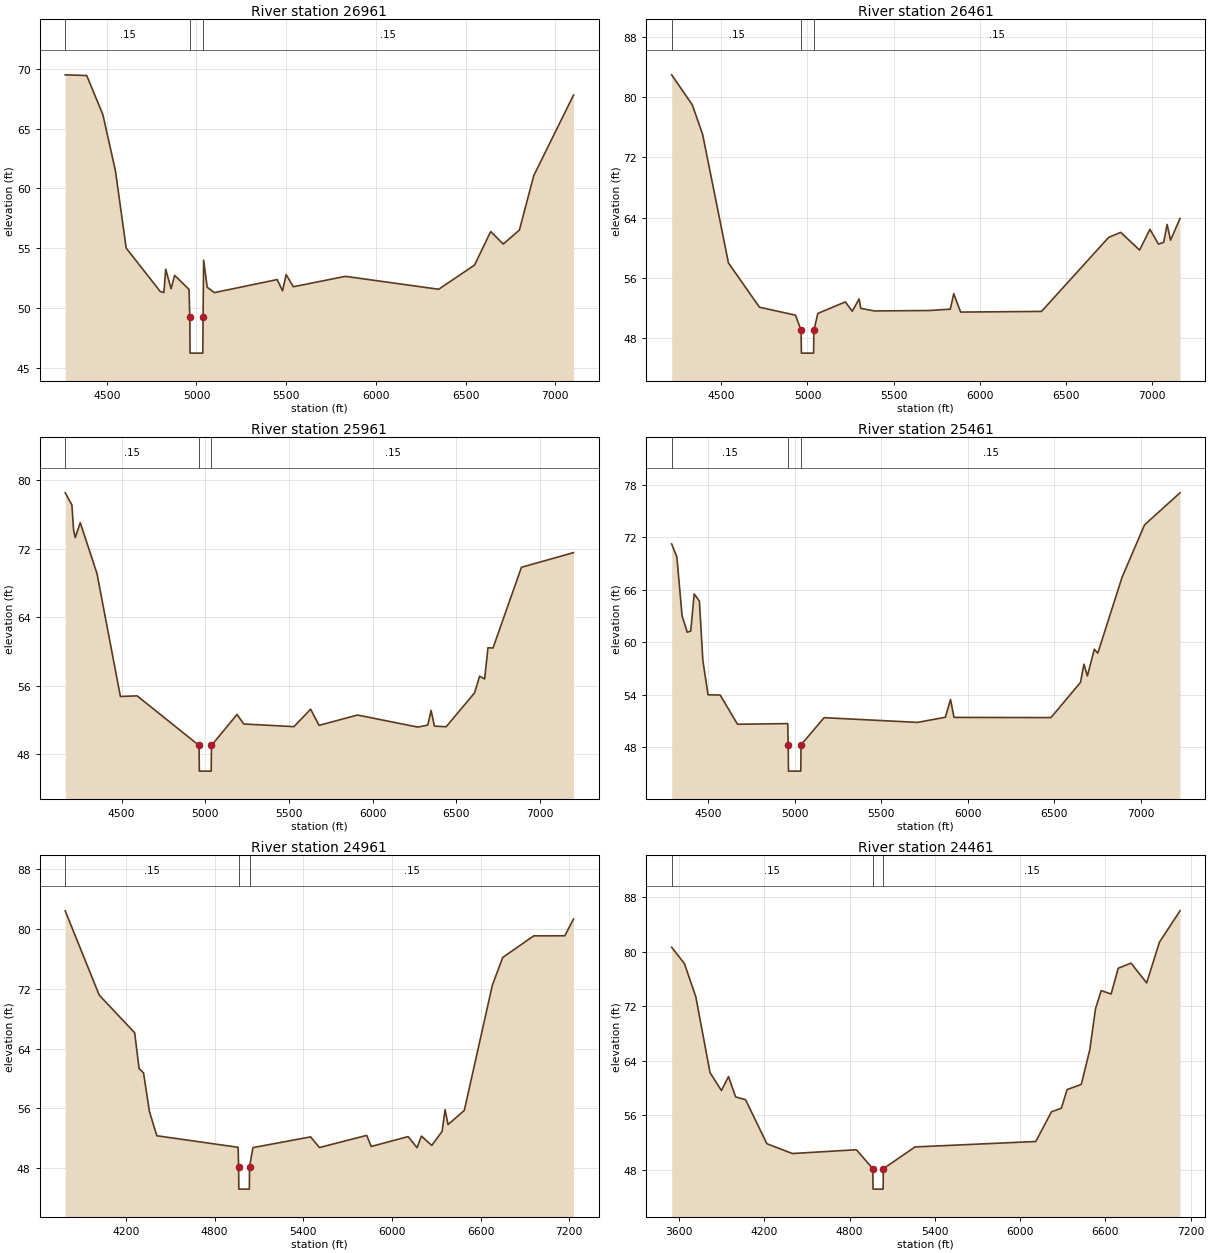
Type RM Length L Ch R = 1 ,26961   ,500,500,500
BEGIN DESCRIPTION:
Indian Field Swamp 54.0
END DESCRIPTION:
XS GIS Cut Line= 3
      2155118.16       468186.44      2154398.15        468057.9
      2152296.45       468059.38
#Sta/Elev= 30
  4268.6   69.49  4388.6   69.43  4478.6   66.16  4548.6   61.46  4608.6      55
  4798.6   51.37  4818.6   51.29  4828.6   53.24  4858.6   51.61  4878.6   52.72
  4958.6   51.55    4963   49.22  4964.5   46.22  5035.5   46.22    5037   49.22
    5040   53.99    5060   51.73    5100   51.28    5450   52.37    5480   51.43
    5500   52.79    5540   51.77    5830   52.64    6350   51.56    6550   53.58
    6640   56.39    6710   55.34    6800   56.51    6880   61.06  7101.7    67.8
#Mann= 3 ,-1,0
  4268.6     .15       0    4963    .045       0    5037     .15       0
Bank Sta=4963,5037
XS Rating Curve= 0 ,0
Exp/Cntr=0.3,0.1

Type RM Length L Ch R = 1 ,26461   ,500,500,500
BEGIN DESCRIPTION:
Indian Field Swamp 53.0
END DESCRIPTION:
XS GIS Cut Line= 3
      2155208.16        467598.8      2154418.86       467601.35
      2152254.06        467598.8
#Sta/Elev= 30
  4210.7   82.95  4330.7   78.96  4390.7   75.05  4540.7   58.01  4720.7   52.15
  4930.7   51.09    4963   49.06  4964.5   46.06  5035.5   46.06    5037   49.06
    5060   51.32    5220   52.85    5260   51.61    5300   53.24    5310   51.99
    5390   51.65    5710   51.71    5830   51.89    5850   53.94    5890    51.5
    6360   51.59    6750    61.4    6820   62.07    6930   59.72    6990   62.47
    7040   60.51    7070   60.74    7090   63.12    7110   61.03  7164.8   63.91
#Mann= 3 ,-1,0
  4210.7     .15       0    4963    .045       0    5037     .15       0
Bank Sta=4963,5037
XS Rating Curve= 0 ,0
Exp/Cntr=0.3,0.1

Type RM Length L Ch R = 1 ,25961   ,500,500,500
BEGIN DESCRIPTION:
Indian Field Swamp 52.0
END DESCRIPTION:
XS GIS Cut Line= 3
      2155250.46       467117.04      2154413.18       467112.48
      2152211.68       467117.04
#Sta/Elev= 30
  4162.7   78.54  4202.7   77.13  4212.7   74.22  4222.7   73.31  4252.7   75.05
  4352.7    69.1  4492.7   54.73  4592.7    54.8    4963      49  4964.5      46
  5035.5      46    5037      49    5190   52.63    5230   51.51    5530    51.2
    5630   53.24    5680   51.35    5910   52.56    6270   51.15    6330   51.38
    6350   53.09    6370   51.26    6440   51.19    6610   55.15    6640    57.1
    6670   56.78    6690   60.43    6720   60.39    6890   69.83  7201.5   71.55
#Mann= 3 ,-1,0
  4162.7     .15       0    4963    .045       0    5037     .15       0
Bank Sta=4963,5037
XS Rating Curve= 0 ,0
Exp/Cntr=0.3,0.1

Type RM Length L Ch R = 1 ,25461   ,500,500,500
BEGIN DESCRIPTION:
Indian Field Swamp 51.0
END DESCRIPTION:
XS GIS Cut Line= 3
      2155124.97         466625.      2154415.17       466623.58
      2152190.57        466624.7
#Sta/Elev= 30
  4290.2   71.25  4320.2   69.76  4350.2   63.04  4380.2   61.15  4400.2    61.3
  4420.2   65.53  4450.2   64.72  4470.2   57.93  4500.2      54  4570.2   53.98
  4670.2   50.64  4960.2   50.71    4963   48.28  4964.5   45.28  5035.5   45.28
    5037   48.28    5170   51.39    5710   50.85    5870   51.44    5900   53.47
    5920   51.42    6480    51.4    6650   55.42    6670    57.5    6690   56.16
    6730   59.21    6750   58.76    6890   67.43    7020   73.43  7224.6   77.09
#Mann= 3 ,-1,0
  4290.2     .15       0    4963    .045       0    5037     .15       0
Bank Sta=4963,5037
XS Rating Curve= 0 ,0
Exp/Cntr=0.3,0.1

Type RM Length L Ch R = 1 ,24961   ,500,500,500
BEGIN DESCRIPTION:
Indian Field Swamp 50.0
END DESCRIPTION:
XS GIS Cut Line= 3
      2155647.51       466254.12      2154442.42       466141.91
      2152222.32       465941.78
#Sta/Elev= 30
  3789.7   82.37  4019.7   71.13  4259.7    66.1  4289.7   61.31  4319.7   60.75
  4359.7   55.58  4409.7   52.36  4959.7   50.82    4963   48.24  4964.5   45.24
  5035.5   45.24    5037   48.24    5060   50.78    5450   52.21    5510   50.79
    5830   52.41    5860   50.93    6110   52.25    6170   50.77    6200   52.31
    6270   51.07    6340   52.95    6360   55.84    6380   53.85    6490   55.74
    6680   72.46    6750   76.15    6960   79.03    7170   79.04  7229.1   81.28
#Mann= 3 ,-1,0
  3789.7     .15       0    4963    .045       0    5037     .15       0
Bank Sta=4963,5037
XS Rating Curve= 0 ,0
Exp/Cntr=0.3,0.1

Type RM Length L Ch R = 1 ,24461   ,500,500,500
BEGIN DESCRIPTION:
Indian Field Swamp 49.0
END DESCRIPTION:
XS GIS Cut Line= 3
      2155725.04       465925.01      2154295.15       465669.15
      2152206.39       465280.02
#Sta/Elev= 30
  3547.4   80.66  3637.4   78.25  3717.4   73.38  3817.4   62.24  3897.4   59.61
  3947.4   61.66  3997.4   58.68  4067.4   58.26  4217.4   51.79  4397.4   50.35
  4847.4   50.91    4963   48.12  4964.5   45.12  5035.5   45.12    5037   48.12
    5260   51.32    6110   52.12    6220   56.48    6290   57.01    6330   59.75
    6430   60.51    6490   65.61    6530   71.61    6570   74.29    6640    73.8
    6690   77.58    6780   78.34    6890   75.43    6980   81.41  7124.7   86.02
#Mann= 3 ,-1,0
  3547.4     .15       0    4963    .045       0    5037     .15       0
Bank Sta=4963,5037
XS Rating Curve= 0 ,0
Exp/Cntr=0.3,0.1

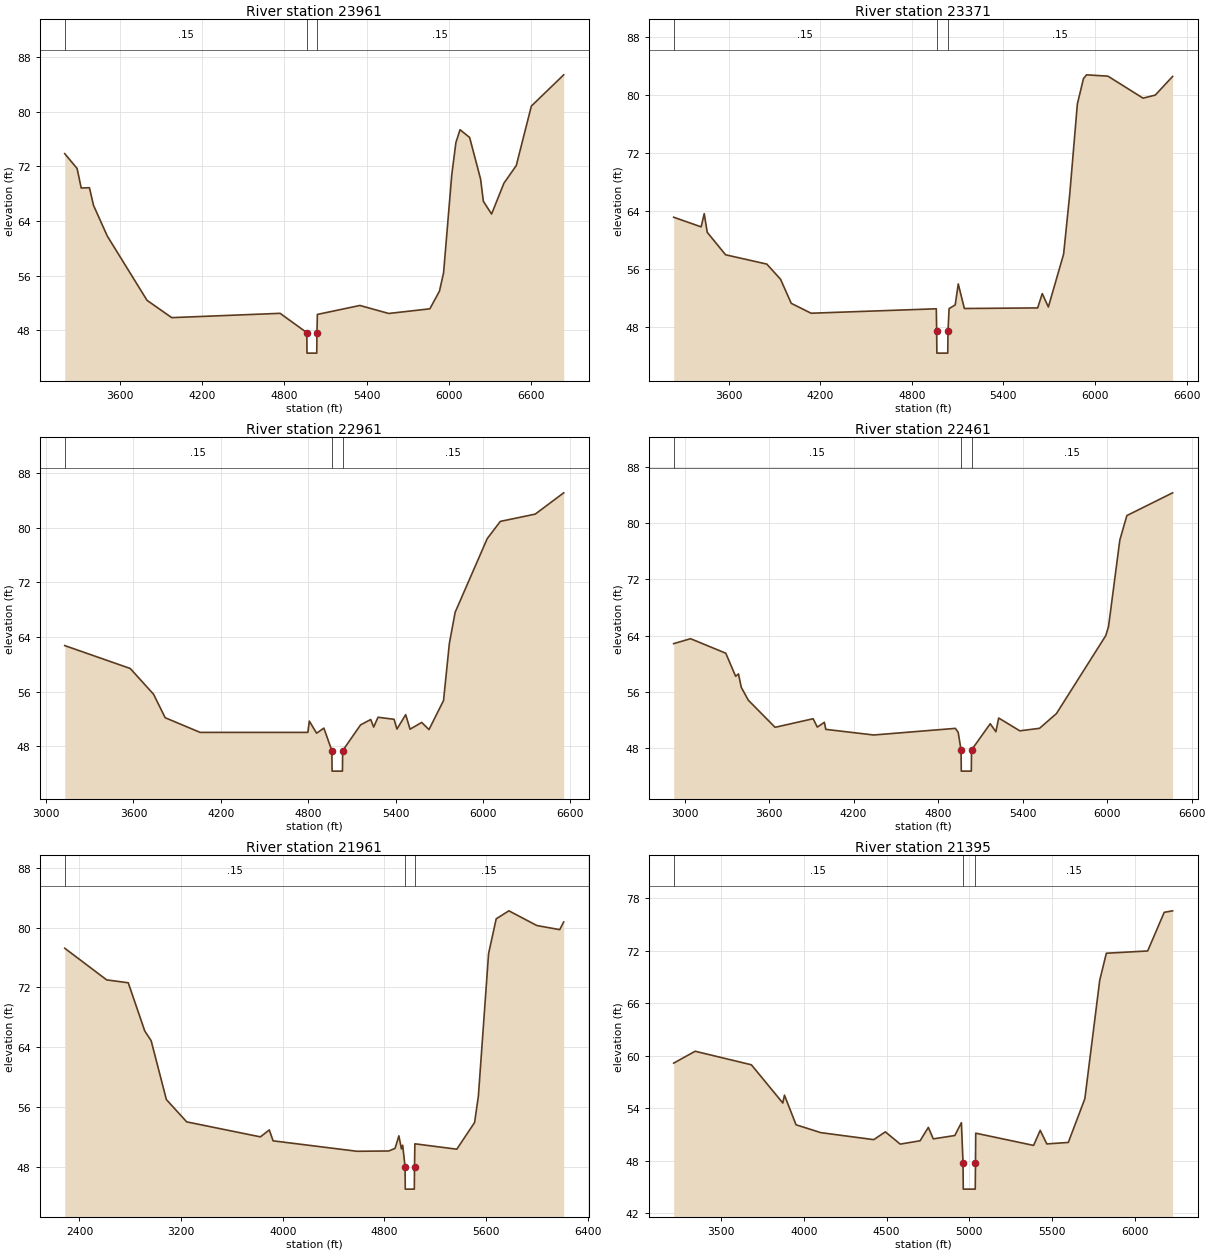
Type RM Length L Ch R = 1 ,23961   ,590,590,590
BEGIN DESCRIPTION:
Indian Field Swamp 48.0
END DESCRIPTION:
XS GIS Cut Line= 3
      2155906.93       465401.79      2154115.86       465206.39
      2152307.01       464893.56
#Sta/Elev= 30
  3198.3   73.86  3288.3    71.7  3318.3   68.84  3378.3   68.88  3408.3   66.29
  3508.3   61.82  3798.3   52.41  3978.3   49.88  4768.3   50.51    4963   47.69
  4964.5   44.69  5035.5   44.69    5037   47.69    5040   50.35    5350   51.66
    5560   50.49    5860   51.17    5930   53.75    5960   56.43    6020   70.81
    6050   75.49    6080   77.36    6150   76.23    6230   70.14    6250    66.9
    6310   65.03    6400   69.54    6490   72.12    6600   80.82  6835.7   85.39
#Mann= 3 ,-1,0
  3198.3     .15       0    4963    .045       0    5037     .15       0
Bank Sta=4963,5037
XS Rating Curve= 0 ,0
Exp/Cntr=0.3,0.1

Type RM Length L Ch R = 1 ,23371   ,410,410,410
BEGIN DESCRIPTION:
Indian Field Swamp 47.0
END DESCRIPTION:
XS GIS Cut Line= 3
      2155781.32       464781.17      2154024.44       464626.63
      2152527.75       464480.22
#Sta/Elev= 30
  3240.7   63.16  3420.7   61.83  3440.7   63.65  3460.7   61.08  3580.7   57.99
  3850.7   56.71  3940.7   54.62  4010.7   51.31  4140.7   49.95  4960.7   50.56
  4962.9   47.46  4964.4   44.46  5035.6   44.46  5037.1   47.46  5044.4   50.59
  5084.4   51.09  5104.4   53.98  5144.4    50.6  5624.4   50.68  5654.4   52.65
  5694.4   50.81  5794.4   58.09  5834.4   66.32  5884.4   78.75  5924.4   82.23
  5944.4   82.75  6084.4   82.57  6314.4   79.54  6394.4   79.96  6508.2   82.53
#Mann= 3 ,-1,0
  3240.7     .15       0  4962.9    .045       0  5037.1     .15       0
Bank Sta=4962.9,5037.1
XS Rating Curve= 0 ,0
Exp/Cntr=0.3,0.1

Type RM Length L Ch R = 1 ,22961   ,500,500,500
BEGIN DESCRIPTION:
Indian Field Swamp 46.0
END DESCRIPTION:
XS GIS Cut Line= 3
      2155834.21       464228.07      2153962.22       464229.75
      2152406.92       464233.13
#Sta/Elev= 30
    3128   62.74    3578   59.38    3738   55.61    3818   52.16    4058   50.01
    4798   50.01    4808   51.67    4858   49.89    4908   50.64  4962.9   47.33
  4964.4   44.33  5035.6   44.33  5037.1   47.33    5160   51.11    5230    51.9
    5250   50.79    5280   52.23    5390   51.93    5410    50.5    5470   52.61
    5500   50.48    5580   51.47    5630   50.42    5730   54.69    5770   63.06
    5810   67.64    6030   78.42    6120   80.95    6360   82.02  6555.3   85.14
#Mann= 3 ,-1,0
    3128     .15       0  4962.9    .045       0  5037.1     .15       0
Bank Sta=4962.9,5037.1
XS Rating Curve= 0 ,0
Exp/Cntr=0.3,0.1

Type RM Length L Ch R = 1 ,22461   ,500,500,500
BEGIN DESCRIPTION:
Indian Field Swamp 45.0
END DESCRIPTION:
XS GIS Cut Line= 3
      2155874.92       463593.63      2153804.46       463764.54
      2152367.22       464047.84
#Sta/Elev= 30
  2922.5   62.87  3042.5   63.57  3292.5   61.51  3362.5   58.23  3382.5   58.57
  3402.5   56.67  3452.5   54.84  3642.5   50.99  3912.5   52.21  3942.5   51.02
  3992.5    51.7  4002.5    50.7  4342.5    49.9  4922.5   50.84  4942.5   50.27
  4962.9   47.77  4964.4   44.77  5035.6   44.77  5037.1   47.77    5170    51.5
    5210   50.36    5230   52.31    5380   50.49    5520   50.85    5640   52.94
    5990      64    6010   65.31    6090   77.57    6140   81.05  6464.9   84.28
#Mann= 3 ,-1,0
  2922.5     .15       0  4962.9    .045       0  5037.1     .15       0
Bank Sta=4962.9,5037.1
XS Rating Curve= 0 ,0
Exp/Cntr=0.3,0.1

Type RM Length L Ch R = 1 ,21961   ,566,566,566
BEGIN DESCRIPTION:
Indian Field Swamp 44.0
END DESCRIPTION:
XS GIS Cut Line= 3
      2156074.19       462442.67      2153521.64       463370.36
      2152380.47       463776.52
#Sta/Elev= 30
  2284.1   77.26  2614.1   73.02  2784.1   72.63  2914.1   66.17  2964.1   64.88
  3084.1   56.99  3244.1      54  3824.1   51.99  3894.1   52.92  3924.1   51.46
  4584.1   50.06  4834.1    50.1  4884.1   50.45  4914.1   52.13  4934.1   50.38
  4944.1   50.87  4962.9   47.99  4964.4   44.99  5035.6   44.99  5037.1   47.99
    5040   51.06    5370   50.34    5510   53.91    5540   57.48    5620   76.52
    5680    81.2    5780   82.27    6000    80.3    6180   79.75  6211.3   80.78
#Mann= 3 ,-1,0
  2284.1     .15       0  4962.9    .045       0  5037.1     .15       0
Bank Sta=4962.9,5037.1
XS Rating Curve= 0 ,0
Exp/Cntr=0.3,0.1

Type RM Length L Ch R = 1 ,21395   ,434,434,434
BEGIN DESCRIPTION:
Indian Field Swamp 43.0
END DESCRIPTION:
XS GIS Cut Line= 3
      2154994.07       461958.15      2153424.99       462812.21
      2152377.11        463457.9
#Sta/Elev= 30
  3212.5   59.14  3342.5    60.5  3682.5   58.95  3872.5   54.58  3882.5   55.48
  3952.5   52.09  4102.5   51.19  4422.5   50.39  4492.5   51.28  4582.5   49.88
  4702.5   50.26  4752.5   51.79  4782.5   50.48  4912.5   50.86  4952.5   52.33
  4962.3   47.73  4963.8   44.73  5036.2   44.73  5037.7   47.73    5039   51.13
    5389   49.73    5429   51.45    5469    49.9    5599   50.07    5699   55.07
    5789   68.62    5829   71.71    6079   71.97    6179   76.39  6229.8   76.56
#Mann= 3 ,-1,0
  3212.5     .15       0  4962.3    .045       0  5037.7     .15       0
Bank Sta=4962.3,5037.7
XS Rating Curve= 0 ,0
Exp/Cntr=0.3,0.1