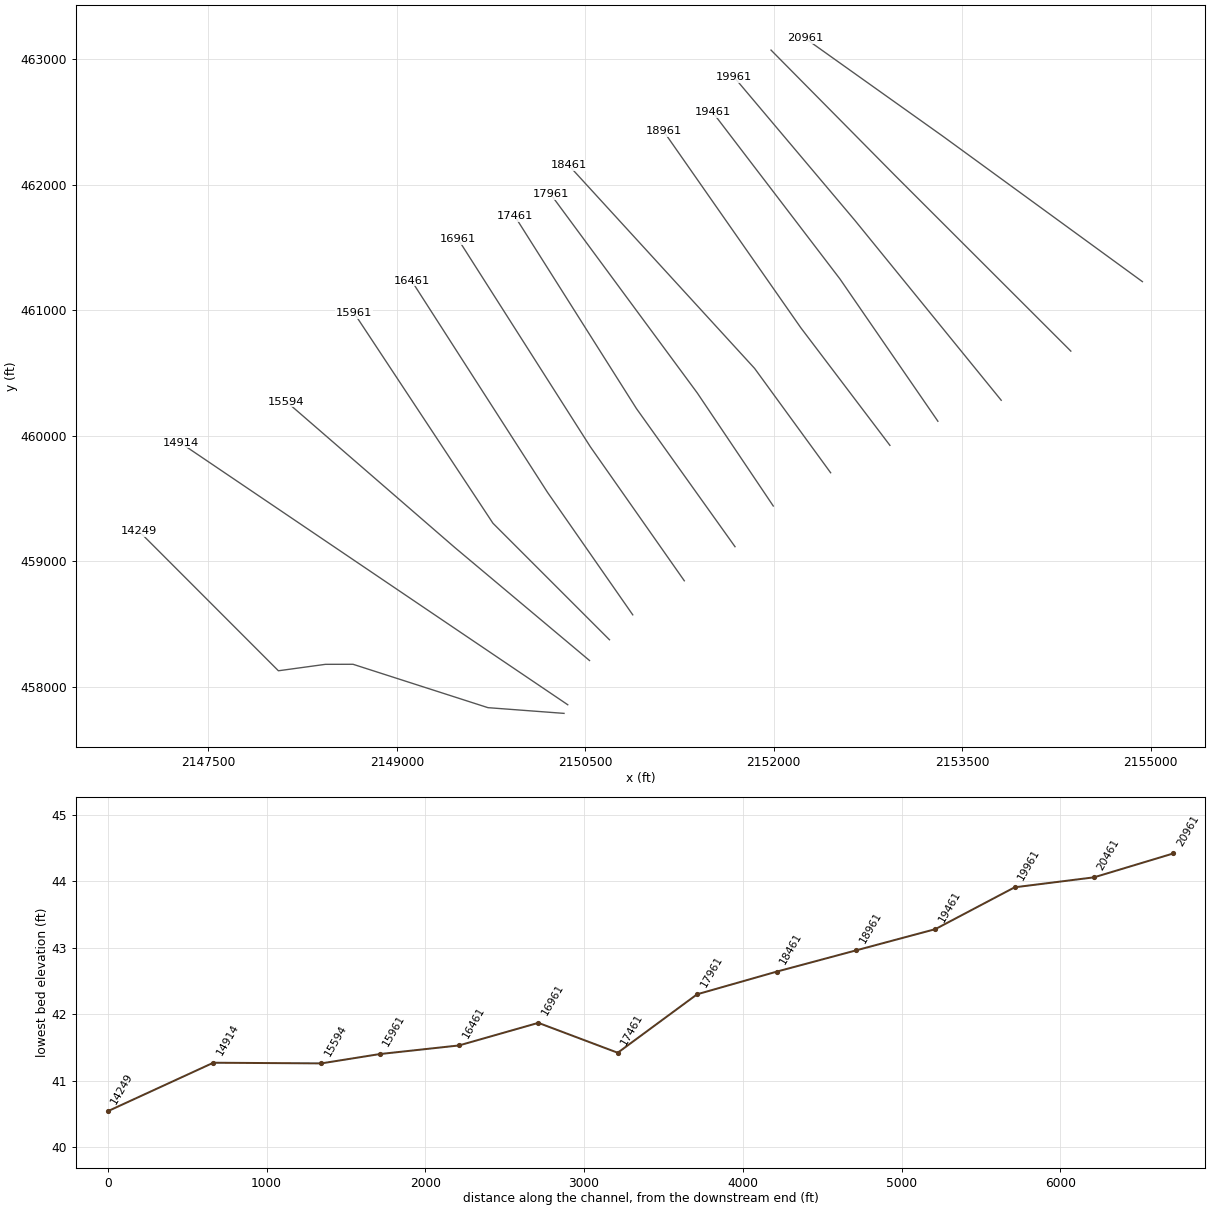
HEC-RAS study IndianFieldsSwamp.prj: S-18-19 over Indian Fields Swamp

--- IndianFieldsSwamp.g02 (geometry) --- (continued)

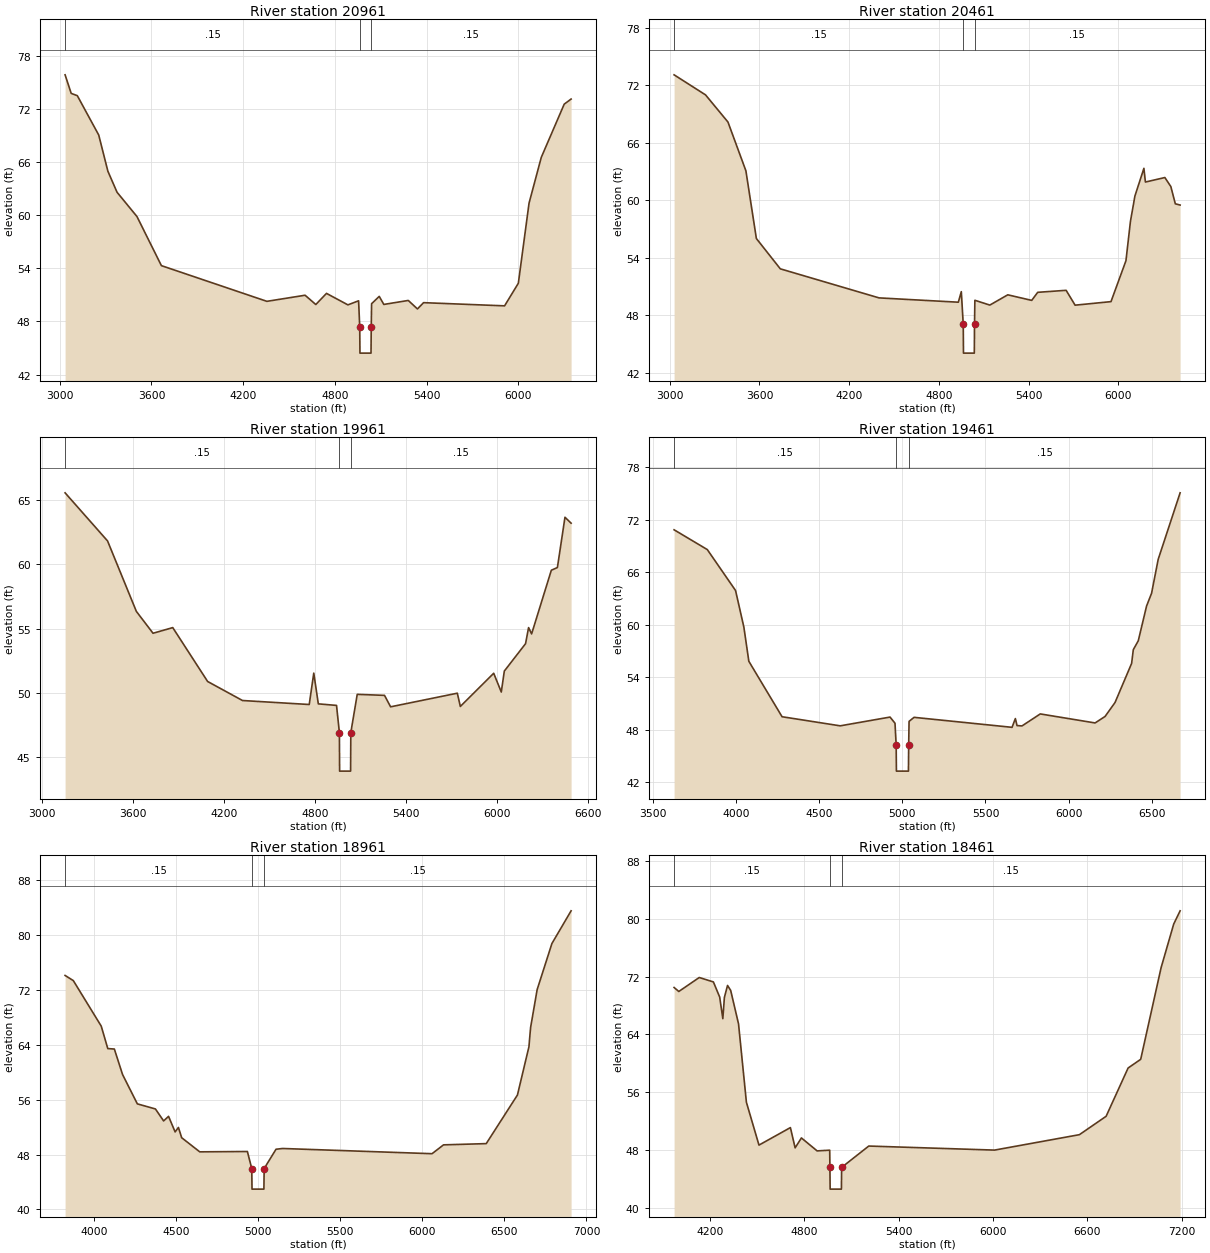
Type RM Length L Ch R = 1 ,20961   ,500,500,500
BEGIN DESCRIPTION:
Indian Field Swamp 42.0
END DESCRIPTION:
XS GIS Cut Line= 3
      2154934.79        461228.8      2153346.99       462386.44
      2152251.24        463166.6
#Sta/Elev= 30
    3035   75.91    3075   73.81    3115   73.55    3255    69.1    3315      65
    3375   62.62    3505   59.88    3665   54.32    4355   50.28    4605   50.97
    4675   49.92    4745   51.18    4885   49.88    4955   50.34  4962.3   47.42
  4963.8   44.42  5036.2   44.42  5037.7   47.42    5040   50.01    5090   50.84
    5120   49.93    5280   50.38    5340   49.42    5380   50.13    5910   49.77
    6000   52.33    6070   61.39    6150   66.57    6300   72.59  6345.1   73.17
#Mann= 3 ,-1,0
    3035     .15       0  4962.3    .045       0  5037.7     .15       0
Bank Sta=4962.3,5037.7
XS Rating Curve= 0 ,0
Exp/Cntr=0.3,0.1

Type RM Length L Ch R = 1 ,20461   ,500,500,500
BEGIN DESCRIPTION:
Indian Field Swamp 41.0
END DESCRIPTION:
XS GIS Cut Line= 3
      2154365.02       460675.61      2152971.31       462068.75
      2151978.77       463073.05
#Sta/Elev= 30
  3029.4   73.08  3239.4   70.99  3389.4   68.16  3509.4   63.07  3579.4   56.01
  3739.4   52.85  4399.4   49.82  4929.4   49.37  4949.4   50.47  4962.3   47.06
  4963.8   44.06  5036.2   44.06  5037.7   47.06    5040   49.57    5140   49.07
    5260   50.14    5420   49.56    5460    50.4    5650   50.61    5710   49.06
    5950   49.43    6050    53.7    6080    57.8    6110   60.45    6170   63.33
    6180    61.9    6310   62.37    6350   61.43    6380   59.63    6412    59.5
#Mann= 3 ,-1,0
  3029.4     .15       0  4962.3    .045       0  5037.7     .15       0
Bank Sta=4962.3,5037.7
XS Rating Curve= 0 ,0
Exp/Cntr=0.3,0.1

Type RM Length L Ch R = 1 ,19961   ,500,500,500
BEGIN DESCRIPTION:
Indian Field Swamp 40.0
END DESCRIPTION:
XS GIS Cut Line= 3
       2153810.9       460284.17      2152646.04       461717.01
      2151685.62       462856.69
#Sta/Elev= 30
  3153.4   65.55  3433.4   61.81  3623.4   56.33  3733.4   54.63  3863.4   55.07
  4093.4   50.88  4323.4    49.4  4763.4   49.09  4793.4   51.53  4823.4   49.14
  4943.4   49.02  4962.3   46.91  4963.8   43.91  5036.2   43.91  5037.7   46.91
    5080   49.88    5260    49.8    5300   48.91    5740   49.97    5760   48.94
    5980   51.52    6030   50.06    6050   51.69    6190   53.82    6210   55.07
    6230   54.58    6360   59.53    6400   59.74    6450   63.65  6490.4   63.19
#Mann= 3 ,-1,0
  3153.4     .15       0  4962.3    .045       0  5037.7     .15       0
Bank Sta=4962.3,5037.7
XS Rating Curve= 0 ,0
Exp/Cntr=0.3,0.1

Type RM Length L Ch R = 1 ,19461   ,500,500,500
BEGIN DESCRIPTION:
Indian Field Swamp 39.0
END DESCRIPTION:
XS GIS Cut Line= 3
      2153306.91       460117.03      2152527.78       461249.62
      2151513.56       462578.75
#Sta/Elev= 30
  3625.3   70.83  3825.3   68.57  3995.3    63.9  4045.3   59.73  4075.3   55.82
  4275.3   49.49  4625.3   48.45  4925.3   49.45  4955.3   48.75  4962.3   46.28
  4963.8   43.28  5036.2   43.28  5037.7   46.28    5040   48.96    5070   49.42
    5660   48.28    5680   49.28    5690   48.48    5720   48.44    5830   49.81
    6160   48.78    6220   49.52    6280   51.11    6380   55.58    6390   57.14
    6420   58.16    6470   62.13    6500   63.58    6540   67.46  6671.9   75.05
#Mann= 3 ,-1,0
  3625.3     .15       0  4962.3    .045       0  5037.7     .15       0
Bank Sta=4962.3,5037.7
XS Rating Curve= 0 ,0
Exp/Cntr=0.3,0.1

Type RM Length L Ch R = 1 ,18961   ,500,500,500
BEGIN DESCRIPTION:
Indian Field Swamp 38.0
END DESCRIPTION:
XS GIS Cut Line= 3
      2152925.02       459924.98      2152216.05       460861.24
      2151124.98       462425.03
#Sta/Elev= 30
  3825.6   74.14  3875.6   73.39  4045.6   66.75  4085.6   63.47  4125.6    63.4
  4175.6   59.68  4265.6    55.4  4375.6   54.66  4425.6   52.91  4455.6   53.58
  4495.6   51.31  4515.6   51.96  4535.6   50.46  4645.6    48.4  4935.6   48.45
  4962.3   45.96  4963.8   42.96  5036.2   42.96  5037.7   45.96    5110   48.78
    5150   48.89    6060   48.13    6130   49.42    6390    49.6    6580   56.69
    6650   63.73    6660   66.52    6700   72.07    6790    78.8  6906.8   83.57
#Mann= 3 ,-1,0
  3825.6     .15       0  4962.3    .045       0  5037.7     .15       0
Bank Sta=4962.3,5037.7
XS Rating Curve= 0 ,0
Exp/Cntr=0.3,0.1

Type RM Length L Ch R = 1 ,18461   ,500,500,500
BEGIN DESCRIPTION:
Indian Field Swamp 37.0
END DESCRIPTION:
XS GIS Cut Line= 3
      2152453.27       459706.72      2151847.76       460538.21
      2150369.29       462154.91
#Sta/Elev= 30
  3971.4   70.49  4001.4   69.94  4131.4   71.87  4221.4   71.26  4261.4   69.17
  4281.4   66.19  4291.4   69.12  4311.4   70.77  4331.4   70.09  4381.4   65.46
  4431.4   54.64  4511.4   48.72  4711.4   51.14  4741.4   48.34  4781.4   49.71
  4881.4   47.92  4961.4   48.02  4962.7   45.64  4964.2   42.64  5035.8   42.64
  5037.3   45.64    5210   48.59    6010   48.03    6550   50.16    6720    52.7
    6860   59.37    6940   60.57    7070   73.24    7150   79.25  7190.8   81.08
#Mann= 3 ,-1,0
  3971.4     .15       0  4962.7    .045       0  5037.3     .15       0
Bank Sta=4962.7,5037.3
XS Rating Curve= 0 ,0
Exp/Cntr=0.3,0.1

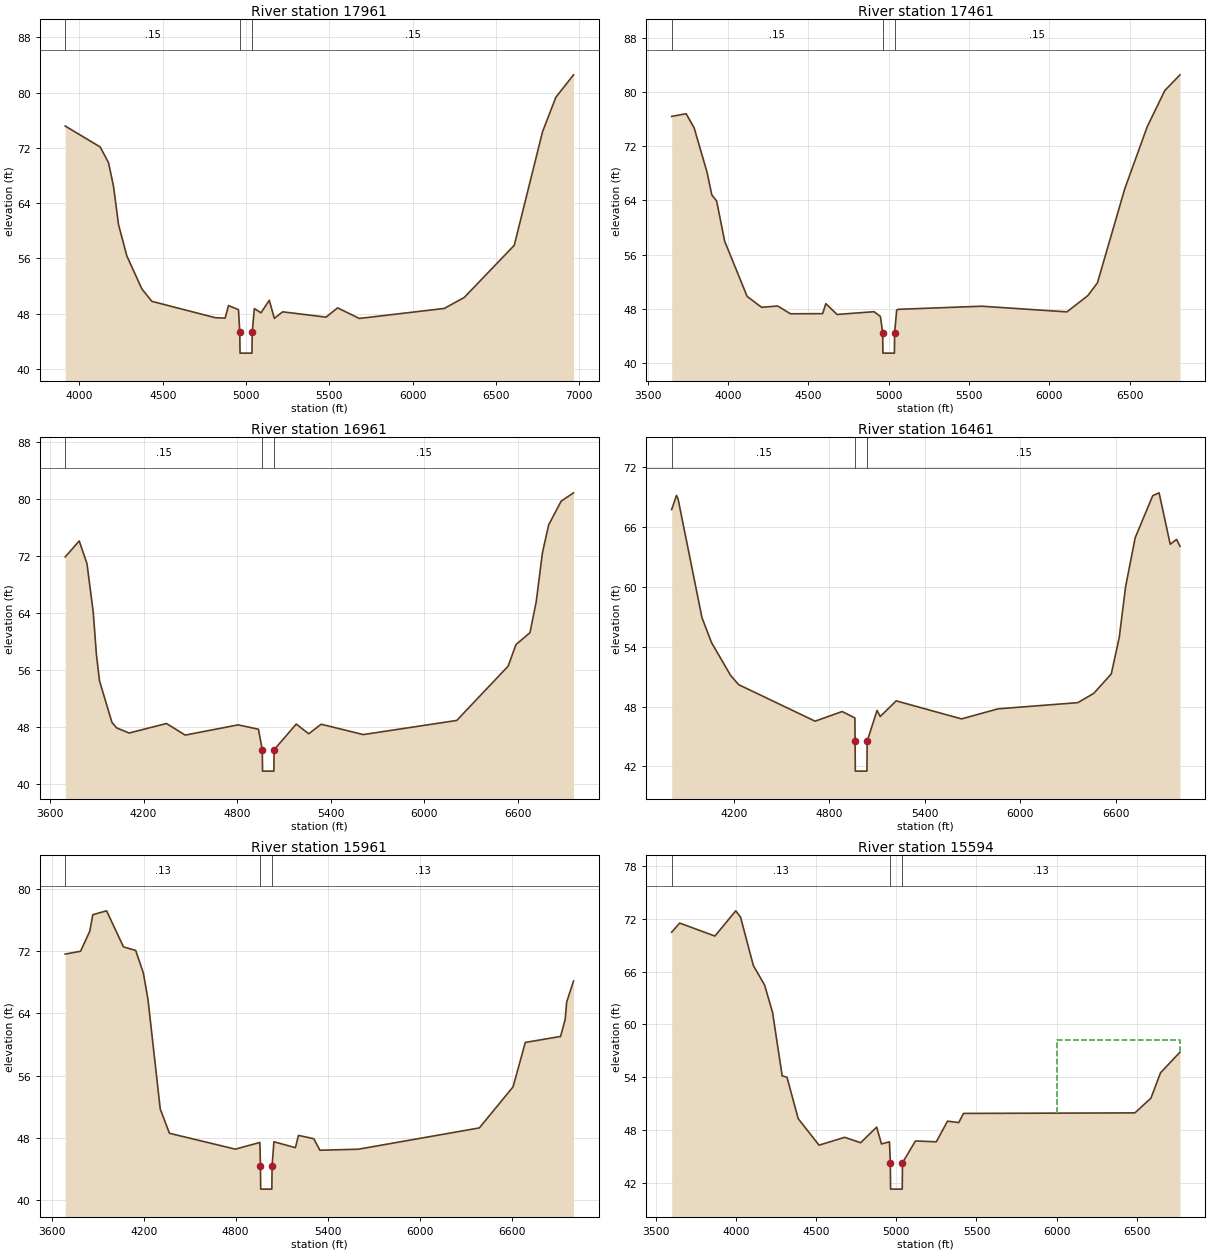
Type RM Length L Ch R = 1 ,17961   ,500,500,500
BEGIN DESCRIPTION:
Indian Field Swamp 36.0
END DESCRIPTION:
XS GIS Cut Line= 3
      2151996.65       459442.03      2151391.47        460342.7
        2150225.       461925.01
#Sta/Elev= 30
  3914.9   75.18  4124.9   72.15  4174.9   69.87  4204.9   66.45  4234.9   60.91
  4284.9   56.37  4374.9    51.6  4434.9    49.8  4814.9   47.43  4874.9   47.37
  4894.9   49.19  4954.9   48.59  4962.7    45.3  4964.2    42.3  5035.8    42.3
  5037.3    45.3    5050   48.75    5090   48.14    5140   49.95    5170   47.33
    5220   48.28    5480   47.51    5550   48.85    5680   47.32    6190   48.77
    6310   50.36    6610   57.91    6780   74.37    6860   79.35  6965.8   82.59
#Mann= 3 ,-1,0
  3914.9     .15       0  4962.7    .045       0  5037.3     .15       0
Bank Sta=4962.7,5037.3
XS Rating Curve= 0 ,0
Exp/Cntr=0.3,0.1

Type RM Length L Ch R = 1 ,17461   ,500,500,500
BEGIN DESCRIPTION:
Indian Field Swamp 35.0
END DESCRIPTION:
XS GIS Cut Line= 3
      2151692.23       459117.81      2150907.61       460217.86
      2149938.58       461751.58
#Sta/Elev= 30
  3648.8   76.44  3738.8   76.84  3788.8   74.74  3868.8   68.21  3898.8   64.82
  3928.8   63.93  3978.8   57.98  4118.8   49.81  4208.8    48.2  4308.8   48.39
  4388.8   47.24  4588.8   47.26  4608.8   48.74  4678.8   47.14  4908.8   47.55
  4948.8   46.84  4962.7   44.42  4964.2   41.42  5035.8   41.42  5037.3   44.42
    5050    47.8    5060    47.9    5580   48.36    6110   47.52    6240   49.92
    6300   51.81    6470   65.71    6610   74.91    6720   80.28  6814.2   82.59
#Mann= 3 ,-1,0
  3648.8     .15       0  4962.7    .045       0  5037.3     .15       0
Bank Sta=4962.7,5037.3
XS Rating Curve= 0 ,0
Exp/Cntr=0.3,0.1

Type RM Length L Ch R = 1 ,16961   ,500,500,500
BEGIN DESCRIPTION:
Indian Field Swamp 34.0
END DESCRIPTION:
XS GIS Cut Line= 3
      2151288.56       458846.49      2150540.91       459913.29
      2149488.61       461566.26
#Sta/Elev= 30
  3697.3   71.88  3787.3   74.12  3837.3   70.91  3877.3   64.11  3897.3   58.27
  3917.3   54.53  3997.3    48.7  4027.3   47.93  4107.3   47.21  4347.3   48.54
  4467.3   46.92  4807.3   48.35  4937.3   47.74  4962.1   44.87  4963.6   41.87
  5036.4   41.87  5037.9   44.87    5180   48.46    5260    47.1    5340   48.44
    5610   46.99    6210   48.97    6540   56.58    6590    59.6    6680   61.26
    6720   65.61    6760   72.47    6800   76.37    6880   79.69  6959.5   80.86
#Mann= 3 ,-1,0
  3697.3     .15       0  4962.1    .045       0  5037.9     .15       0
Bank Sta=4962.1,5037.9
XS Rating Curve= 0 ,0
Exp/Cntr=0.3,0.1

Type RM Length L Ch R = 1 ,16461   ,500,500,500
BEGIN DESCRIPTION:
Indian Field Swamp 33.0
END DESCRIPTION:
XS GIS Cut Line= 3
      2150878.26       458575.19      2150199.24       459551.36
        2149118.       461235.44
#Sta/Elev= 30
  3810.9   67.77  3840.9   69.19  3850.9   68.85  4000.9   56.94  4060.9   54.43
  4180.9   51.13  4230.9   50.21  4710.9   46.54  4880.9   47.51  4960.9   46.87
  4962.1   44.53  4963.6   41.53  5036.4   41.53  5037.9   44.53    5100   47.62
    5120   47.01    5220   48.58    5630   46.77    5860   47.78    6360    48.4
    6460   49.33    6570   51.28    6620   54.94    6660   60.04    6720   64.94
    6830   69.16    6870   69.45    6940   64.29    6980   64.78  7001.3   64.08
#Mann= 3 ,-1,0
  3810.9     .15       0  4962.1    .045       0  5037.9     .15       0
Bank Sta=4962.1,5037.9
XS Rating Curve= 0 ,0
Exp/Cntr=0.3,0.1

Type RM Length L Ch R = 1 ,15961   ,367,367,367
BEGIN DESCRIPTION:
Indian Field Swamp 32.0
END DESCRIPTION:
XS GIS Cut Line= 3
      2150692.96       458376.67       2149765.7       459304.44
      2148661.41       460977.33
#Sta/Elev= 30
  3688.3   71.62  3788.3   71.98  3848.3   74.54  3868.3   76.68  3958.3   77.18
  4068.3   72.55  4148.3   72.08  4198.3   69.17  4228.3   65.79  4308.3   51.71
  4368.3   48.58  4798.3   46.54  4958.3    47.4  4962.1    44.4  4963.6    41.4
  5036.4    41.4  5037.9    44.4    5050   47.49    5190   46.73    5210   48.31
    5310   47.88    5350    46.4    5600   46.53    6390   49.27    6610   54.55
    6690   60.26    6920   61.03    6950   63.22    6960   65.46  7004.5   68.15
#Mann= 3 ,-1,0
  3688.3     .13       0  4962.1    .045       0  5037.9     .13       0
Bank Sta=4962.1,5037.9
XS Rating Curve= 0 ,0
Exp/Cntr=0.3,0.1

Type RM Length L Ch R = 1 ,15594   ,680,680,680
BEGIN DESCRIPTION:
Indian Field Swamp 31.0
END DESCRIPTION:
XS GIS Cut Line= 3
      2150534.17        458211.2      2149460.04       459112.86
      2148121.44       460273.48
#Sta/Elev= 30
  3596.7   70.48  3646.7   71.52  3866.7   70.04  3996.7   72.91  4026.7    72.2
  4106.7   66.69  4176.7   64.48  4226.7   61.36  4286.7   54.14  4316.7   53.99
  4386.7   49.28  4516.7   46.26  4676.7   47.15  4776.7   46.54  4876.7   48.31
  4906.7    46.4  4956.7   46.64  4962.1   44.26  4963.6   41.26  5036.4   41.26
  5037.9   44.26  5119.1   46.74  5249.1   46.64  5319.1   48.99  5389.1   48.83
  5419.1   49.87  6489.1   49.93  6589.1    51.6  6649.1   54.49  6770.8   56.84
#Mann= 3 ,-1,0
  3596.7     .13       0  4962.1    .045       0  5037.9     .13       0
#XS Ineff= 2 , 0
       0    4250    58.2    6000       0    58.2
Permanent Ineff=
       F       F
Bank Sta=4962.1,5037.9
XS Rating Curve= 0 ,0
Exp/Cntr=0.3,0.1

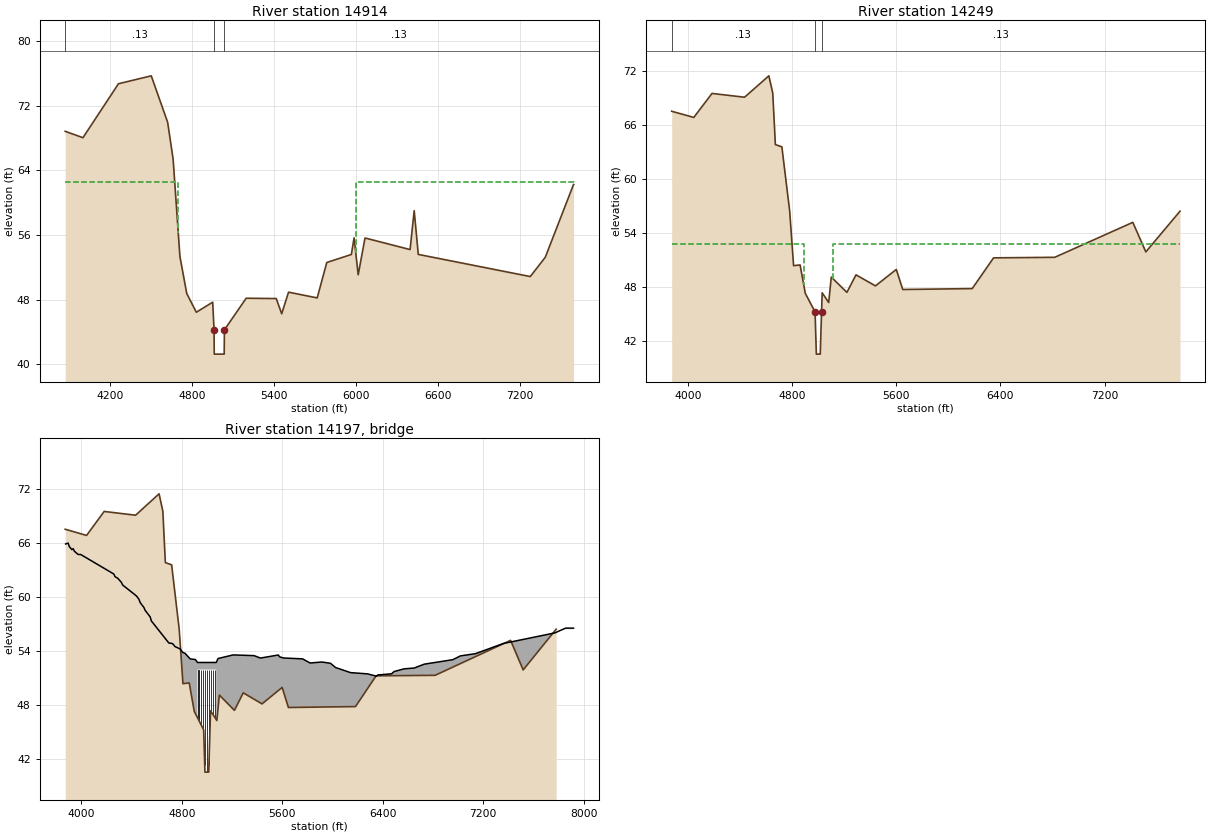
Type RM Length L Ch R = 1 ,14914   ,665,665,665
BEGIN DESCRIPTION:
Indian Field Swamp 30.0
END DESCRIPTION:
XS GIS Cut Line= 3
      2150360.93       457859.09      2149428.78       458489.37
      2147278.39       459944.87
#Sta/Elev= 30
  3872.3   68.82  4002.3   68.03  4262.3    74.7  4502.3   75.68  4622.3   69.94
  4662.3    65.4  4712.3   53.33  4762.3   48.76  4832.3   46.45  4952.3   47.69
  4962.1   44.27  4963.6   41.27  5036.4   41.27  5037.9   44.27  5197.5   48.18
  5417.5   48.14  5457.5   46.26  5507.5   48.93  5717.5   48.22  5787.5    52.6
  5967.5   53.59  5987.5   55.65  6017.5   51.08  6067.5   55.63  6397.5    54.2
  6427.5   59.01  6457.5    53.6  7277.5   50.86  7387.5   53.25  7594.2   62.24
#Mann= 3 ,-1,0
  3872.3     .13       0  4962.1    .045       0  5037.9     .13       0
#XS Ineff= 2 , 0
       0    4700   62.55    6000       0   62.55
Permanent Ineff=
       F       F
Bank Sta=4962.1,5037.9
XS Rating Curve= 0 ,0
Exp/Cntr=0.5,0.3

Type RM Length L Ch R = 1 ,14249   ,145,145,145
BEGIN DESCRIPTION:
Wire Road at Indian Field - US
END DESCRIPTION:
XS GIS Cut Line= 6
      2150331.21        457790.4        2149726.       457835.87
      2148651.82       458181.42      2148432.18       458180.96
      2148057.87       458129.72      2146946.67       459242.47
#Sta/Elev= 30
  3873.1   67.56  4043.1   66.87  4183.1   69.54  4433.1   69.12    4620    71.5
    4650   69.57    4670   63.85    4720    63.6    4780   56.46    4810   50.38
    4860   50.46    4900    47.3    4975   45.24    4985   40.54    5015   40.54
    5025   45.24  5029.8   47.36  5079.8   46.28  5099.8   49.11  5219.8   47.41
  5289.8   49.36  5439.2   48.13  5599.2   49.96  5649.1   47.73  6182.8   47.83
    6347   51.25    6817   51.31    7417    55.2    7517   51.91  7779.6   56.44
#Mann= 3 ,-1,0
  3873.1     .13       0    4975    .045       0    5025     .13       0
#XS Ineff= 2 , 0
       0    4888   52.75    5112       0   52.75
Permanent Ineff=
       F       F
Bank Sta=4975,5025
XS Rating Curve= 0 ,0
Exp/Cntr=0.5,0.3

Type RM Length L Ch R = 3 ,14197   ,,,
BEGIN DESCRIPTION:
Wire Road at Indian Field - TOR
Structure ID: LDS_IFS_01
Approximate Survey Structure
END DESCRIPTION:
Bridge Culvert--1,0,-1,-1, 0
Deck Dist Width WeirC Skew NumUp NumDn MinLoCord MaxHiCord MaxSubmerge Is_Ogee
37.5,29,3,0, 60, 60, , , 0.95, 0, 1,1,,
  3876.3  3896.3  3906.3  3926.3  3936.3  3946.3  3976.3  3996.3  4259.8  4269.8
  4289.8  4319.8  4329.8  4439.1  4459.1  4469.1  4499.1  4509.1  4549.1  4559.1
  4697.3  4727.3  4747.3  4787.3  4807.3  4827.3  4867.3  4909.6  4925.5  4925.5
  5074.5  5074.5  5089.3  5209.3  5376.1  5426.1  5568.7  5578.7  5608.7    5762
    5822  5915.1  5983.8  6023.8  6143.8    6280    6350    6360    6470    6490
    6570    6650    6730  6957.7  7017.7  7137.7  7359.6  7769.6  7854.6  7917.8
   65.92   66.02   65.62   65.29    65.4   65.11   64.75   64.75   62.58   62.28
   62.12   61.66   61.36   60.15   59.79   59.41   58.86   58.54   57.81   57.35
   54.91   54.84    54.5   54.25   53.87   53.75   53.14   53.06   52.74   52.74
   52.74   52.74   53.18   53.58    53.5   53.23   53.57   53.37   53.24   53.14
   52.68   52.79   52.65   52.18   51.61   51.47   51.21   51.35   51.48   51.73
   52.03   52.12   52.55   53.05   53.47   53.72   54.85   56.03   56.56   56.56
   20.54   20.54   20.54   20.54   20.54   20.54   20.54   20.54   20.54   20.54
   20.54   20.54   20.54   20.54   20.54   20.54   20.54   20.54   20.54   20.54
   20.54   20.54   20.54   20.54   20.54   20.54   20.54   20.54   20.54   51.94
   51.94   20.54   20.54   20.54   20.54   20.54   20.54   20.54   20.54   20.54
   20.54   20.54   20.54   20.54   20.54   20.54   20.54   20.54   20.54   20.54
   20.54   20.54   20.54   20.54   20.54   20.54   20.54   20.54   20.54   20.54
  3876.3  3896.3  3906.3  3926.3  3936.3  3946.3  3976.3  3996.3  4259.8  4269.8
  4289.8  4319.8  4329.8  4439.1  4459.1  4469.1  4499.1  4509.1  4549.1  4559.1
  4697.3  4727.3  4747.3  4787.3  4807.3  4827.3  4867.3  4909.6  4925.5  4925.5
  5074.5  5074.5  5089.3  5209.3  5376.1  5426.1  5568.7  5578.7  5608.7    5762
    5822  5915.1  5983.8  6023.8  6143.8    6280    6350    6360    6470    6490
    6570    6650    6730  6957.7  7017.7  7137.7  7359.6  7769.6  7854.6  7917.8
   65.92   66.02   65.62   65.29    65.4   65.11   64.75   64.75   62.58   62.28
   62.12   61.66   61.36   60.15   59.79   59.41   58.86   58.54   57.81   57.35
   54.91   54.84    54.5   54.25   53.87   53.75   53.14   53.06   52.74   52.74
   52.74   52.74   53.18   53.58    53.5   53.23   53.57   53.37   53.24   53.14
   52.68   52.79   52.65   52.18   51.61   51.47   51.21   51.35   51.48   51.73
   52.03   52.12   52.55   53.05   53.47   53.72   54.85   56.03   56.56   56.56
   20.54   20.54   20.54   20.54   20.54   20.54   20.54   20.54   20.54   20.54
   20.54   20.54   20.54   20.54   20.54   20.54   20.54   20.54   20.54   20.54
   20.54   20.54   20.54   20.54   20.54   20.54   20.54   20.54   20.54   51.94
   51.94   20.54   20.54   20.54   20.54   20.54   20.54   20.54   20.54   20.54
   20.54   20.54   20.54   20.54   20.54   20.54   20.54   20.54   20.54   20.54
   20.54   20.54   20.54   20.54   20.54   20.54   20.54   20.54   20.54   20.54
Pier Skew, UpSta & Num, DnSta & Num=  ,4933.8, 2 ,4933.8, 2 , 0 , 0 , 0 ,0,0
     1.1     1.1
   46.59   51.94
     1.1     1.1
   46.56   51.94
Pier Skew, UpSta & Num, DnSta & Num=  ,4950.3, 2 ,4950.3, 2 , 0 , 0 , 0 ,0,0
     1.1     1.1
   46.21   51.94
     1.1     1.1
   45.93   51.94
Pier Skew, UpSta & Num, DnSta & Num=  ,4966.9, 2 ,4966.9, 2 , 0 , 0 , 0 ,0,0
     1.1     1.1
   46.47   51.94
     1.1     1.1
    45.3   51.94
Pier Skew, UpSta & Num, DnSta & Num=  ,4983.4, 2 ,4983.4, 2 , 0 , 0 , 0 ,0,0
     1.1     1.1
   41.29   51.94
     1.1     1.1
   41.04   51.94
Pier Skew, UpSta & Num, DnSta & Num=  ,5000, 2 ,5000, 2 , 0 , 0 , 0 ,0,0
     1.1     1.1
   40.54   51.94
     1.1     1.1
   40.29   51.94
Pier Skew, UpSta & Num, DnSta & Num=  ,5016.6, 2 ,5016.6, 2 , 0 , 0 , 0 ,0,0
     1.1     1.1
   41.29   51.94
     1.1     1.1
   41.04   51.94
Pier Skew, UpSta & Num, DnSta & Num=  ,5033.1, 2 ,5033.1, 2 , 0 , 0 , 0 ,0,0
     1.1     1.1
   45.89   51.94
     1.1     1.1
   49.33   51.94
Pier Skew, UpSta & Num, DnSta & Num=  ,5049.7, 2 ,5049.7, 2 , 0 , 0 , 0 ,0,0
     1.1     1.1
   46.07   51.94
     1.1     1.1
   48.83   51.94
Pier Skew, UpSta & Num, DnSta & Num=  ,5066.2, 2 ,5066.2, 2 , 0 , 0 , 0 ,0,0
     1.1     1.1
   46.57   51.94
     1.1     1.1
   48.61   51.94
Abutment Skew #Up #Dn= , 2 , 2
  4925.5  4938.5
   51.94   46.64
  4925.5  4938.5
   51.94   46.38
Abutment Skew #Up #Dn= , 2 , 2
  5061.5  5074.5
   46.61   51.94
  5061.5  5074.5
   48.52   51.94
BR Coef= 1 , 1 , 0 ,1.25, 0 ,,,0.8,0,2,0,
WSPro=,,,, 1 ,,,, 0 ,,,, 0 ,,,,-1 ,-1 ,-1 , 0 , 0 , 0 , 0 , 0
BC Design=,, 0 ,, 0 ,,,,,,
BC HTab HWMax=71.5
BC Use User HTab Curves=0
BC User HTab FreeFlow(D)= 0