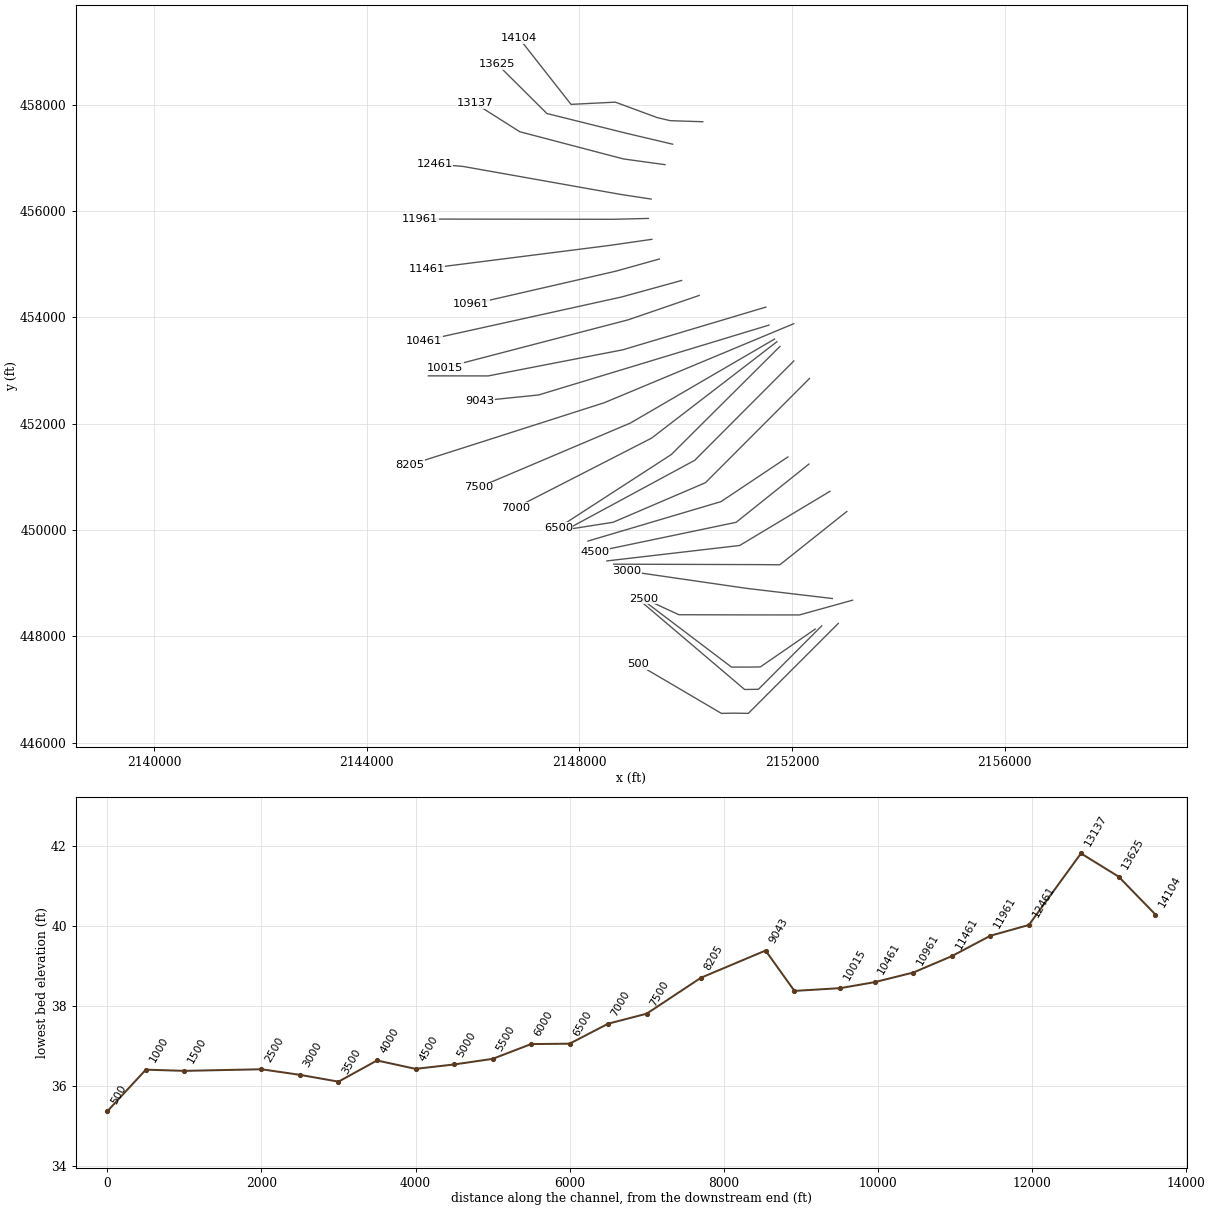
HEC-RAS study IndianFieldsSwamp.prj: S-18-19 over Indian Fields Swamp

--- IndianFieldsSwamp.g02 (geometry) --- (continued)

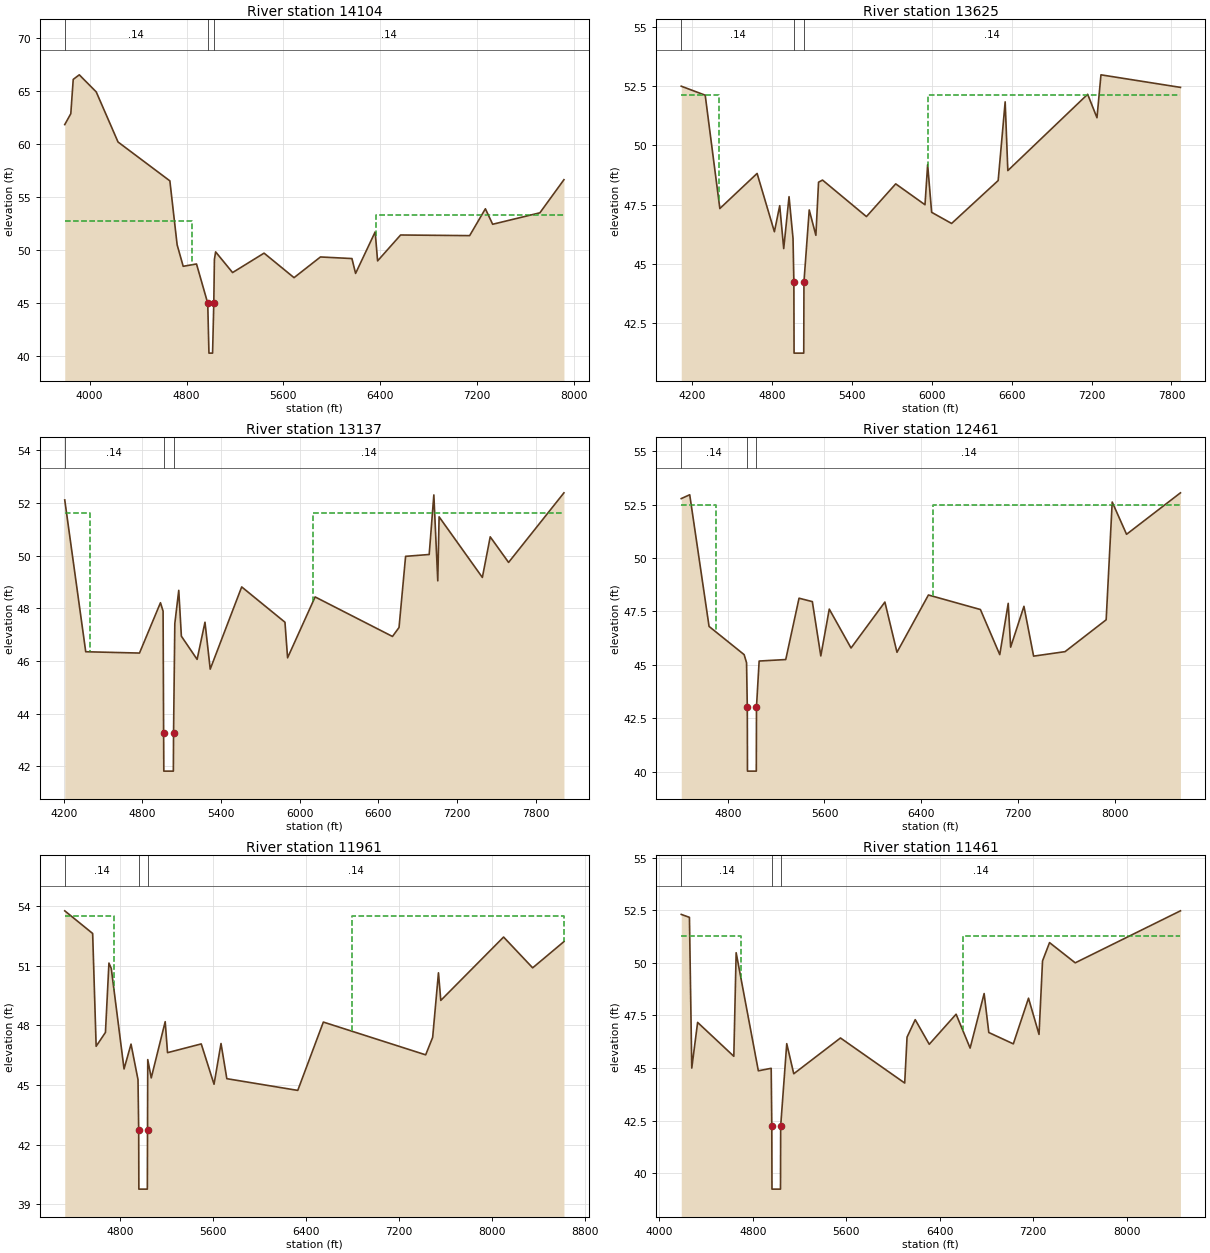
Type RM Length L Ch R = 1 ,14104   ,479,479,479
BEGIN DESCRIPTION:
Wire Road at Indian Field - DS
END DESCRIPTION:
XS GIS Cut Line= 6
      2150321.29       457678.17      2149710.37       457698.06
      2149460.59       457757.05      2148677.13       458046.49
      2147843.45       458005.06      2146868.62       459246.66
#Sta/Elev= 30
  3794.4   61.82  3844.4   62.85  3864.4   66.08  3914.4   66.51  4054.4    64.9
  4234.4   60.18  4662.3   56.52  4722.3    50.5  4772.3   48.47  4882.3   48.69
    4975   44.99    4985   40.29    5015   40.29    5025   44.99  5030.1   49.11
  5040.1   49.83  5180.1   47.88  5440.1   49.71  5687.6    47.4  5905.7   49.35
  6165.7    49.2  6195.7    47.8  6357.5   51.71  6377.5   48.98  6567.5   51.42
  7137.5   51.36  7267.5   53.89  7327.5   52.43  7717.5   53.51  7916.1   56.63
#Mann= 3 ,-1,0
  3794.4     .14       0    4975    .045       0    5025     .14       0
#XS Ineff= 2 , 0
       0    4847   52.74  6360.4       0   53.35
Permanent Ineff=
       F       F
Bank Sta=4975,5025
XS Rating Curve= 0 ,0
Exp/Cntr=0.5,0.3

Type RM Length L Ch R = 1 ,13625   ,488,488,488
BEGIN DESCRIPTION:
Indian Field Swamp 27.0
END DESCRIPTION:
XS GIS Cut Line= 4
       2149755.3       457255.72      2148897.04       457458.24
      2147390.32       457832.55      2146455.86       458761.23
#Sta/Elev= 30
  4115.8    52.5  4295.8   52.12  4405.8   47.34  4685.8   48.82  4815.8   46.36
  4855.8   47.46  4885.8   45.65  4925.8   47.84  4955.8   46.08  4962.1   44.24
  4963.6   41.24  5036.4   41.24  5037.9   44.24  5077.6   47.28  5127.6   46.21
  5147.6   48.45  5177.6   48.54  5507.6      47  5727.6   48.38  5947.6    47.5
  5967.6   49.19  5997.6   47.18  6147.6   46.71  6497.6   48.52  6550.2   51.84
  6570.2   48.94  7170.2   52.16  7240.2   51.17  7270.2   52.98  7867.6   52.45
#Mann= 3 ,-1,0
  4115.8     .14       0  4962.1    .045       0  5037.9     .14       0
#XS Ineff= 2 , 0
       0    4400   52.14  5969.3       0   52.14
Permanent Ineff=
       F       F
Bank Sta=4962.1,5037.9
XS Rating Curve= 0 ,0
Exp/Cntr=0.3,0.1

Type RM Length L Ch R = 1 ,13137   ,676,676,676
BEGIN DESCRIPTION:
Indian Field Swamp 26.0
END DESCRIPTION:
XS GIS Cut Line= 4
      2149611.14       456871.01      2148828.96       456978.58
      2146879.49       457490.28      2146033.17       458026.97
#Sta/Elev= 30
  4208.1   52.11  4368.1   46.35  4778.1    46.3  4938.1   48.21  4958.1   47.89
  4962.1   43.26  4963.6   41.82  5036.4   41.82  5037.9   43.26  5047.6   47.42
  5077.6   48.68  5097.6   46.94  5217.6   46.06  5277.6   47.47  5317.6   45.69
  5557.6   48.81  5887.6   47.47  5907.6   46.12  6117.6   48.43  6707.6   46.93
  6757.6   47.27  6807.6   49.97  6987.6   50.04  7023.1    52.3  7053.1   49.04
  7063.1   51.47  7393.1   49.17  7453.1   50.71  7593.1   49.74  8015.3   52.38
#Mann= 3 ,-1,0
  4208.1     .14       0  4962.1    .045       0  5037.9     .14       0
#XS Ineff= 2 , 0
       0    4400   51.63    6100       0   51.63
Permanent Ineff=
       F       F
Bank Sta=4962.1,5037.9
XS Rating Curve= 0 ,0
Exp/Cntr=0.3,0.1

Type RM Length L Ch R = 1 ,12461   ,500,500,500
BEGIN DESCRIPTION:
Indian Field Swamp 25.0
END DESCRIPTION:
XS GIS Cut Line= 4
      2149349.72        456224.2      2148772.28       456312.12
      2145819.84        456836.6      2145276.23       456884.77
#Sta/Elev= 30
  4415.9   52.78  4485.9   52.96  4645.9    46.8  4935.9   45.48  4955.9    45.1
    4962   43.03  4963.5   40.03  5036.5   40.03    5038   43.03    5060   45.18
    5280   45.25    5390   48.12    5500   47.96    5570   45.42    5640   47.61
    5820   45.79    6100   47.94    6200   45.59    6460   48.27    6890   47.59
    7050   45.48    7120   47.88    7140   45.83    7250   47.74    7330   45.41
    7590   45.62    7930   47.11    7980   52.62  8098.7   51.11  8544.4   53.05
#Mann= 3 ,-1,0
  4415.9     .14       0    4962    .045       0    5038     .14       0
#XS Ineff= 2 , 0
       0    4700   52.48    6500       0   52.48
Permanent Ineff=
       F       F
Bank Sta=4962,5038
XS Rating Curve= 0 ,0
Exp/Cntr=0.3,0.1

Type RM Length L Ch R = 1 ,11961   ,500,500,500
BEGIN DESCRIPTION:
Indian Field Swamp 24.0
END DESCRIPTION:
XS GIS Cut Line= 3
      2149295.53       455859.86      2148621.93       455843.53
      2145002.94       455847.87
#Sta/Elev= 30
  4326.2   53.77  4566.2   52.63  4596.2   46.95  4676.2   47.65  4706.2   51.14
  4726.2   50.87  4836.2   45.81  4896.2   47.06  4956.2   45.27    4962   42.76
  4963.5   39.76  5036.5   39.76    5038   42.76    5040   46.28    5070   45.36
    5190   48.19    5210   46.63    5500   47.07    5610   45.04    5670   47.09
    5720   45.32    6330   44.73    6550   48.17    7430   46.52    7490    47.4
    7540   50.65    7560   49.26    8100   52.45    8350    50.9    8619   52.22
#Mann= 3 ,-1,0
  4326.2     .14       0    4962    .045       0    5038     .14       0
#XS Ineff= 2 , 0
       0    4750    53.5    6800       0    53.5
Permanent Ineff=
       F       F
Bank Sta=4962,5038
XS Rating Curve= 0 ,0
Exp/Cntr=0.3,0.1

Type RM Length L Ch R = 1 ,11461   ,500,500,500
BEGIN DESCRIPTION:
Indian Field Swamp 23.0
END DESCRIPTION:
XS GIS Cut Line= 3
      2149363.38       455466.87       2148558.5       455350.84
       2145125.1       454915.48
#Sta/Elev= 30
  4186.8    52.3  4256.8   52.16  4276.8      45  4326.8   47.17  4636.8   45.56
  4656.8   50.48  4846.8   44.87  4956.8   44.99    4962   42.25  4963.5   39.25
  5036.5   39.25    5038   42.25    5090   46.16    5150   44.73    5550   46.43
    6100   44.29    6120   46.47    6190    47.3    6310   46.13    6540   47.56
    6660   45.95    6780   48.54    6820   46.69    7030   46.15    7160   48.32
    7250    46.6    7280   50.09    7340   50.96    7560      50  8460.9   52.47
#Mann= 3 ,-1,0
  4186.8     .14       0    4962    .045       0    5038     .14       0
#XS Ineff= 2 , 0
       0    4700   51.27    6600       0   51.27
Permanent Ineff=
       F       F
Bank Sta=4962,5038
XS Rating Curve= 0 ,0
Exp/Cntr=0.3,0.1

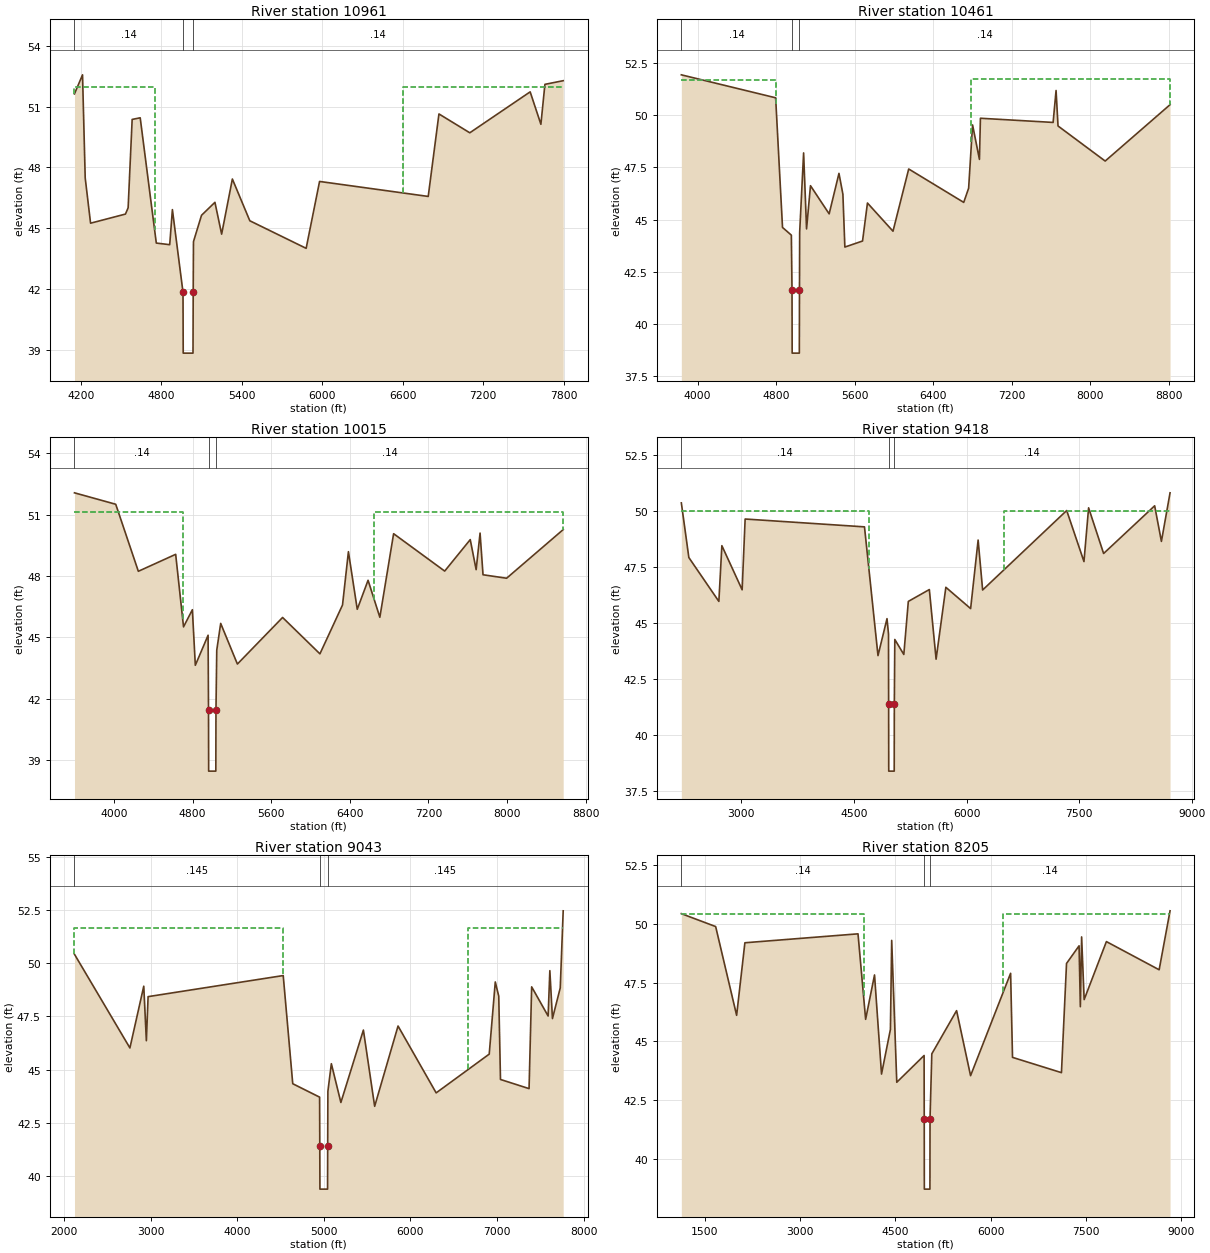
Type RM Length L Ch R = 1 ,10961   ,500,500,500
BEGIN DESCRIPTION:
Indian Field Swamp 22.0
END DESCRIPTION:
XS GIS Cut Line= 3
      2149503.29       455096.53      2148687.49        454868.4
      2145962.28       454242.32
#Sta/Elev= 30
  4152.9   51.63  4212.9   52.57  4232.9   47.48  4272.9   45.25  4532.9    45.7
  4552.9   46.01  4582.9   50.37  4642.9   50.45  4762.9   44.27  4862.9   44.19
  4882.9   45.92    4962   41.84  4963.5   38.84  5036.5   38.84    5038   41.84
    5040   44.34    5100   45.64    5200   46.28    5250   44.71    5330   47.43
    5460   45.37    5880   44.01    5980   47.31    6790   46.57    6870   50.64
    7100   49.71    7550   51.73    7630   50.13    7660    52.1  7796.2   52.28
#Mann= 3 ,-1,0
  4152.9     .14       0    4962     .05       0    5038     .14       0
#XS Ineff= 2 , 0
       0    4750   51.96    6600       0   51.96
Permanent Ineff=
       F       F
Bank Sta=4962,5038
XS Rating Curve= 0 ,0
Exp/Cntr=0.3,0.1

Type RM Length L Ch R = 1 ,10461   ,446,446,446
BEGIN DESCRIPTION:
Indian Field Swamp 21.0
END DESCRIPTION:
XS GIS Cut Line= 3
        2149923.       454693.27       2148800.1       454384.06
      2145079.35       453562.37
#Sta/Elev= 30
  3835.3   51.93  4795.3   50.83  4865.3   44.62  4955.3   44.25    4962    41.6
  4963.5    38.6  5036.5    38.6    5038    41.6    5040   44.39    5080   48.19
    5110   44.55    5150   46.62    5340   45.27    5440   47.21    5480   46.21
    5500   43.68    5680   43.97    5730   45.79    5990   44.44    6150   47.42
    6710   45.82    6760    46.5    6800   49.53    6870   47.88    6880   49.85
    7620   49.65    7650   51.18    7670   49.48    8150    47.8  8810.4    50.5
#Mann= 3 ,-1,0
  3835.3     .14       0    4962     .05       0    5038     .14       0
#XS Ineff= 2 , 0
       0    4800   51.68  6789.1       0   51.74
Permanent Ineff=
       F       F
Bank Sta=4962,5038
XS Rating Curve= 0 ,0
Exp/Cntr=0.3,0.1

Type RM Length L Ch R = 1 ,10015   ,597,597,597
BEGIN DESCRIPTION:
Indian Field Swamp 20.0
END DESCRIPTION:
XS GIS Cut Line= 3
      2150253.02        454411.4       2148921.2       453953.99
      2145470.59       453054.11
#Sta/Elev= 30
  3597.8   52.07  4017.8   51.51  4247.8   48.23  4627.8   49.06  4707.8   45.51
  4797.8   46.35  4827.8   43.63  4957.8    45.1    4962   41.45  4963.5   38.45
  5036.5   38.45    5038   41.45    5046   44.37    5086   45.68    5256   43.69
    5716   45.97    6096   44.19    6326   46.58    6386   49.19    6476   46.37
    6586   47.79    6706   45.98    6846   50.07    7366   48.24    7626   49.78
    7686   48.31    7726    50.1    7756   48.06    7996   47.89    8572   50.27
#Mann= 3 ,-1,0
  3597.8     .14       0    4962     .05       0    5038     .14       0
#XS Ineff= 2 , 0
       0    4700   51.14    6650       0   51.14
Permanent Ineff=
       F       F
Bank Sta=4962,5038
XS Rating Curve= 0 ,0
Exp/Cntr=0.3,0.1

Type RM Length L Ch R = 1 ,9418    ,375,375,375
BEGIN DESCRIPTION:
Indian Field Swamp 18.0
END DESCRIPTION:
XS GIS Cut Line= 4
      2151507.18       454192.38       2148820.4       453390.12
       2146285.9       452898.23      2145160.79       452899.44
#Sta/Elev= 30
  2200.4   50.36  2300.4   47.92  2700.4   45.96  2740.4   48.45  3010.4   46.48
  3050.4   49.64  4640.4   49.29  4820.4   43.54  4940.4   45.19  4960.4    44.5
    4962   41.38  4963.5   38.38  5036.5   38.38    5038   41.38  5044.4   44.26
  5164.4   43.59  5224.4   45.96  5504.4   46.49  5594.4   43.38  5724.4   46.59
  6054.4   45.64  6154.4    48.7  6214.4   46.47  7334.4   50.02  7564.4   47.74
  7626.2   50.14  7826.2    48.1  8506.2   50.23  8596.2   48.64  8711.3   50.81
#Mann= 3 ,-1,0
  2200.4     .14       0    4962     .05       0    5038     .14       0
#XS Ineff= 2 , 0
       0    4700   49.98    6500       0   49.98
Permanent Ineff=
       F       F
Bank Sta=4962,5038
XS Rating Curve= 0 ,0
Exp/Cntr=0.3,0.1

Type RM Length L Ch R = 1 ,9043    ,838,838,838
BEGIN DESCRIPTION:
Indian Field Swamp 17.0
END DESCRIPTION:
XS GIS Cut Line= 4
      2151566.96       453853.95      2148805.45       453016.61
      2147233.49       452539.97      2146125.22       452427.15
#Sta/Elev= 30
  2122.2   50.42  2762.2   46.02  2922.2   48.92  2952.2   46.36  2972.2   48.43
  4532.2   49.42  4642.2   44.34  4952.2   43.71  4954.4    41.4  4955.9   39.39
  5044.1   39.39  5045.6   41.42  5047.9   43.98  5087.9   45.28  5197.9   43.46
  5457.9   46.86  5587.9   43.28  5857.9   47.05  6297.9   43.91  6910.5   45.73
  6980.5   49.12  7020.5   48.45  7040.5   44.54  7370.5   44.11  7400.5   48.89
  7590.5   47.52  7610.5   49.65  7640.5    47.4  7730.5   48.84  7764.5   52.46
#Mann= 3 ,-1,0
  2122.2    .145       0  4954.4    .045       0  5045.6    .145       0
#XS Ineff= 2 , 0
       0  4525.8   51.67  6669.9       0   51.67
Permanent Ineff=
       F       F
Bank Sta=4954.4,5045.6
XS Rating Curve= 0 ,0
Exp/Cntr=0.3,0.1

Type RM Length L Ch R = 1 ,8205    ,705,705,705
BEGIN DESCRIPTION:
Indian Field Swamp 16.0
END DESCRIPTION:
XS GIS Cut Line= 4
      2152031.49       453880.49      2148467.83       452393.97
      2146194.13       451666.13      2144820.77       451227.92
#Sta/Elev= 30
  1132.3   50.44  1672.3   49.89  2002.3   46.11  2132.3    49.2  3912.3   49.58
  4032.3   45.94  4172.3   47.83  4282.3   43.61  4422.3   45.51  4442.3    49.3
  4522.3   43.26  4952.3    44.4  4954.4   41.71  4955.9   38.71  5044.1   38.71
  5045.6   41.71  5073.6   44.47  5463.6   46.31  5683.6   43.54  6313.6    47.9
  6343.6   44.32  7113.6   43.67  7193.6   48.32  7390.9   49.07  7410.9   46.48
  7430.9   49.45  7470.9   46.78  7820.9   49.25  8650.9   48.05  8822.5   50.56
#Mann= 3 ,-1,0
  1132.3     .14       0  4954.4     .05       0  5045.6     .14       0
#XS Ineff= 2 , 0
       0    4000   50.41    6200       0   50.41
Permanent Ineff=
       F       F
Bank Sta=4954.4,5045.6
XS Rating Curve= 0 ,0
Exp/Cntr=0.3,0.1

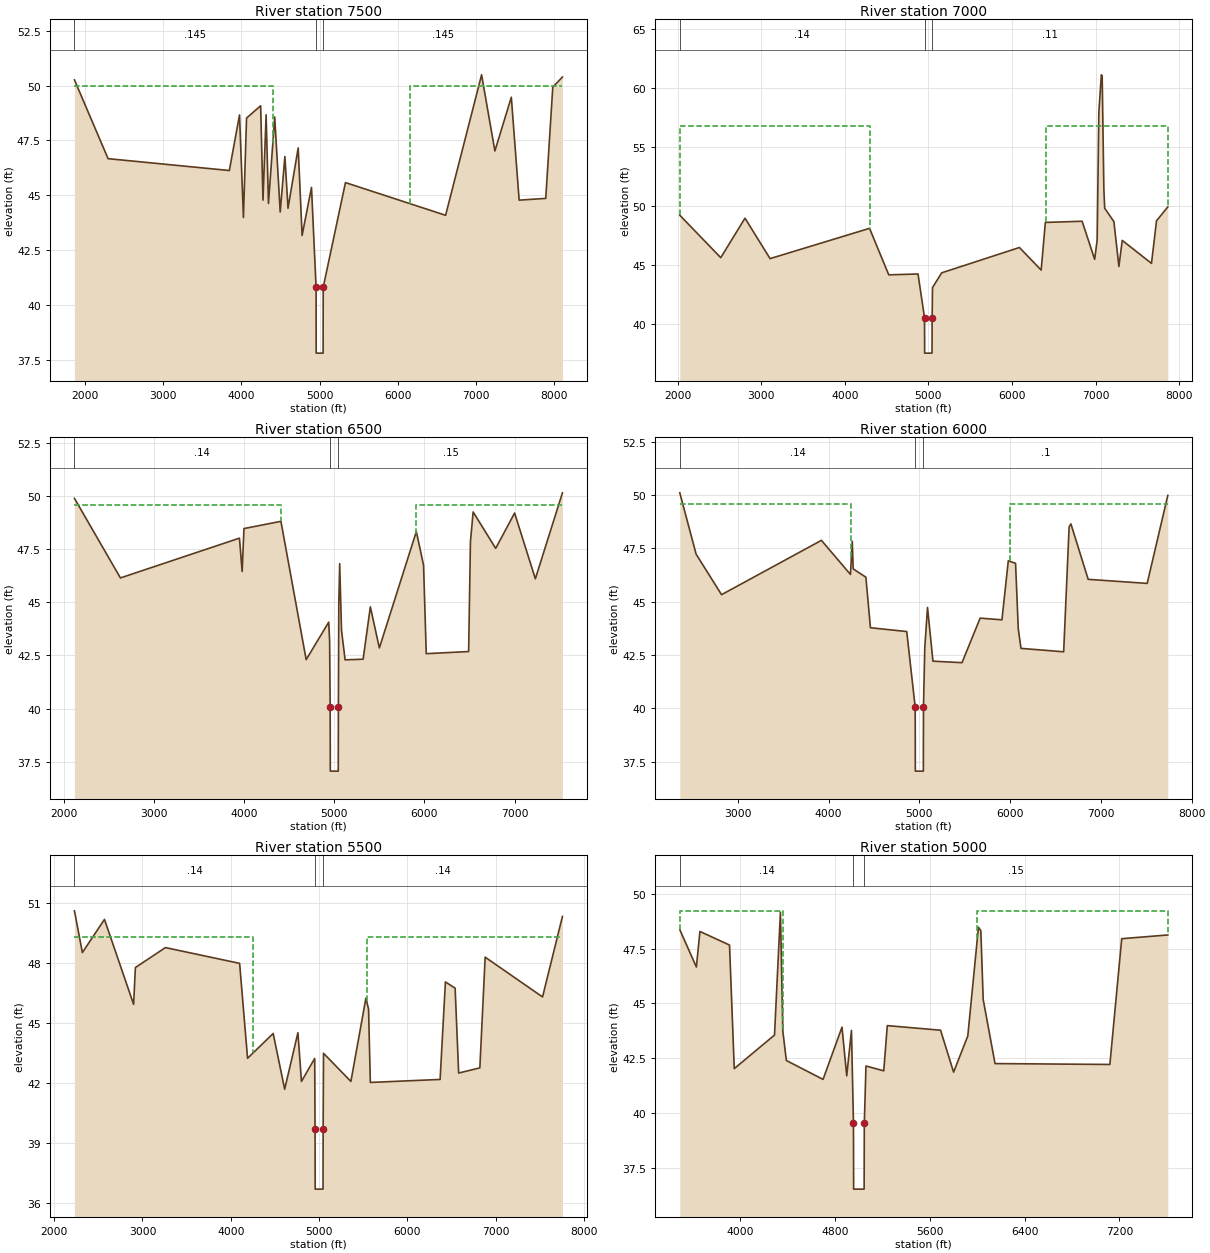
Type RM Length L Ch R = 1 ,7500    ,500,500,500
BEGIN DESCRIPTION:
Indian Field Swamp 15.0
END DESCRIPTION:
XS GIS Cut Line= 3
       2151670.5       453590.95      2148962.38        452013.2
       2146105.3       450801.26
#Sta/Elev= 30
  1865.8   50.26  2295.8   46.67  3845.8   46.13  3975.8   48.66  4025.8   43.99
  4065.8   48.52  4245.8   49.08  4275.8   44.78  4315.8   48.67  4345.8   44.63
  4425.8   48.57  4495.8   44.24  4555.8   46.77  4595.8   44.41  4725.8   47.16
  4775.8   43.17  4895.8   45.36  4954.4   40.81  4955.9   37.81  5044.1   37.81
  5045.6   40.81    5330   45.58    6610   44.09    7070   50.49    7240   47.02
    7450   49.47    7550   44.78    7890   44.86    7980   49.93  8103.5   50.39
#Mann= 3 ,-1,0
  1865.8    .145       0  4954.4    .045       0  5045.6    .145       0
#XS Ineff= 2 , 0
       0    4400   49.99  6159.3       0   49.99
Permanent Ineff=
       F       F
Bank Sta=4954.4,5045.6
XS Rating Curve= 0 ,0
Exp/Cntr=0.3,0.1

Type RM Length L Ch R = 1 ,7000    ,500,500,500
BEGIN DESCRIPTION:
Indian Field Swamp 14.0
END DESCRIPTION:
XS GIS Cut Line= 3
      2151715.06       453540.82      2149358.01       451728.25
      2146808.12       450421.77
#Sta/Elev= 30
  2026.6   49.22  2516.6   45.63  2806.6   48.97  3106.6   45.55  4296.6   48.11
  4526.6   44.18  4876.6   44.25  4954.4   40.56  4955.9   37.56  5044.1   37.56
  5045.6   40.56    5050    43.1    5160   44.35    6090   46.49    6350   44.58
    6400   48.61    6840   48.71    6990   45.49    7020   47.13    7040   57.89
    7070   61.09    7080   60.98    7100   51.45    7110   49.81    7220   48.68
    7280   44.89    7320   47.09    7670   45.15    7730   48.75  7865.1   49.92
#Mann= 3 ,-1,0
  2026.6     .14       0  4954.4    .045       0  5045.6     .11       0
#XS Ineff= 2 , 0
       0    4300   56.74    6406       0   56.74
Permanent Ineff=
       F       F
Bank Sta=4954.4,5045.6
XS Rating Curve= 0 ,0
Exp/Cntr=0.3,0.1

Type RM Length L Ch R = 1 ,6500    ,500,500,500
BEGIN DESCRIPTION:
Indian Field Swamp 13.0
END DESCRIPTION:
XS GIS Cut Line= 3
      2151770.76       453451.72      2149728.11       451419.05
      2147604.56       450043.01
#Sta/Elev= 30
  2118.3   49.88  2628.3   46.14  3948.3   48.01  3978.3   46.44  3998.3   48.46
  4408.3    48.8  4688.3    42.3  4938.3   44.06  4948.3   43.17  4954.4   40.06
  4955.9   37.06  5044.1   37.06  5045.6   40.06    5050   44.92    5060   46.81
    5080   43.68    5120   42.29    5320   42.32    5400   44.78    5500   42.85
    5910   48.32    5990   46.74    6020   42.58    6490   42.68    6510   47.84
    6540   49.24    6790   47.53    7000   49.19    7230    46.1  7530.4   50.14
#Mann= 3 ,-1,0
  2118.3     .14       0  4954.4    .045       0  5045.6     .15       0
#XS Ineff= 2 , 0
       0  4403.7   49.55  5902.8       0   49.55
Permanent Ineff=
       F       F
Bank Sta=4954.4,5045.6
XS Rating Curve= 0 ,0
Exp/Cntr=0.3,0.1

Type RM Length L Ch R = 1 ,6000    ,500,500,500
BEGIN DESCRIPTION:
Indian Field Swamp 12.0
END DESCRIPTION:
XS GIS Cut Line= 3
      2152032.53       453178.79       2150168.7        451310.8
      2147760.55       450009.61
#Sta/Elev= 30
  2361.2   50.11  2541.2   47.23  2821.2   45.33  3921.2   47.88  4241.2   46.28
  4261.2   47.83  4271.2   46.54  4411.2   46.15  4461.2   43.78  4861.2    43.6
  4954.4   40.05  4955.9   37.05  5044.1   37.05  5045.6   40.05    5060   42.84
    5090   44.73    5150   42.21    5470   42.14    5670   44.23    5910   44.15
    5980   46.92    6060    46.8    6090   43.72    6120   42.81    6590   42.65
    6650   48.51    6670   48.65    6860   46.05    7510   45.86  7737.2   49.99
#Mann= 3 ,-1,0
  2361.2     .14       0  4954.4    .045       0  5045.6      .1       0
#XS Ineff= 2 , 0
       0    4250   49.58    6000       0   49.58
Permanent Ineff=
       F       F
Bank Sta=4954.4,5045.6
XS Rating Curve= 0 ,0
Exp/Cntr=0.3,0.1

Type RM Length L Ch R = 1 ,5500    ,500,500,500
BEGIN DESCRIPTION:
Indian Field Swamp 11.0
END DESCRIPTION:
XS GIS Cut Line= 4
      2152327.68       452850.14      2150370.77       450889.97
      2148633.76       450145.84      2147778.96        450011.4
#Sta/Elev= 30
  2230.2   50.61  2320.2   48.52  2570.2   50.18  2900.2   45.93  2920.2   47.77
  3260.2   48.77  4100.2   47.98  4190.2   43.23  4480.2   44.47  4610.2   41.68
  4760.2   44.51  4800.2   42.07  4950.2   43.22  4954.2   39.68  4955.7   36.68
  5044.3   36.68  5045.8   39.68    5050   43.48    5360   42.07    5530   46.24
    5560   45.69    5580   42.02    6370   42.17    6430   47.05    6540   46.74
    6580   42.49    6820   42.75    6880   48.29  7529.7    46.3    7755   50.33
#Mann= 3 ,-1,0
  2230.2     .14       0  4954.2     .05       0  5045.8     .14       0
#XS Ineff= 2 , 0
       0    4250   49.29  5538.3       0   49.29
Permanent Ineff=
       F       F
Bank Sta=4954.2,5045.8
XS Rating Curve= 0 ,0
Exp/Cntr=0.3,0.1

Type RM Length L Ch R = 1 ,5000    ,500,500,500
BEGIN DESCRIPTION:
Indian Field Swamp 10.0
END DESCRIPTION:
XS GIS Cut Line= 3
      2151921.14       451374.21      2150663.22        450534.2
      2148161.59        449792.4
#Sta/Elev= 30
  3487.4   48.36  3627.4   46.66  3657.4   48.28  3907.4   47.66  3947.4   42.03
  4287.4   43.56  4337.4   49.16  4357.4   43.75  4387.4    42.4  4697.4   41.54
  4857.4   43.92  4897.4    41.7  4937.4   43.77  4954.2   39.54  4955.7   36.54
  5044.3   36.54  5045.8   39.54    5060   42.15    5210   41.93    5240   43.99
    5690   43.78    5800   41.87    5920   43.52    6010   48.47    6030   48.31
    6050   45.18    6150   42.26    7120   42.22    7220   47.95  7609.3   48.12
#Mann= 3 ,-1,0
  3487.4     .14       0  4954.2    .045       0  5045.8     .15       0
#XS Ineff= 2 , 0
       0  4357.3    49.2    6000       0   49.22
Permanent Ineff=
       F       F
Bank Sta=4954.2,5045.8
XS Rating Curve= 0 ,0
Exp/Cntr=0.3,0.1

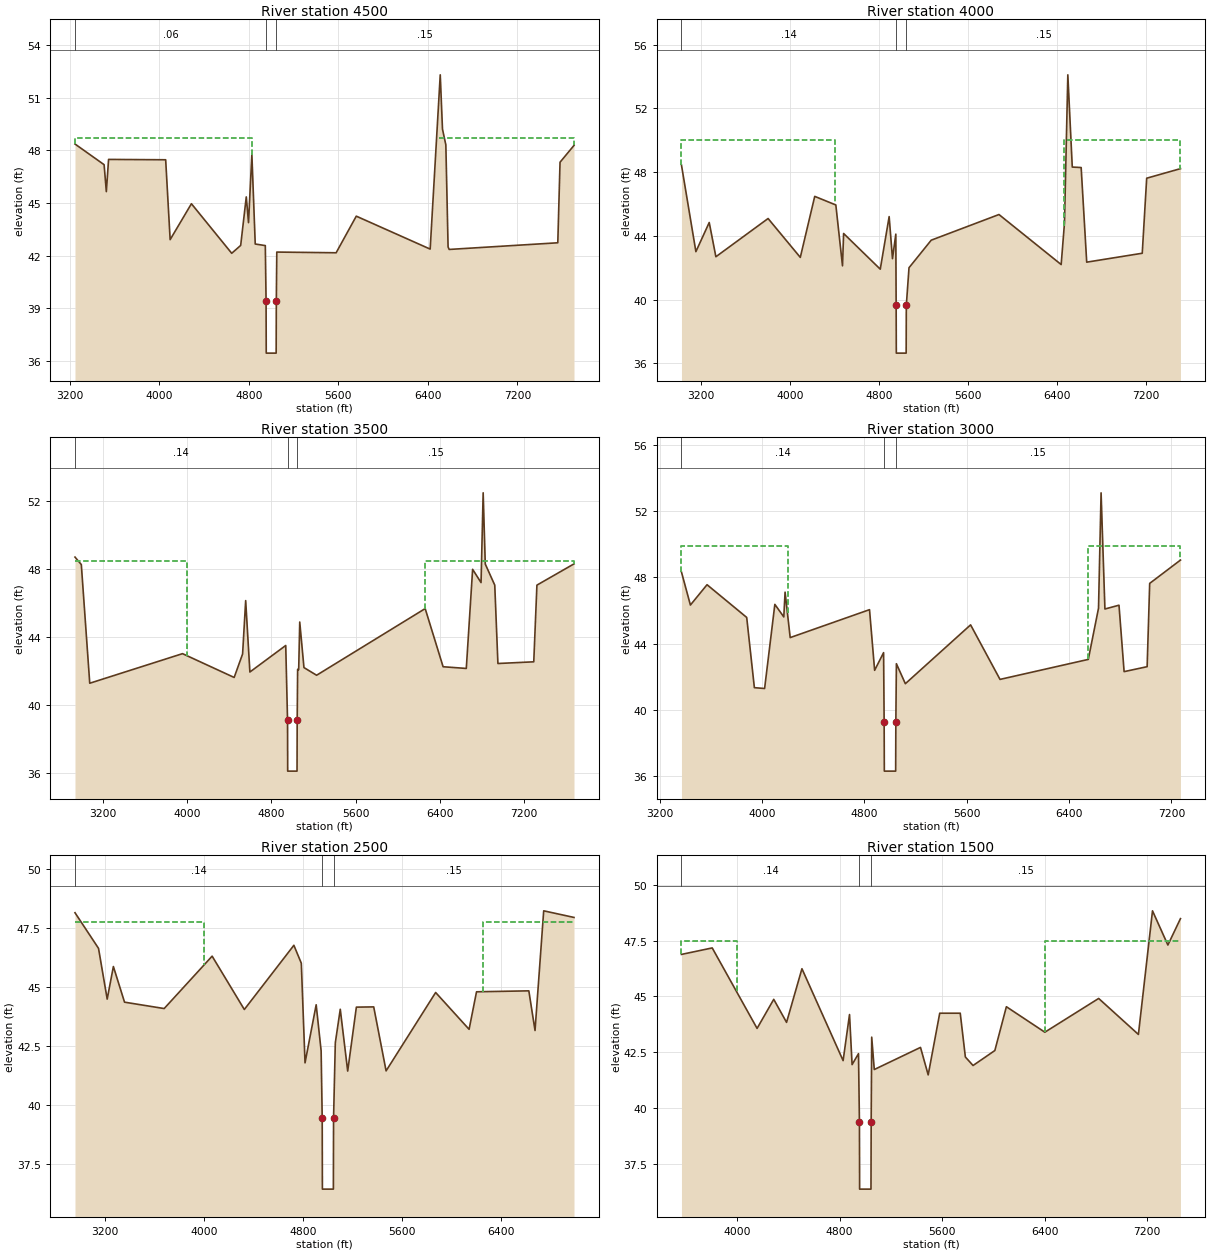
Type RM Length L Ch R = 1 ,4500    ,500,500,500
BEGIN DESCRIPTION:
Indian Field Swamp 9.0
END DESCRIPTION:
XS GIS Cut Line= 3
      2152316.58       451240.53      2150948.24       450145.42
      2148300.79       449591.88
#Sta/Elev= 30
  3247.4   48.37  3507.4   47.19  3527.4   45.65  3547.4   47.49  4057.4   47.47
  4097.4   42.91  4287.4   44.96  4647.4   42.13  4727.4   42.58  4777.4   45.35
  4797.4   43.88  4827.4   47.77  4857.4   42.66  4947.4   42.57  4954.2   39.43
  4955.7   36.43  5044.3   36.43  5045.8   39.43    5050    42.2    5580   42.16
    5760   44.25    6420   42.37    6510   52.32    6530   49.22    6560   48.32
    6580   42.49    6590   42.35    7560   42.73    7580   47.33  7704.7   48.29
#Mann= 3 ,-1,0
  3247.4     .06       0  4954.2     .04       0  5045.8     .15       0
#XS Ineff= 2 , 0
       0  4827.6   48.73    6500       0   48.73
Permanent Ineff=
       F       F
Bank Sta=4954.2,5045.8
XS Rating Curve= 0 ,0
Exp/Cntr=0.3,0.1

Type RM Length L Ch R = 1 ,4000    ,500,500,500
BEGIN DESCRIPTION:
Indian Field Swamp 8.0
END DESCRIPTION:
XS GIS Cut Line= 3
      2152711.97       450728.08      2151015.33       449709.73
      2148518.07       449419.23
#Sta/Elev= 30
  3021.2   48.45  3151.2   43.01  3271.2   44.84  3331.2   42.69  3801.2   45.09
  4091.2   42.65  4221.2   46.48  4411.2   45.94  4471.2   42.12  4481.2   44.15
  4811.2   41.91  4891.2   45.21  4921.2   42.57  4951.2   44.11  4954.2   39.64
  4955.7   36.64  5044.3   36.64  5045.8   39.64    5070      42    5270   43.73
    5880   45.34    6440    42.2    6470   44.82    6500   54.11    6540   48.32
    6620   48.29    6670   42.35    7170   42.91    7210   47.62  7514.1   48.22
#Mann= 3 ,-1,0
  3021.2     .14       0  4954.2     .04       0  5045.8     .15       0
#XS Ineff= 2 , 0
       0    4400   50.04  6467.4       0   50.04
Permanent Ineff=
       F       F
Bank Sta=4954.2,5045.8
XS Rating Curve= 0 ,0
Exp/Cntr=0.3,0.1

Type RM Length L Ch R = 1 ,3500    ,500,500,500
BEGIN DESCRIPTION:
Indian Field Swamp 7.0
END DESCRIPTION:
XS GIS Cut Line= 4
      2153029.49       450349.37      2151770.73       449346.82
      2151317.86       449350.13      2148646.17       449357.96
#Sta/Elev= 30
  2937.9    48.7  2997.9   48.26  3077.9   41.28  3957.9   43.02  4447.9   41.62
  4527.9      43  4557.1   46.14  4597.1   41.94  4937.1    43.5  4954.2   39.11
  4955.7   36.11  5044.3   36.11  5045.8   39.11    5050    42.1    5060   42.07
    5070   44.88    5110    42.2    5230   41.75    6260   45.67    6430   42.25
    6650   42.15    6710   47.98    6790    47.2    6810   52.48    6830   48.29
    6920   47.05    6950   42.44    7290   42.54    7320   47.05  7671.7    48.3
#Mann= 3 ,-1,0
  2937.9     .14       0  4954.2     .04       0  5045.8     .15       0
#XS Ineff= 2 , 0
       0    4000   48.47  6257.6       0   48.47
Permanent Ineff=
       F       F
Bank Sta=4954.2,5045.8
XS Rating Curve= 0 ,0
Exp/Cntr=0.3,0.1

Type RM Length L Ch R = 1 ,3000    ,500,500,500
BEGIN DESCRIPTION:
Indian Field Swamp 6.0
END DESCRIPTION:
XS GIS Cut Line= 3
      2152756.97        448712.4      2151138.17         448904.
      2148891.17       449229.86
#Sta/Elev= 30
  3369.9   48.33  3439.9   46.33  3569.9   47.56  3879.9   45.58  3939.9   41.33
  4019.9   41.28  4099.9   46.37  4169.9   45.61  4179.9   47.11  4219.9   44.36
  4839.9   46.05  4879.9   42.38  4949.9   43.45  4954.2   39.28  4955.7   36.28
  5044.3   36.28  5045.8   39.28    5050   42.78    5120   41.57    5630   45.13
    5860   41.83    6550   43.04    6630   46.14    6650   53.12    6680   46.09
    6790   46.32    6830    42.3    7010    42.6    7030   47.64  7270.5   49.05
#Mann= 3 ,-1,0
  3369.9     .14       0  4954.2     .04       0  5045.8     .15       0
#XS Ineff= 2 , 0
       0    4200   49.88    6550       0   49.88
Permanent Ineff=
       F       F
Bank Sta=4954.2,5045.8
XS Rating Curve= 0 ,0
Exp/Cntr=0.3,0.1

Type RM Length L Ch R = 1 ,2500    ,1000,1000,1000
BEGIN DESCRIPTION:
Indian Field Swamp 5.0
END DESCRIPTION:
XS GIS Cut Line= 5
      2153137.41       448680.62      2152138.02       448403.43
      2151133.53       448404.02      2149871.24       448407.59
      2149213.64       448711.91
#Sta/Elev= 30
  2958.4   48.13  3148.4   46.62  3218.4   44.47  3268.4   45.85  3358.4   44.34
  3678.4   44.07  4065.5   46.29  4325.5   44.03  4725.5   46.75  4785.5   45.99
  4815.5   41.77  4905.5   44.23  4945.5   42.28  4954.2   39.42  4955.7   36.42
  5044.3   36.42  5045.8   39.42    5060   42.62    5100   44.04    5160   41.42
    5230   44.13    5370   44.14    5470   41.43    5870   44.75    6140   43.19
    6200   44.78  6622.3   44.82  6672.3   43.14  6742.3   48.21  6986.9   47.93
#Mann= 3 ,-1,0
  2958.4     .14       0  4954.2     .04       0  5045.8     .15       0
#XS Ineff= 2 , 0
       0    4000   47.73    6250       0   47.73
Permanent Ineff=
       F       F
Bank Sta=4954.2,5045.8
XS Rating Curve= 0 ,0
Exp/Cntr=0.3,0.1

Type RM Length L Ch R = 1 ,1500    ,500,500,500
BEGIN DESCRIPTION:
Indian Field Swamp 3.0
END DESCRIPTION:
XS GIS Cut Line= 5
      2152434.46       448136.73      2151404.55       447426.27
      2151221.46       447422.93      2150860.73       447422.71
      2149188.42        448689.7
#Sta/Elev= 30
  3565.7   46.88  3805.7   47.17  4155.7   43.57  4285.7   44.87  4385.7   43.84
  4505.7   46.24  4826.9   42.13  4876.9   44.19  4896.9   41.95  4946.9   42.44
  4954.2   39.38  4955.7   36.38  5044.3   36.38  5045.8   39.38    5050   43.18
    5070   41.73  5430.7   42.72  5490.7   41.49  5580.7   44.25  5740.7   44.25
  5780.7   42.29  5840.7   41.91  6010.7   42.58  6100.7   44.54  6400.7    43.4
  6820.7   44.91  7130.7    43.3  7240.7   48.83  7360.7    47.3  7458.8   48.48
#Mann= 3 ,-1,0
  3565.7     .14       0  4954.2     .04       0  5045.8     .15       0
#XS Ineff= 2 , 0
       0    4000   47.47    6400       0   47.47
Permanent Ineff=
       F       F
Bank Sta=4954.2,5045.8
XS Rating Curve= 0 ,0
Exp/Cntr=0.3,0.1

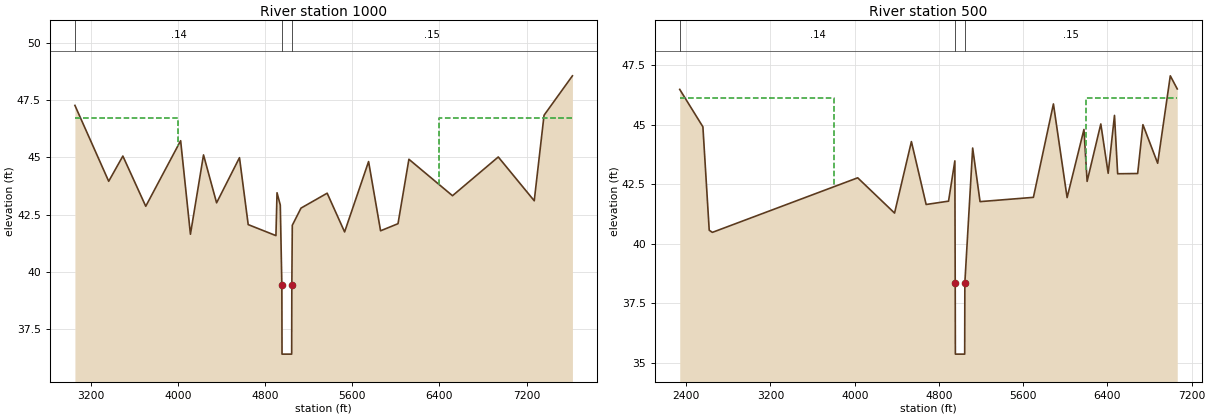
Type RM Length L Ch R = 1 ,1000    ,500,500,500
BEGIN DESCRIPTION:
Indian Field Swamp 2.0
END DESCRIPTION:
XS GIS Cut Line= 4
      2152557.07       448198.02      2151367.75       447005.12
      2151107.66       447001.57      2149110.65       448698.18
#Sta/Elev= 30
  3055.4   47.26  3365.4   43.95  3495.4   45.05  3705.4   42.86  4025.4   45.72
  4115.4   41.64  4235.4    45.1  4355.4   43.01  4565.4   44.98  4645.4   42.06
  4899.9   41.58  4909.9   43.45  4939.9   42.91  4954.2   39.41  4955.7   36.41
  5044.3   36.41  5045.8   39.41    5050   42.03    5130   42.78    5370   43.43
    5530   41.74    5750   44.81    5860   41.79    6020    42.1    6120   44.91
    6520   43.32    6940   45.01    7270    43.1    7360   46.83  7620.4   48.55
#Mann= 3 ,-1,0
  3055.4     .14       0  4954.2     .04       0  5045.8     .15       0
#XS Ineff= 2 , 0
       0    4000   46.71    6400       0   46.71
Permanent Ineff=
       F       F
Bank Sta=4954.2,5045.8
XS Rating Curve= 0 ,0
Exp/Cntr=0.3,0.1

Type RM Length L Ch R = 1 ,500     ,500,500,500
BEGIN DESCRIPTION:
Indian Field Swamp 1.0
END DESCRIPTION:
XS GIS Cut Line= 5
       2152868.9       448244.07      2151177.11       446552.28
      2150907.89       446556.57      2150671.11       446552.28
      2149096.93       447477.37
#Sta/Elev= 30
  2338.2   46.48  2558.2   44.91  2618.2   40.57  2648.2   40.48  4028.2   42.77
  4378.2   41.29  4538.2   44.29  4678.2   41.65  4890.8   41.79  4950.8   43.48
  4954.2   38.37  4955.7   35.37  5044.3   35.37  5045.8   38.37    5120   44.02
    5190   41.77  5696.8   41.95  5886.8   45.87  6016.8   41.94  6176.8    44.8
  6206.8   42.62  6336.8   45.03  6406.8   42.96  6466.8   45.39  6496.8   42.94
  6686.8   42.95  6736.8      45  6876.8   43.38  6996.8   47.05  7062.7    46.5
#Mann= 3 ,-1,0
  2338.2     .14       0  4954.2     .04       0  5045.8     .15       0
#XS Ineff= 2 , 0
       0    3800   46.13    6200       0   46.13
Permanent Ineff=
       F       F
Bank Sta=4954.2,5045.8
XS Rating Curve= 0 ,0
Exp/Cntr=0.3,0.1
LCMann Table=0

--- IndianFieldsSwamp.g07 (geometry) ---

Geom Title=Existing
Program Version=6.60

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
River Reach=Indian Field Swa,Reach-1

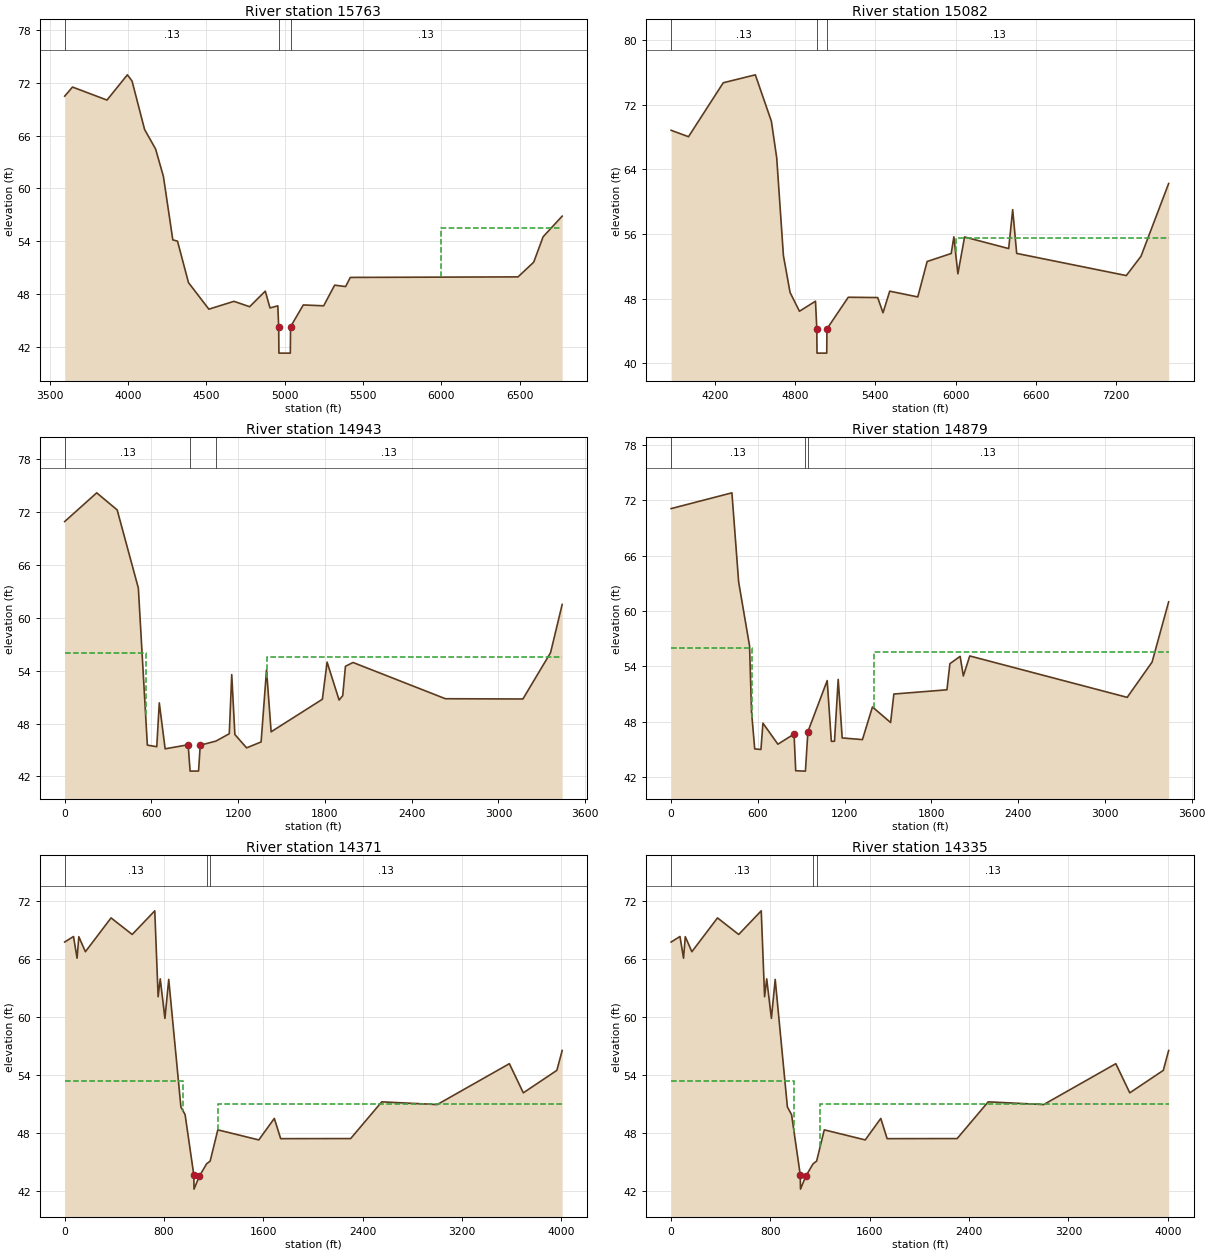
Type RM Length L Ch R = 1 ,15763   ,680,680,680
BEGIN DESCRIPTION:
Indian Field Swamp 31.0
END DESCRIPTION:
XS GIS Cut Line= 3
      2150534.17        458211.2      2149460.04       459112.86
      2148121.44       460273.48
#Sta/Elev= 30
  3596.7   70.48  3646.7   71.52  3866.7   70.04  3996.7   72.91  4026.7    72.2
  4106.7   66.69  4176.7   64.48  4226.7   61.36  4286.7   54.14  4316.7   53.99
  4386.7   49.28  4516.7   46.26  4676.7   47.15  4776.7   46.54  4876.7   48.31
  4906.7    46.4  4956.7   46.64  4962.1   44.26  4963.6   41.26  5036.4   41.26
  5037.9   44.26  5119.1   46.74  5249.1   46.64  5319.1   48.99  5389.1   48.83
  5419.1   49.87  6489.1   49.93  6589.1    51.6  6649.1   54.49  6770.8   56.84
#Mann= 3 ,-1,0
  3596.7     .13       0  4962.1    .045       0  5037.9     .13       0
#XS Ineff= 2 , 0
       0                    6000       0    55.5
Permanent Ineff=
       F       F
Bank Sta=4962.1,5037.9
XS Rating Curve= 0 ,0
Exp/Cntr=0.5,0.3

Type RM Length L Ch R = 1 ,15082   ,139.3,139.3,139.3
BEGIN DESCRIPTION:
Indian Field Swamp 30.0
END DESCRIPTION:
XS GIS Cut Line= 3
      2150360.93       457859.09      2149428.78       458489.37
      2147278.39       459944.87
#Sta/Elev= 30
  3872.3   68.82  4002.3   68.03  4262.3    74.7  4502.3   75.68  4622.3   69.94
  4662.3    65.4  4712.3   53.33  4762.3   48.76  4832.3   46.45  4952.3   47.69
  4962.1   44.27  4963.6   41.27  5036.4   41.27  5037.9   44.27  5197.5   48.18
  5417.5   48.14  5457.5   46.26  5507.5   48.93  5717.5   48.22  5787.5    52.6
  5967.5   53.59  5987.5   55.65  6017.5   51.08  6067.5   55.63  6397.5    54.2
  6427.5   59.01  6457.5    53.6  7277.5   50.86  7387.5   53.25  7594.2   62.24
#Mann= 3 ,-1,0
  3872.3     .13       0  4962.1    .045       0  5037.9     .13       0
#XS Ineff= 2 , 0
       0                    6000       0    55.5
Permanent Ineff=
       F       F
Bank Sta=4962.1,5037.9
XS Rating Curve= 0 ,0
Exp/Cntr=0.5,0.3

Type RM Length L Ch R = 1 ,14943   ,63.9,63.9,63.9
XS GIS Cut Line= 6
2150060.73179075457902.3452848622149544.11541243458255.135346235
2149361.73382409458373.7998231982149258.87973167458440.417532982
2148855.42888635458729.9528455062147263.22773477459904.409083364
#Sta/Elev= 30
       0    70.9   221.7   74.16   363.2   72.22   509.6   63.36  571.83   45.55
   636.9   45.37   654.4   50.34   694.9   45.13     854   45.59  867.56    42.6
  925.91   42.61  937.66   45.54  1046.8   46.01  1138.5   46.84 1155.49   53.55
 1177.18   46.75  1258.3   45.24 1358.59   45.91 1396.06   54.08  1427.9   47.06
  1782.3   50.75    1815   54.96  1898.1   50.66    1923   51.16  1941.8   54.49
  1994.4   54.92  2633.3   50.81  3169.1   50.78  3360.4   56.03  3440.8    61.5
#Mann= 3 ,-1,0
       0     .13       0  867.56    .045       0  1046.8     .13       0
#XS Ineff= 2 , 0
       0     560      56    1400       0    55.5
Permanent Ineff=
       F       F
Bank Sta=854,937.66
XS Rating Curve= 0 ,0
Exp/Cntr(USF)=0,0
Exp/Cntr=0.5,0.3

Type RM Length L Ch R = 1 ,14879   ,508.8,508.8,508.8
XS GIS Cut Line= 6
 2150007.2416423457865.5172508032149490.62526397458218.307312176
2149308.24367563458336.9717891392149205.38958322458403.589498923
2148801.93873789458693.1248114472147209.73758631459867.581049305
#Sta/Elev= 30
       0   71.09   420.4    72.8   466.9   63.14   542.3   56.21  556.06   49.06
   578.1   45.03  621.13   44.97  634.93   47.82   738.4   45.54   850.1   46.64
  861.69   42.66  928.73   42.62  945.89    46.9  1079.3   52.44    1108   45.85
 1129.86   45.86 1155.49   52.57  1183.1   46.22  1323.1   46.04  1392.3   49.58
  1517.9   47.89  1540.3   50.98  1907.5   51.44  1927.9   54.27  1998.8   55.07
  2020.9   52.94  2065.2   55.11  3154.2   50.62  3326.1   54.44  3440.8   60.98
#Mann= 3 ,-1,0
       0     .13       0  928.73    .045       0  945.89     .13       0
#XS Ineff= 2 , 0
       0     560      56    1400       0    55.5
Permanent Ineff=
       F       F
Bank Sta=850.1,945.89
XS Rating Curve= 0 ,0
Exp/Cntr(USF)=0,0
Exp/Cntr=0.5,0.3

Type RM Length L Ch R = 1 ,14371   ,35.3,35.3,35.3
BEGIN DESCRIPTION:
Wire Road at Indian Field - US
END DESCRIPTION:
XS GIS Cut Line= 6
2150333.42248984  457818.40776572149728.21248984  457863.8777657
2148587.55000415458211.3003852132148247.66440599  458189.1377657
 2147994.4660008458132.4137917952146909.49685185459306.712552653
#Sta/Elev= 30
       0   67.73    71.3    68.3    99.9   66.06     114   68.28   167.1   66.73
   373.6   70.22   544.1   68.51   725.8   70.95   752.8   62.08   769.9   63.93
   807.5   59.85   838.2   63.87   936.4    50.7   970.1   49.91    1040  43.698
  1041.9   42.22    1085  43.563 1143.66   44.84 1171.83   45.11  1233.5   48.34
  1563.5    47.3  1688.6   49.52  1739.8   47.43  2303.6   47.44  2553.8   51.23
  3000.9   50.95  3581.9   55.17  3694.1   52.16  3964.3   54.48  4007.2   56.53
#Mann= 3 ,-1,0
       0     .13       0 1143.66    .045       0 1171.83     .13       0
#XS Ineff= 2 , 0
       0   954.9    53.4  1235.1       0   51.02
Permanent Ineff=
       F       F
Bank Sta=1040,1085
XS Rating Curve= 0 ,0
Exp/Cntr=0.5,0.3

Type RM Length L Ch R = 1 ,14335   ,139.4,139.4,139.4
BEGIN DESCRIPTION:
Wire Road at Indian Field - US
END DESCRIPTION:
XS GIS Cut Line= 6
2150329.49883881457784.4027901322149724.28883881457829.872790132
2148583.62635312458177.2954096452148243.74075496458155.132790132
2147990.54234977458098.4088162272146905.57320082459272.707577085
#Sta/Elev= 30
       0   67.73    71.3    68.3    99.9   66.06     114   68.28   167.1   66.73
   373.6   70.22   544.1   68.51   725.8   70.95   752.8   62.08   769.9   63.93
   807.5   59.85   838.2   63.87   936.4    50.7   970.1   49.91    1040  43.698
  1041.9   42.22    1085  43.563 1143.66   44.84 1171.83   45.11  1233.5   48.34
  1563.5    47.3  1688.6   49.52  1739.8   47.43  2303.6   47.44  2553.8   51.23
  3000.9   50.95  3581.9   55.17  3694.1   52.16  3964.3   54.48  4007.2   56.53
#Mann= 3 ,-1,0
       0     .13       0 1143.66    .045       0 1171.83     .13       0
#XS Ineff= 2 , 0
           990.2    53.4  1199.8           51.02
Permanent Ineff=
       F       F
Bank Sta=1040,1085
XS Rating Curve= 0 ,0
Exp/Cntr=0.5,0.3