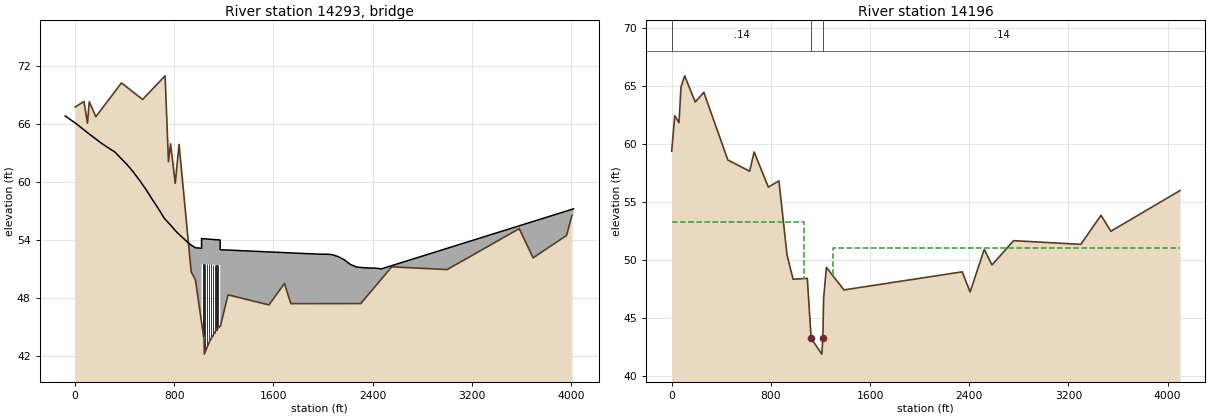
HEC-RAS study IndianFieldsSwamp.prj: S-18-19 over Indian Fields Swamp

--- IndianFieldsSwamp.g07 (geometry) --- (continued)

Type RM Length L Ch R = 3 ,14293   ,,,
BEGIN DESCRIPTION:
S-18-19 (Wire Rd) over Indian Fields  Swamp
END DESCRIPTION:
Bridge Culvert--1,0,-1,-1, 0
Deck Dist Width WeirC Skew NumUp NumDn MinLoCord MaxHiCord MaxSubmerge Is_Ogee
29.79509,27.5,3,0, 40, 40, , , 0.95, 0, 2,2,,
     -80     -30      20      70     120     220     270     320     420     470
     520     570     620     670     720     770     820     870     920     970
 1019.99    1020    1020    1170    1170 1170.01    1870    1920    1970    2020
    2070    2120    2170    2220    2270    2320    2370    2420    2470    4020
   66.81   66.36    65.9   65.38   64.88   63.92    63.5   63.09   61.77   61.01
   60.16   59.24   58.24   57.26   56.23   55.54   54.81   54.21   53.62    53.2
   53.15   54.15   54.15      54      54      53  52.594   52.57   52.54   52.54
    52.5    52.3   51.97   51.48   51.21   51.15   51.11    51.1   51.02   57.22
                                                                                
                                                                                
                   51.55    51.4
                                                                                
       8      58     108     158     208     308     358     408     508     558
     608     658     708     758     808     858     908     958    1008    1058
 1107.99    1108    1108    1258    1258 1258.01    1958    2008    2058    2108
    2158    2208    2258    2308    2358    2408    2458    2508    2558    4108
   66.81   66.36    65.9   65.38   64.88   63.92    63.5   63.09   61.77   61.01
   60.16   59.24   58.24   57.26   56.23   55.54   54.81   54.21   53.62    53.2
   53.15   54.15   54.15      54      54      53  52.594   52.57   52.54   52.54
    52.5    52.3   51.97   51.48   51.21   51.15   51.11    51.1   51.02   57.22
                                                                                
                                                                                
                   51.55    51.4
                                                                                
Pier Skew, UpSta & Num, DnSta & Num=  ,1035, 2 ,1123, 2 , 0 , 0 , 0 ,,
     1.5     1.5
   41.87      52
     1.5     1.5
   41.87      52
Pier Skew, UpSta & Num, DnSta & Num=  ,1050, 2 ,1138, 2 , 0 , 0 , 0 ,,
     1.5     1.5
   41.87      52
     1.5     1.5
   41.87      52
Pier Skew, UpSta & Num, DnSta & Num=  ,1065, 2 ,1153, 2 , 0 , 0 , 0 ,,
     1.5     1.5
   41.87      52
     1.5     1.5
   41.87      52
Pier Skew, UpSta & Num, DnSta & Num=  ,1080, 2 ,1168, 2 , 0 , 0 , 0 ,,
     1.5     1.5
   41.87      52
     1.5     1.5
   41.87      52
Pier Skew, UpSta & Num, DnSta & Num=  ,1095, 2 ,1183, 2 , 0 , 0 , 0 ,,
     1.5     1.5
   41.87      52
     1.5     1.5
   41.87      52
Pier Skew, UpSta & Num, DnSta & Num=  ,1110, 2 ,1198, 2 , 0 , 0 , 0 ,,
     1.5     1.5
   41.87      52
     1.5     1.5
   41.87      52
Pier Skew, UpSta & Num, DnSta & Num=  ,1125, 2 ,1213, 2 , 0 , 0 , 0 ,,
     1.5     1.5
   41.87      52
     1.5     1.5
   41.87      52
Pier Skew, UpSta & Num, DnSta & Num=  ,1140, 2 ,1228, 2 , 0 , 0 , 0 ,,
     1.5     1.5
   41.87      52
     1.5     1.5
   41.87      52
Pier Skew, UpSta & Num, DnSta & Num=  ,1155, 2 ,1243, 2 , 0 , 0 , 0 ,,
     1.5     1.5
   41.87      52
     1.5     1.5
   41.87      52
Abutment Skew #Up #Dn= , 3 , 3
 1019.99    1022  1034.3
    49.4    49.4   43.25
 1107.99    1110  1122.3
    49.4    49.4   43.25
Abutment Skew #Up #Dn= , 3 , 3
    1158    1168 1170.01
      45      50      50
    1246    1256 1258.01
      45      50      50
BR Coef=-1 ,-1 ,-1 ,1.25, 0 ,,,0.8,0,2,0,
WSPro=,,,, 1 ,,,, 0 ,,,, 0 ,,,,-1 ,-1 ,-1 , 0 , 0 , 0 , 0 , 0
BC Design=,, 0 ,, 0 ,,,,,,
BC HTab HWMax=71.5
BC Use User HTab Curves=0
BC User HTab FreeFlow(D)= 0

Type RM Length L Ch R = 1 ,14196   ,572.1,572.1,572.1
BEGIN DESCRIPTION:
Wire Road at Indian Field - DS
END DESCRIPTION:
XS GIS Cut Line= 6
2150323.70635095457663.0944824492149589.22826132457723.219142731
2148557.91016933458039.7280789072148319.53207461458038.226249793
2147928.73818492457969.4063180592146859.36653229459215.052239341
#Sta/Elev= 30
       0   59.37      25   62.44      59   61.84    75.3   64.92   104.9   65.88
     190   63.62   259.3   64.46   453.1   58.62   628.7   57.65   665.4   59.31
   779.9   56.28     865   56.82   930.8   50.42   979.3   48.33  1094.2   48.41
    1125  43.235    1211   41.87 1219.69   43.27  1225.5   46.66  1248.1   49.36
  1389.4   47.41  2343.6   48.97  2407.3   47.23  2521.4   50.91  2583.8   49.56
  2758.3   51.66  3300.5   51.34  3463.4   53.85  3542.6   52.47  4100.4   55.98
#Mann= 3 ,-1,0
       0     .14       0    1125    .045       0 1219.69     .14       0
#XS Ineff= 2 , 0
            1067   53.25    1299           51.02
Permanent Ineff=
       F       F
Bank Sta=1125,1219.69
XS Rating Curve= 0 ,0
Exp/Cntr=0.5,0.3