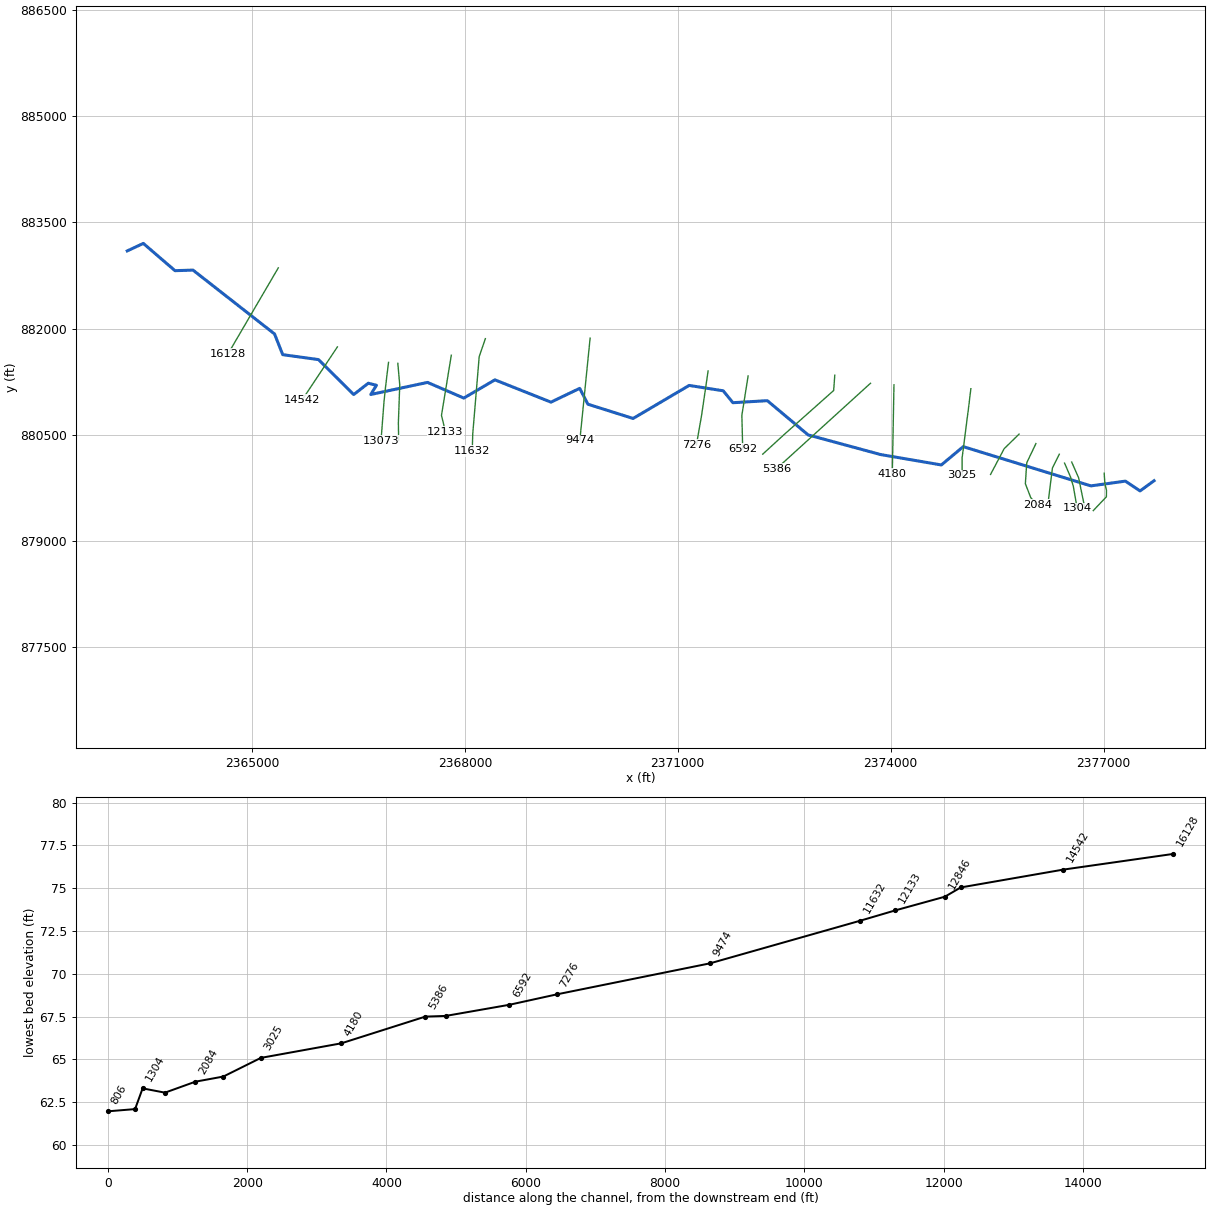
--- HighHillCreek.prj (project) ---

Proj Title=S-21-356 over High Hill Creek
Current Plan=p09
Default Exp/Contr=0.3,0.1
English Units
Geom File=g01
Geom File=g02
Geom File=g03
Geom File=g04
Geom File=g05
Geom File=g06
Geom File=g07
Flow File=f01
Flow File=f02
Flow File=f03
Flow File=f05
Plan File=p01
Plan File=p02
Plan File=p03
Plan File=p05
Plan File=p06
Plan File=p07
Plan File=p08
Plan File=p09
Y Axis Title=Elevation
X Axis Title(PF)=Main Channel Distance
X Axis Title(XS)=Station
BEGIN DESCRIPTION:
END DESCRIPTION:
DSS File=dss
DSS Export Rating Curves= 0
DSS Export Rating Curve Sorted= 0
DSS Export Volume Flow Curves= 0
DXF OffsetX= 0
DXF OffsetY= 0
DXF ScaleX= 1
DXF ScaleY= 10

--- HighHillCreek.p09 (plan) ---

Plan Title=Revised Conditions - FEMA
Program Version=6.60
Short Identifier=RC
Geom File=g06
Flow File=f01
Subcritical Flow
K Sum by GR= 0
Std Step Tol= 0.01
Critical Tol= 0.01
Num of Std Step Trials= 20
Max Error Tol= 0.3
Flow Tol Ratio= 0.001
Split Flow NTrial= 30
Split Flow Tol= 0.02
Split Flow Ratio= 0.02
Log Output Level= 0
Friction Slope Method= 1
Unsteady Friction Slope Method= 2
Unsteady Bridges Friction Slope Method= 1
Parabolic Critical Depth
Global Vel Dist= 0 , 0 , 0
Global Log Level= 0
CheckData=True
Encroach Param=-1 ,0,0, 0
Flow Ratio Tolerance=0.1
Flow Ratio Min Ratio=0.5
Flow Ratio Max Ratio=4
Flow Ratio Max Iterations= 10
Computation Interval=1MIN
Output Interval=1HOUR
Instantaneous Interval=1HOUR
Mapping Interval=1HOUR
Computation Time Step Use Courant=        0
Computation Time Step Use Time Series=    0
Computation Time Step Count To Double=0
Computation Time Step Max Doubling=0
Computation Time Step Max Halving=0
Computation Time Step Residence Courant=0
Run HTab= 0
Run UNet= 0
Run Sediment= 0
Run PostProcess= 0
Run WQNet= 0
Run RASMapper= 0
UNET Theta= 1
UNET Theta Warmup= 1
UNET ZTol= 0.02
UNET ZSATol= 0.02
UNET MxIter= 20
UNET Max Iter WO Improvement= 0
UNET MaxInSteps= 0
UNET DtIC= 0
UNET DtMin= 0
UNET MaxCRTS= 20
UNET WFStab= 2
UNET SFStab= 1
UNET WFX= 1
UNET SFX= 1
UNET Gravity=32.17405
UNET 1D Methodology=Finite Difference
UNET DSS MLevel= 4
UNET Pardiso=0
UNET DZMax Abort= 100
UNET Use Existing IB Tables=-1
UNET Froude Reduction=False
UNET Froude Limit= 0.8
UNET Froude Power= 4
UNET D1 Cores= 0
UNET WindReference=Eulerian
UNET WindDragFormulation=Hsu (1988)
UNET D2 Coriolis=0
UNET D2 Cores= 0
UNET D2 Theta= 1
UNET D2 Theta Warmup= 1
UNET D2 Z Tol= 0.01
UNET D2 Volume Tol= 0.01
UNET D2 Max Iterations= 20
UNET D2 Advanced Convergence=0
UNET D2 WS Max Tol=0.15
UNET D2 WS RMS Tol=0.002
UNET D2 WS Stall Tol=1
UNET D2 Equation= 0
UNET D2 RampUpFraction=0.1
UNET D2 TimeSlices= 1
UNET D2 Turbulence Formulation=None
UNET D2 Eddy Viscosity=0.3
UNET D2 Transverse Eddy Viscosity=0.1
UNET D2 Smagorinsky Mixing=0.05
UNET D2 BCVolumeCheck=0
UNET D2 Cores=0
UNET D2 SolverType=PARDISO (Direct)
UNET D2 Minimum Iterations= 3
UNET D2 Maximum Iterations= 30
UNET D2 Restart Number= 10
UNET D2 Relaxation Coeff=1.3
UNET D2 SOR Precondition Iterations= 10
UNET D2 ILUT Maximum Fill= 8
UNET D2 ILUT Tolerance=1E-08
UNET D2 Convergence Tolerance=0.00001
PS Theta= 1
PS WS Tol= 0.01
PS Volume Tol= 0.01
PS Max Iterations= 20
PS Equation= 0
PS Advance Time Step=-1
PS Target Courant=0.9
PS Time Slices= 1
PS Iterate With 2D=0
PS Project Initial WSE from DS=-1
PS Ramp Up Initial WSE from US=-1
PS Cores=0
UNET D1D2 MaxIter= 0
UNET D1D2 ZTol=0.01
UNET D1D2 QTol=0.1
UNET D1D2 MinQTol=1
Write IC File= 0
Write IC File at Fixed DateTime=0
Write IC File at Sim End=0
Echo Input=False
Echo Parameters=False
Echo Output=False
Write Detailed= 0
HDF Write Warmup=0
HDF Write Time Slices=0
HDF Flush=0
HDF Compression= 1
HDF Chunk Size= 1
HDF Spatial Parts= 1
HDF Use Max Rows=0
HDF Fixed Rows= 1
Calibration Method= 0
Calibration Iterations= 20
Calibration Max Change=0.05
Calibration Tolerance=0.2
Calibration Maximum=1.5
Calibration Minimum=0.5
Calibration Optimization Method= 1
WQ AD Non Conservative
WQ ULTIMATE=-1
WQ Max Comp Step=1HOUR
WQ Output Interval=15MIN
WQ Output Selected Increments= 0
WQ Create Restart=0
WQ Fixed Restart=0
WQ System Summary=0
WQ Write To DSS=0
Sorting and Armoring Iterations= 10
XS Update Threshold= 0.02
Bed Roughness Predictor= 0
Processes Affected by Predictor=Sediment Only
Hydraulics Update Threshold= 0.02
Energy Slope Method= 1
Volume Change Method= 1
Sediment Retention Method= 0
Sediment TS Multiplier= 1
Warm Up Method= 0
XS Weighting Method= 0
Number of US Weighted Cross Sections= 1
Number of DS Weighted Cross Sections= 1
Upstream XS Weight=0
Main XS Weight=1
Downstream XS Weight=0
Number of DS XS's Weighted with US Boundary= 1
Upstream Boundary Weight= 1
Weight of XSs Associated with US Boundary= 0
Number of US XS's Weighted with DS Boundary= 1
Downstream Boundary Weight= 0.5
Weight of XSs Associated with DS Boundary= 0.5
Percentile Method= 0
Sediment Output Level= 3
Mass or Volume Output= 0
Output Increment Type= 1
Profile and TS Output Increment= 1
Transport Output Increment 1
XS Output Flag= 0
XS Output Increment= 10
Read HDF5 Sediment Hotstart= 0
Sediment Hotstart Type= 0
Write Gradation File= 0
Read Gradation Hotstart= 0
Write HDF5 File= 1
Write Binary Output= 1
Write DSS Sediment File= 0
DSS Sediment Output Type= 1
SV Curve= 0
Specific Gage Flag= 0
Subcell Erosion Methods= 0
Subcell Deposition Methods= 0
Advection Scheme= 1
Matrix Solver= 0
Implicit Weighting Factor= 1
Maximum Outer Loop Convergence Iterations= 5
Convergence Maximum Absolute= 0.001
Convergence RMSE= 0.0001
Grain Fractions Max Abs Error= 0.001
Max Subgrid Regions= 1
Max Subgrid Length Scale= 3.402823E+38
Initial Layer Thickness= 3
Min Layer Thickness= 0.1
Max Layer Thickness= 6
Number of Layers= 5

--- HighHillCreek.p01 (plan) ---

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Plan Title=Corrected Effective - FEMA
Short Identifier=CE
Geom File=g01
Flow File=f01

--- HighHillCreek.p02 (plan) ---

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Plan Title=Corrected Effective Floodway - FEMA
Short Identifier=CE_FW
Geom File=g01
Flow File=f02
Encroach Param=-1 ,0,0, 2
Encroach River=High Hill Creek
Encroach Reach=Reach 1
Encroach Node=16128
       1   506.8 1072.75
Encroach Node=14542
       1   252.8   600.5
Encroach Node=13073
       1   286.5     575
Encroach Node=12846
       1   286.4     584
Encroach Node=12133
       1     370   817.2
Encroach Node=11632
       1   598.5  1106.9
Encroach Node=9474
       1     680  1163.6
Encroach Node=7276
       1   202.2     629
Encroach Node=6592
       1     220   654.5
Encroach Node=5680
       1   628.1  1246.6
Encroach Node=5386
       1   636.8  1262.3
Encroach Node=4180
       1     545  1084.5
Encroach Node=3025
       1   505.5     957
Encroach Node=2486
       1   217.5   582.5
Encroach Node=2084
       1   183.8   467.5
Encroach Node=1625
       1     176   415.2
Encroach Node=1304
       1   205.6   300.4
Encroach Node=1196
       1     252   325.5
Encroach Node=806
       1   164.8   335.8

--- HighHillCreek.p03 (plan) ---

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Plan Title=Existing - SCDOT
Short Identifier=EX
Geom File=g02
Flow File=f03
Encroach Param=-1 ,0,0, 2

--- HighHillCreek.p05 (plan) ---

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Plan Title=Sensitivity Analysis - SCDOT
Short Identifier=Sensitivity
Geom File=g02
Flow File=f05
Encroach Param=-1 ,0,0, 2

--- HighHillCreek.p06 (plan) ---

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Plan Title=Natural - SCDOT
Short Identifier=Natural
Geom File=g04
Flow File=f03
Encroach Param=-1 ,0,0, 2

--- HighHillCreek.p07 (plan) ---

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Plan Title=Proposed - SCDOT
Short Identifier=PROP
Geom File=g05
Flow File=f03
Encroach Param=-1 ,0,0, 2

--- HighHillCreek.p08 (plan) ---

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Plan Title=Revised Conditions Floodway - FEMA
Short Identifier=RC_FW
Geom File=g06
Flow File=f02
Encroach Param=-1 ,0,0, 2
Encroach River=High Hill Creek
Encroach Reach=Reach 1
Encroach Node=16128
       1   506.8 1072.75
Encroach Node=14542
       1   252.8   600.5
Encroach Node=13073
       1   286.5     575
Encroach Node=12846
       1   286.4     584
Encroach Node=12133
       1     370   817.2
Encroach Node=11632
       1   598.5  1106.9
Encroach Node=9474
       1     680  1163.6
Encroach Node=7276
       1   202.2     629
Encroach Node=6592
       1     220   654.5
Encroach Node=5680
       1   628.1  1246.6
Encroach Node=5386
       1   636.8  1262.3
Encroach Node=4180
       1     545  1084.5
Encroach Node=3025
       1   505.5     957
Encroach Node=2486
       1   217.5   582.5
Encroach Node=2084
       1   183.8   467.5
Encroach Node=1625
       1     176   415.2
Encroach Node=1304
       1   205.6   300.4
Encroach Node=1196
       1     252   325.5
Encroach Node=806
       1   164.8   335.8

--- HighHillCreek.f01 (steady flow) ---

Flow Title=FEMA Flows
Program Version=6.60
Number of Profiles= 4
Profile Names=10-yr,50-yr,100-yr,500-yr
River Rch & RM=High Hill Creek,Reach 1         ,16128
    1850    3175    4000    6300
River Rch & RM=High Hill Creek,Reach 1         ,2084
    2050    3500    4400    6900
Boundary for River Rch & Prof#=High Hill Creek,Reach 1         , 1
Up Type= 0
Dn Type= 3
Dn Slope=0.001
Boundary for River Rch & Prof#=High Hill Creek,Reach 1         , 2
Up Type= 0
Dn Type= 3
Dn Slope=0.001
Boundary for River Rch & Prof#=High Hill Creek,Reach 1         , 3
Up Type= 0
Dn Type= 3
Dn Slope=0.001
Boundary for River Rch & Prof#=High Hill Creek,Reach 1         , 4
Up Type= 0
Dn Type= 3
Dn Slope=0.001
DSS Import GetInterval= 0
DSS Import GetPeak= 0
DSS Import FillOption= 0

--- HighHillCreek.f02 (steady flow) ---

Flow Title=Floodway
Program Version=6.60
Number of Profiles= 2
Profile Names=100-yr,100-yr FW
River Rch & RM=High Hill Creek,Reach 1         ,16128
    4000    4000
River Rch & RM=High Hill Creek,Reach 1         ,2084
    4400    4400
Boundary for River Rch & Prof#=High Hill Creek,Reach 1         , 1
Up Type= 0
Dn Type= 3
Dn Slope=0.001
Boundary for River Rch & Prof#=High Hill Creek,Reach 1         , 2
Up Type= 0
Dn Type= 3
Dn Slope=0.001
DSS Import GetInterval= 0
DSS Import GetPeak= 0
DSS Import FillOption= 0

--- HighHillCreek.f03 (steady flow) ---

Flow Title=WeightedQ
Program Version=6.60
Number of Profiles= 6
Profile Names=2-yr,10-yr,25-yr,50-yr,100-yr,500-yr
River Rch & RM=High Hill Creek,Reach 1         ,48415
     643    1710    2400    3040    3680    5290
River Rch & RM=High Hill Creek,Reach 1         ,34371
     754    1990    2800    3530    4270    6120
River Rch & RM=High Hill Creek,Reach 1         ,32284
    2171    5579    7898    9906   12046   17629
Boundary for River Rch & Prof#=High Hill Creek,Reach 1         , 1
Up Type= 0
Dn Type= 3
Dn Slope=0.001
Boundary for River Rch & Prof#=High Hill Creek,Reach 1         , 2
Up Type= 0
Dn Type= 3
Dn Slope=0.001
Boundary for River Rch & Prof#=High Hill Creek,Reach 1         , 3
Up Type= 0
Dn Type= 3
Dn Slope=0.001
Boundary for River Rch & Prof#=High Hill Creek,Reach 1         , 4
Up Type= 0
Dn Type= 3
Dn Slope=0.001
Boundary for River Rch & Prof#=High Hill Creek,Reach 1         , 5
Up Type= 0
Dn Type= 3
Dn Slope=0.001
Boundary for River Rch & Prof#=High Hill Creek,Reach 1         , 6
Up Type= 0
Dn Type= 3
Dn Slope=0.001
DSS Import GetInterval= 0
DSS Import GetPeak= 0
DSS Import FillOption= 0

--- HighHillCreek.f05 (steady flow) ---

Flow Title=Sensitivity
Program Version=6.60
Number of Profiles= 3
Profile Names=100yr - 3ft,100yr,100yr + 3ft
River Rch & RM=High Hill Creek,Reach 1         ,48415
    3680    3680    3680
River Rch & RM=High Hill Creek,Reach 1         ,34371
    4270    4270    4270
River Rch & RM=High Hill Creek,Reach 1         ,32284
   12046   12046   12046
Boundary for River Rch & Prof#=High Hill Creek,Reach 1         , 1
Up Type= 0
Dn Type= 1
Dn Known WS=63.76
Boundary for River Rch & Prof#=High Hill Creek,Reach 1         , 2
Up Type= 0
Dn Type= 1
Dn Known WS=66.76
Boundary for River Rch & Prof#=High Hill Creek,Reach 1         , 3
Up Type= 0
Dn Type= 1
Dn Known WS=69.76
DSS Import GetInterval= 0
DSS Import GetPeak= 0
DSS Import FillOption= 0

--- HighHillCreek.g06 (geometry) ---

Geom Title=Revised Conditions - FEMA
Program Version=6.60

River Reach=High Hill Creek ,Reach 1
Reach XY= 30
2363243.59977666883095.1585389252363470.10273459883200.979624876
     2363916.541     882816.2089     2364169.825     882824.5284
2365318.91790818881923.4632630332365434.07356473881631.331335304
2365938.12192123881561.7803600872366434.63516231 881068.63046019
2366639.57739412881228.4486882212366754.57299165881199.380348398
 2366675.0810412881069.5994706042367474.41349412881239.832417638
2367985.37632941881019.0347882392368423.81331766881275.887817588
2369213.48965868880961.4292568692369618.44172039881155.965495848
     2369733.853     880932.35422370371.18916704880731.220620871
     2371160.465     881197.2497     2371640.446      881121.605
     2371777.203     880953.6182     2372262.513     880982.1788
2372836.82505122880499.400195291     2373858.439     880222.0221
 2374714.1616769 880075.309496362375022.87405973880333.523637647
2376821.32108408879779.9052694932377306.83948176 879847.03482287
2377514.09763044879708.7602519652377711.40880004879853.044300603

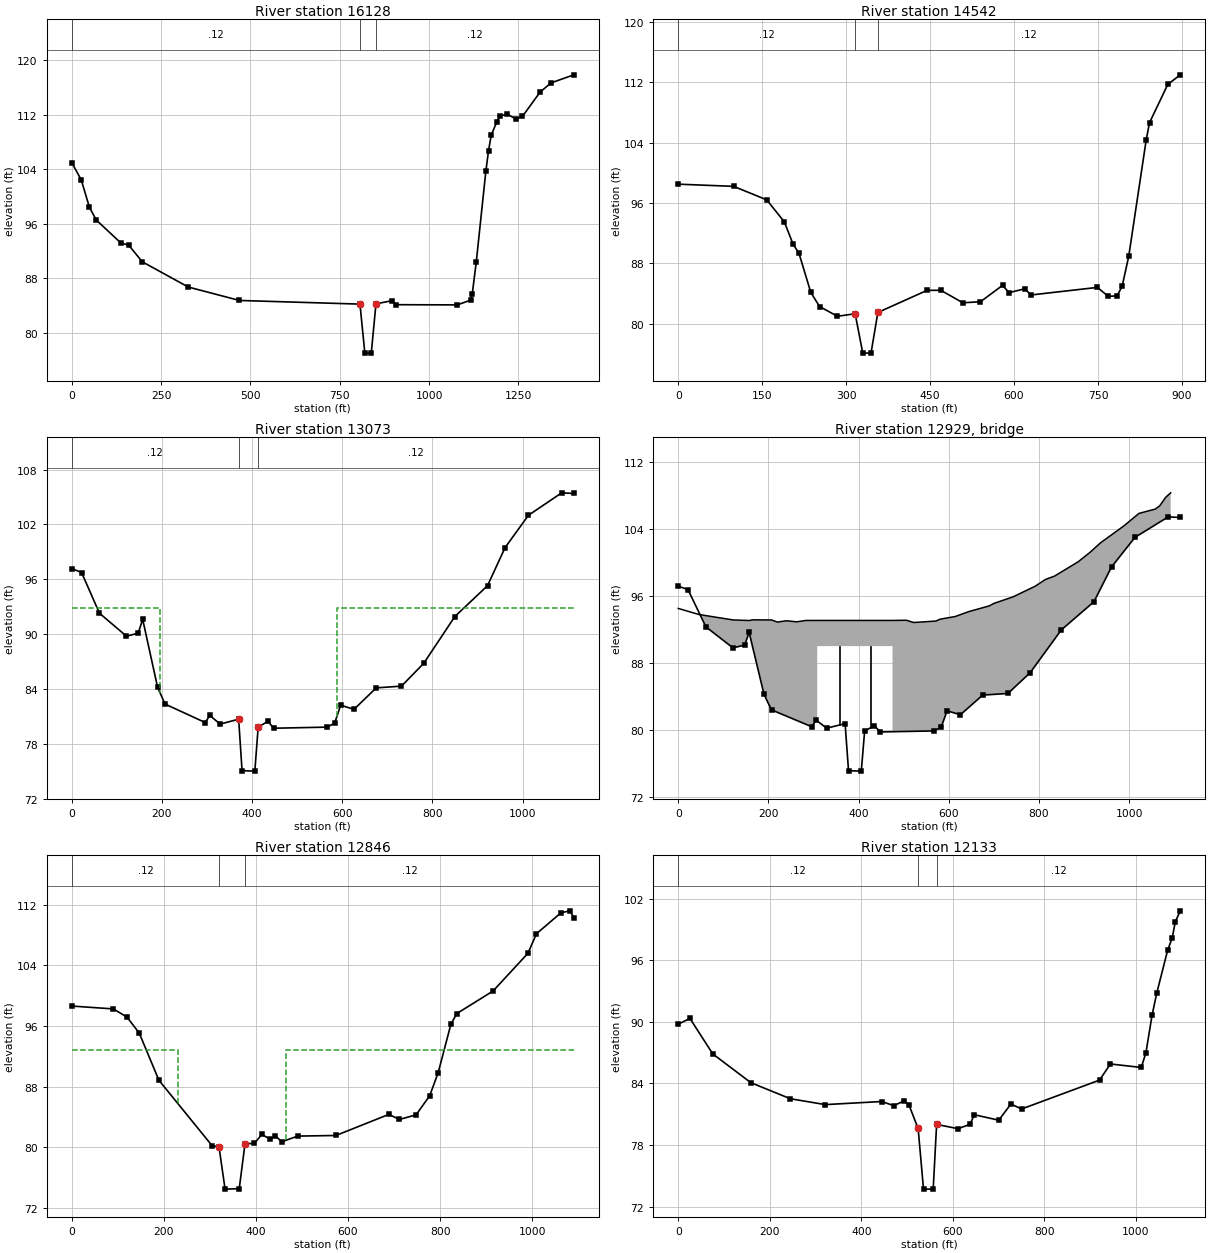
Type RM Length L Ch R = 1 ,16128   ,1585.7,1585.7,1585.7
XS GIS Cut Line= 2
  2365371.411892882855.6956462862364662.86671036 881642.17983147
#Sta/Elev= 30
       0  104.97   26.57  102.42   49.36   98.42   68.36   96.55  136.75    93.2
  159.55   92.83  197.54    90.4   326.2    86.7  469.36   84.73   806.6  84.195
  820.25      77  838.26      77   851.4  84.236  896.65    84.7  908.05   84.11
 1079.02   84.08 1117.02   84.79 1120.82   85.66 1132.21   90.43 1158.93   103.7
 1166.41   106.7 1174.01     109 1189.21   110.9 1197.31  111.74  1217.7  112.11
  1242.4  111.39  1261.4  111.75 1310.79  115.32 1341.19  116.66 1405.22  117.85
#Mann= 3 ,0,0
       0     .12       0   806.6     .05       0   851.4     .12       0
Bank Sta=806.6,851.4
XS Rating Curve= 0 ,0
Exp/Cntr(USF)=0,0
Exp/Cntr=0.3,0.1

Type RM Length L Ch R = 1 ,14542   ,1469.3,1469.3,1469.3
XS GIS Cut Line= 2
2366204.20714159881740.5968944942365708.08189925880993.145049117
#Sta/Elev= 30
       0    98.5   99.01   98.21  158.08   96.42  189.58    93.5  205.34   90.51
  215.59   89.37  236.84   84.14  252.59   82.26  284.44   80.97   316.1  81.304
  329.72   76.09  344.47   76.08   356.7  81.476  444.64   84.41  469.19   84.42
  508.57   82.76  540.08    82.9  579.46   85.07  591.27   84.11  618.84   84.61
  630.65    83.8   748.8    84.8  768.49   83.61  784.24   83.69  793.15   84.95
  804.98   88.94  836.22   104.4  842.16  106.67  874.82  111.75  897.12  113.01
#Mann= 3 ,0,0
       0     .12       0   316.1     .05       0   356.7     .12       0
Bank Sta=316.1,356.7
XS Rating Curve= 0 ,0
Exp/Cntr(USF)=0,0
Exp/Cntr=0.5,0.3

Type RM Length L Ch R = 1 ,13073   ,227.2,227.2,227.2
XS GIS Cut Line= 4
 2366924.9056944881522.1839907562366884.43137281881190.680023462
2366861.30318904 880969.034929052366818.90151881880413.958518697
#Sta/Elev= 30
       0   97.18   21.73   96.75    61.4    92.3  121.27   89.79  147.34   90.12
  157.26   91.63  190.31   84.21  206.84   82.37  296.09   80.35     306   81.13
  329.14   80.18   370.1  80.719  377.67   75.09  405.99   75.04   413.4   79.85
  434.92   80.48  447.91   79.73  566.65   79.85   583.1   80.29  596.27   82.25
  625.88   81.79  675.24   84.14  731.18   84.33  780.55   86.82  849.65   91.94
  922.04   95.31  960.96   99.47 1012.93  103.01 1086.58  105.46 1113.51  105.39
#Mann= 3 ,0,0
       0     .12       0   370.1     .05       0   413.4     .12       0
#XS Ineff= 2 , 0
       0  195.75   92.88  587.75       0   92.82
Permanent Ineff=
       F       F
Bank Sta=370.1,413.4
XS Rating Curve= 0 ,0
Exp/Cntr(USF)=0,0
Exp/Cntr=0.5,0.3

Type RM Length L Ch R = 3 ,12929   ,,,
Bridge Culvert--1,0,-1,-1, 0
Deck Dist Width WeirC Skew NumUp NumDn MinLoCord MaxHiCord MaxSubmerge Is_Ogee
112.5,46.5,2.6,0, 35, 32, , , 0.98, 0, 2,2,,
       0  45.978 121.546 157.687 164.258  206.97 220.113 239.826 262.695 282.532
  308.24  308.25  475.25  475.26 505.742  522.19 571.534 581.025 614.266 643.847
 689.806 699.653 742.362 791.735 814.533 834.493 887.096 913.378 936.375 988.939
1021.7921057.9291067.7851080.9261092.095
  94.506  93.781  93.131   93.06  93.144  93.128  92.875  93.031  92.904  93.068
   93.07   93.07   93.07   93.07  93.095  92.822  92.998  93.222   93.54  94.119
  94.813  95.101  95.888  97.169  97.979  98.375 100.093 101.224 102.352 104.408
 105.878 106.394 106.782 107.793  108.34
                                                                                
              90      90
                                                                                
                                        
       0  45.978 121.546 157.687 164.258  206.97 220.113  264.54  264.55  431.55
  431.56 505.742  522.19 571.534 581.025 614.266 643.847 689.806 699.653 742.362
 791.735 814.533 834.493 887.096 913.378 936.375 988.9391021.7921057.9291067.785
1080.9261092.095
  94.506  93.781  93.131   93.06  93.144  93.128  92.875   93.07   93.07   93.07
   93.07  93.095  92.822  92.998  93.222   93.54  94.119  94.813  95.101  95.888
  97.169  97.979  98.375 100.093 101.224 102.352 104.408 105.878 106.394 106.782
 107.793  108.34
                                                                      90      90
                                                                                
                                                                                
                
Pier Skew, UpSta & Num, DnSta & Num=  ,357.25, 2 ,313.55, 2 , 0 , 0 , 0 ,,
       3       3
       0      91
       3       3
       0      91
Pier Skew, UpSta & Num, DnSta & Num=  ,426.25, 2 ,382.55, 2 , 0 , 0 , 0 ,,
       3       3
       0      91
       3       3
       0      91
Abutment Skew #Up #Dn= , 2 , 2
  308.25  328.25
      89      69
  264.55  284.55
      89      69
Abutment Skew #Up #Dn= , 2 , 2
  455.25  475.25
      69      89
  411.55  431.55
      69      89
BR Coef=-1 , 0 , 0 ,, 0 ,,,0.8,0,,0,
WSPro=,,,, 1 ,,,, 0 ,,,, 0 ,,,,-1 ,-1 ,-1 , 0 , 0 , 0 , 0 , 0
BC Design=,, 0 ,, 0 ,,,,,,
BC Use User HTab Curves=0
BC User HTab FreeFlow(D)= 0

Type RM Length L Ch R = 1 ,12846   ,713,713,713
XS GIS Cut Line= 4
 2367055.9654024881508.6925502272367082.94828345881204.171463991
2367063.67479698880670.2958887562367067.52949428880419.740564638
#Sta/Elev= 30
       0   98.63   90.46   98.25  120.11   97.16  146.46   95.08  189.28   88.85
  304.57   80.24   319.8  80.066  332.97    74.5  363.73   74.56   376.3  80.485
   396.5   80.53  412.92   81.71  431.38   81.06  442.47   81.55   455.6   80.73
  490.81   81.49   573.8   81.57  688.72   84.35   711.7   83.68  747.81   84.29
  777.36    86.8  795.85   89.85  823.33    96.2  836.22   97.64  915.22  100.62
   990.7  105.58 1009.33  108.16 1062.89  110.94 1082.58  111.18 1090.52  110.23
#Mann= 3 ,0,0
       0     .12       0   319.8     .05       0   376.3     .12       0
#XS Ineff= 2 , 0
       0  230.45   92.88  465.65       0   92.82
Permanent Ineff=
       F       F
Bank Sta=319.8,376.3
XS Rating Curve= 0 ,0
Exp/Cntr(USF)=0,0
Exp/Cntr=0.5,0.3

Type RM Length L Ch R = 1 ,12133   ,501.1,501.1,501.1
XS GIS Cut Line= 3
 2367809.5587234 881624.333469052367670.78962081880774.372715697
2367726.68273157880545.018226697
#Sta/Elev= 30
       0   89.78   25.62   90.34   75.49   86.88   158.6   84.08  245.04   82.51
  321.51   81.94  444.52   82.24  471.11   81.84  494.39   82.32  504.36   81.89
   524.3  79.611  536.02    73.7  557.22    73.7   564.7  80.012  611.36   79.59
  637.34   80.01  647.32   80.95  700.51   80.42  727.11      82  750.38   81.51
  920.86   84.33   944.5    85.9 1012.04   85.56 1022.17   87.01 1035.68   90.69
 1045.81   92.81 1069.45   96.97 1079.59   98.19 1086.34   99.77 1097.28  100.83
#Mann= 3 ,0,0
       0     .12       0   524.3     .05       0   564.7     .12       0
Bank Sta=524.3,564.7
XS Rating Curve= 0 ,0
Exp/Cntr(USF)=0,0
Exp/Cntr=0.3,0.1

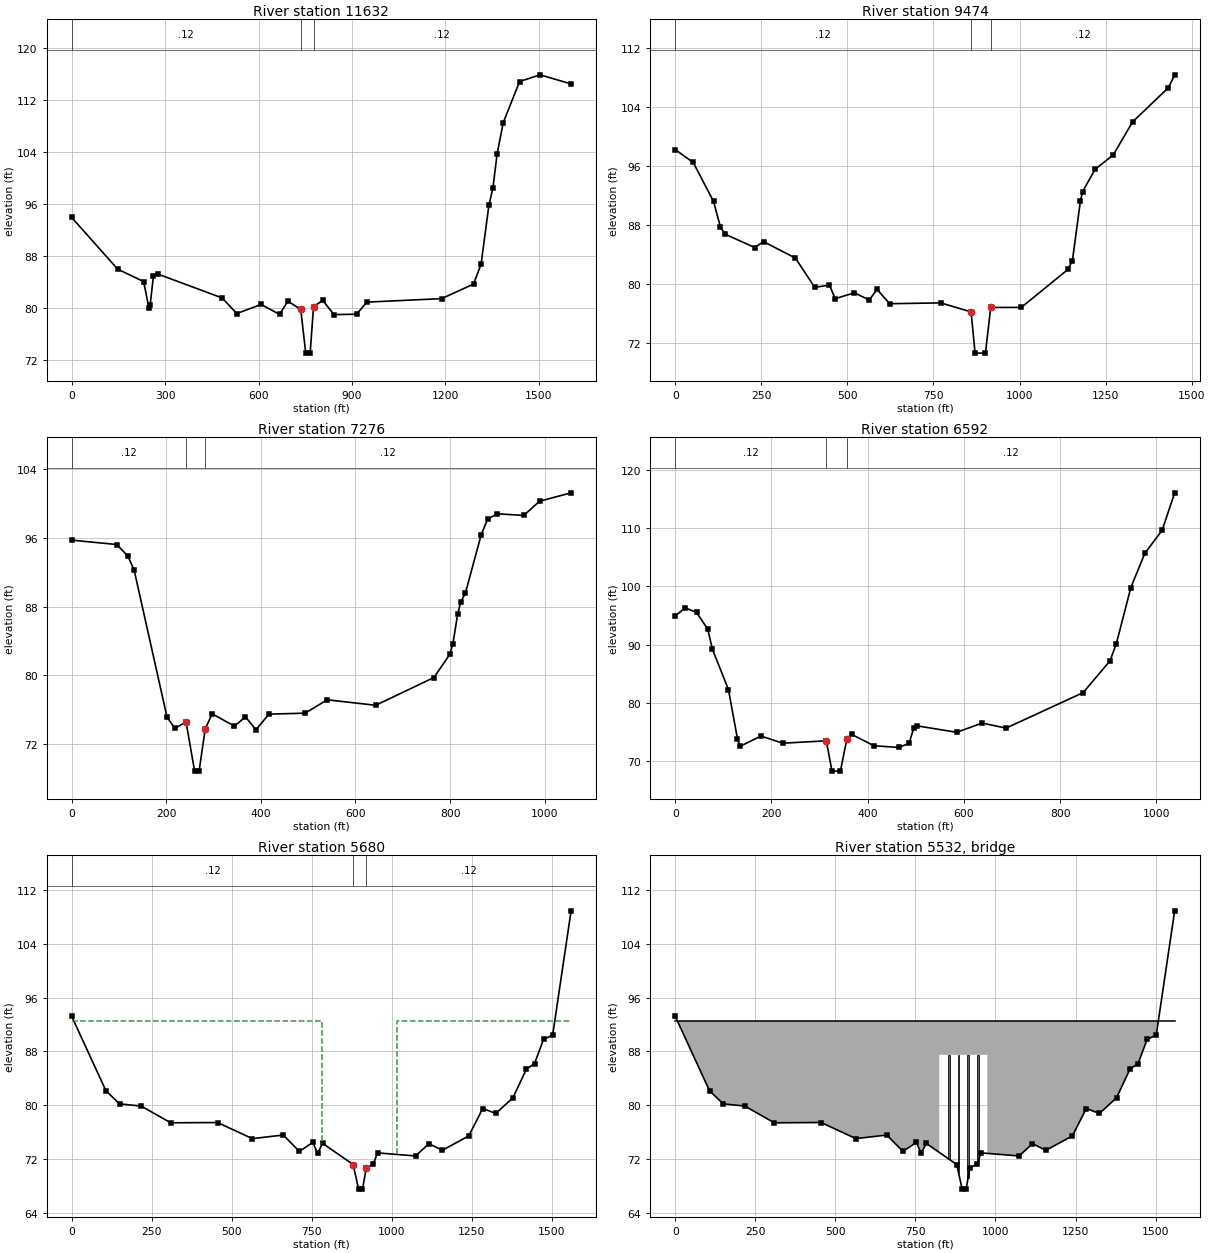
Type RM Length L Ch R = 1 ,11632   ,2157.9,2157.9,2157.9
XS GIS Cut Line= 4
2368289.25326603881857.0929439242368202.21374983881603.227688338
2368111.54758712880515.233735824 2368104.2942941880272.248419762
#Sta/Elev= 30
       0   93.99  147.92   86.02  231.17   84.12   248.1   80.03  251.98   80.44
  262.38    84.9  275.86   85.29  483.29   81.59  530.21    79.2   608.4   80.59
  667.67   79.06  694.01   81.11   735.4  79.824  751.46    73.1   765.6    73.1
   776.5  80.252  805.95   81.22  842.17   79.03   914.6   79.09  947.53   80.95
 1187.88   81.49 1290.02   83.73 1314.34   86.81 1339.34   95.84 1352.51   98.59
 1365.66  103.75 1385.36  108.57 1437.88  114.91 1503.53  115.94 1603.23  114.54
#Mann= 3 ,0,0
       0     .12       0   735.4     .05       0   776.5     .12       0
Bank Sta=735.4,776.5
XS Rating Curve= 0 ,0
Exp/Cntr(USF)=0,0
Exp/Cntr=0.3,0.1

Type RM Length L Ch R = 1 ,9474    ,2198.1,2198.1,2198.1
XS GIS Cut Line= 2
2369765.29839494881864.3462369412369620.23253461880420.940926606
#Sta/Elev= 30
       0    98.2   52.29   96.46  111.23   91.18  131.43   87.69  144.62   86.75
  230.36   84.93  256.74   85.72  349.08    83.5  405.14   79.53  448.01   79.83
  464.49   77.99  520.55   78.79  563.42   77.82  586.51   79.24  622.78   77.31
  771.18   77.42   859.3    76.2  870.98   70.61  901.03   70.61   916.4    76.8
 1005.31   76.81 1140.51   81.95 1153.71   83.15 1176.79   91.21 1183.38   92.52
 1219.66   95.53 1272.42   97.49 1328.48  101.96 1432.69  106.61 1450.68  108.34
#Mann= 3 ,0,0
       0     .12       0   859.3     .05       0   916.4     .12       0
Bank Sta=859.3,916.4
XS Rating Curve= 0 ,0
Exp/Cntr(USF)=0,0
Exp/Cntr=0.3,0.1

Type RM Length L Ch R = 1 ,7276    ,683.4,683.4,683.4
XS GIS Cut Line= 3
2371427.57182206881401.5498760072371336.50672823880778.782137588
2371263.06713644880358.707672522
#Sta/Elev= 30
       0   95.74   95.53   95.23  118.74   93.88     132   92.28  201.68   75.09
  218.22    73.8   241.9  74.526  259.96    68.8  269.43    68.8   282.4  73.736
  297.08   75.48  344.23   74.05  367.44   75.13  389.66   73.63  417.18   75.45
   493.8   75.56  540.09   77.12  642.73   76.48  765.97   79.72  799.28   82.41
  805.95   83.63  815.94   87.09   822.6   88.53  832.59    89.6   865.9   96.39
  879.23   98.16  899.21   98.82  955.84   98.62  989.14  100.28 1055.84  101.26
#Mann= 3 ,0,0
       0     .12       0   241.9     .05       0   282.4     .12       0
Bank Sta=241.9,282.4
XS Rating Curve= 0 ,0
Exp/Cntr(USF)=0,0
Exp/Cntr=0.3,0.1

Type RM Length L Ch R = 1 ,6592    ,912.8,912.8,912.8
XS GIS Cut Line= 3
2371991.58788704881331.0478678842371903.46037689880775.844553916
2371915.21071157880299.955999086
#Sta/Elev= 30
       0   94.95      21    96.3   44.25   95.54   67.51   92.65   77.48   89.15
   110.7   82.22   129.3   73.79  135.04   72.47  178.04   74.23  223.92      73
  314.12   73.41  325.86   68.19   343.4   68.19  356.54   73.64  366.51   74.53
  413.02   72.56  464.76   72.27  486.11   72.97  496.07   75.66  502.72   75.99
  585.19   74.88     638   76.47  687.68    75.6  848.06   81.72  903.86    87.2
  916.98   90.16  947.13   99.82  976.06  105.69 1012.17  109.69 1038.19  116.13
#Mann= 3 ,0,0
       0     .12       0  314.12     .05       0  356.54     .12       0
Bank Sta=314.12,356.54
XS Rating Curve= 0 ,0
Exp/Cntr(USF)=0,0
Exp/Cntr=0.5,0.3

Type RM Length L Ch R = 1 ,5680    ,293.5,293.5,293.5
XS GIS Cut Line= 4
 2373212.5198401881341.6548465152373196.92097123881125.639110115
2372501.97479952880506.9903224492372197.91797148880228.048851198
#Sta/Elev= 30
       0   93.25  107.09   82.16  149.86   80.21  217.15   79.89   309.4    77.4
   455.6   77.44  564.19   75.05  660.84   75.58  711.24   73.14  753.06    74.5
  767.87   72.86  783.84   74.34     879    71.2  896.02   67.54  908.25   67.54
   920.1  70.674  941.98   71.25  955.16   72.93 1073.82   72.47 1115.62   74.29
 1157.53   73.31 1240.04   75.45 1283.72   79.52 1324.65   78.79 1378.06   81.12
 1420.08   85.38 1445.41    86.2 1473.51   89.79 1502.14   90.46 1559.62  108.91
#Mann= 3 ,0,0
       0     .12       0     879     .05       0   920.1     .12       0
#XS Ineff= 2 , 0
       0  782.55    92.6 1016.55       0    92.6
Permanent Ineff=
       F       F
Bank Sta=879,920.1
XS Rating Curve= 0 ,0
Exp/Cntr(USF)=0,0
Exp/Cntr=0.5,0.3

Type RM Length L Ch R = 3 ,5532    ,,,
Bridge Culvert--1,0,-1,-1, 0
Deck Dist Width WeirC Skew NumUp NumDn MinLoCord MaxHiCord MaxSubmerge Is_Ogee
42,145.7,2.6,0, 6, 6, , , 0.98, 0, 2,2,,
       0  824.54  824.55  974.55  974.56 1559.62
    92.6    92.6    92.6    92.6    92.6    92.6
                    87.5    87.5
       0 1035.29  1035.3  1185.3 1185.31 1792.15
    92.6    92.6    92.6    92.6    92.6    92.6
                    87.5    87.5
Pier Skew, UpSta & Num, DnSta & Num=  ,854.55, 2 ,1065.3, 2 , 0 , 0 , 0 ,,
       5       5
    67.5    87.5
       5       5
    67.5    87.5
Pier Skew, UpSta & Num, DnSta & Num=  ,884.55, 2 ,1095.3, 2 , 0 , 0 , 0 ,,
       5       5
    67.5    87.5
       5       5
    67.5    87.5
Pier Skew, UpSta & Num, DnSta & Num=  ,914.55, 2 ,1125.3, 2 , 0 , 0 , 0 ,,
       5       5
    67.5    87.5
       5       5
    67.5    87.5
Pier Skew, UpSta & Num, DnSta & Num=  ,944.55, 2 ,1155.3, 2 , 0 , 0 , 0 ,,
       5       5
    67.5    87.5
       5       5
    67.5    87.5
Abutment Skew #Up #Dn= , 2 , 2
  824.55  844.55
    86.5    66.5
 1035.29  1055.3
    86.5    66.5
Abutment Skew #Up #Dn= , 2 , 2
  954.55  974.55
    66.5    86.5
  1165.3 1185.29
    66.5    86.5
BR Coef=-1 , 0 , 0 ,, 0 ,,,0.8,0,,0,
WSPro=,,,, 1 ,,,, 0 ,,,, 0 ,,,,-1 ,-1 ,-1 , 0 , 0 , 0 , 0 , 0
BC Design=,, 0 ,, 0 ,,,,,,
BC Use User HTab Curves=0
BC User HTab FreeFlow(D)= 0

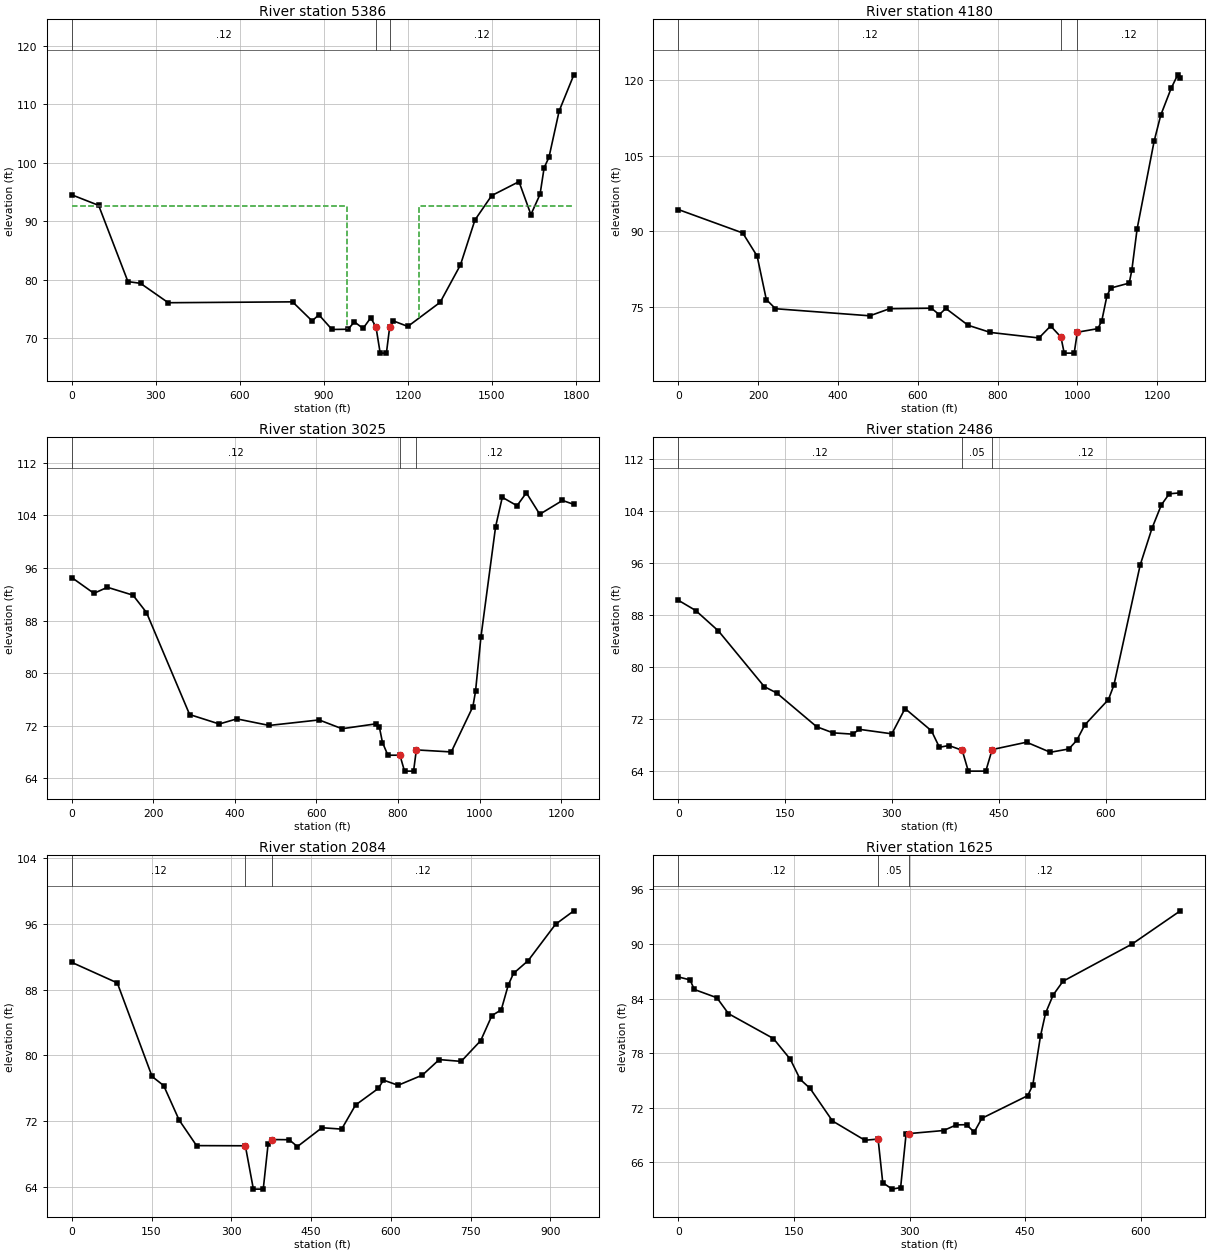
Type RM Length L Ch R = 1 ,5386    ,1206.5,1206.5,1206.5
XS GIS Cut Line= 2
2373715.94950238881228.2324393712372390.84181334880021.633565704
#Sta/Elev= 30
       0   94.54   95.93   92.74  200.45   79.72  245.47   79.42  344.45   76.11
  788.08   76.26  857.86      73  882.02   74.05  928.86   71.54  986.55   71.58
 1008.73   72.84  1039.8   71.72 1067.21   73.54  1085.971.96136 1100.88    67.5
 1123.05    67.5  1134.771.91929 1148.09      73 1199.55   72.06 1314.93   76.18
 1387.32   82.56 1439.18   90.25 1498.81   94.41 1596.36   96.79 1638.87   91.17
 1671.51   94.63 1686.13   99.18 1703.21  100.93 1739.74  108.87 1792.15  115.04
#Mann= 3 ,0,0
       0     .12       0  1085.9     .05       0  1134.7     .12       0
#XS Ineff= 2 , 0
       0   982.4    92.6  1238.2       0    92.6
Permanent Ineff=
       F       F
Bank Sta=1085.9,1134.7
XS Rating Curve= 0 ,0
Exp/Cntr(USF)=0,0
Exp/Cntr=0.5,0.3

Type RM Length L Ch R = 1 ,4180    ,1154.7,1154.7,1154.7
XS GIS Cut Line= 2
2374046.49470773881206.0258288342374022.99403835879948.740017308
#Sta/Elev= 30
       0   94.34  161.52    89.7  197.62   85.13  220.59   76.54  243.56   74.72
  479.84   73.32  529.21   74.72  634.08   74.82  653.77   73.55  670.18   74.78
  725.97   71.45  781.76   70.03  903.47   68.94  932.72   71.31   958.5   69.12
  966.72   65.94   991.7   65.94   999.6  70.074 1050.86   70.78  1060.7   72.28
 1073.83    77.3 1083.31   78.81 1129.62   79.79 1136.18    82.4 1149.31    90.5
 1191.97  107.86 1208.38  112.96 1234.63  118.32 1251.04  120.97 1257.51  120.35
#Mann= 3 ,0,0
       0     .12       0   958.5     .05       0   999.6     .12       0
Bank Sta=958.5,999.6
XS Rating Curve= 0 ,0
Exp/Cntr(USF)=0,0
Exp/Cntr=0.3,0.1

Type RM Length L Ch R = 1 ,3025    ,539,539,539
XS GIS Cut Line= 4
2375130.22613982881150.9458156392375094.23822683880857.326687737
2375006.70741348880173.6482118342375007.19970881879927.367252335
#Sta/Elev= 30
       0   94.54   54.31   92.14   87.37   93.06  150.18   91.86  183.24   89.22
  289.02    73.7  361.79   72.26  404.79   73.04  484.18   72.04  606.57   72.88
  662.81   71.54  745.51   72.28  754.24   71.84  762.05   69.44  775.28   67.51
   804.8  67.514  816.07   65.09  838.26   65.09   845.1  68.319  930.75   68.01
  983.68   74.89  990.25   77.23 1003.37   85.43 1039.47  102.28 1055.87  106.75
 1091.96  105.47 1114.93  107.43 1147.74  104.17 1203.52  106.27 1231.36  105.67
#Mann= 3 ,0,0
       0     .12       0   804.8     .05       0   845.1     .12       0
Bank Sta=804.8,845.1
XS Rating Curve= 0 ,0
Exp/Cntr(USF)=0,0
Exp/Cntr=0.3,0.1

Type RM Length L Ch R = 1 ,2486    ,401.7,401.7,401.7
XS GIS Cut Line= 3
 2375809.2555984880510.4897835882375598.50002385880303.949320524
2375407.41496958879941.449732288
#Sta/Elev= 30
       0    90.3   24.55   88.71   56.51   85.56  120.82      77  138.14   76.03
  194.33   70.83   217.3   69.89  244.86   69.69  254.25   70.43  299.87   69.74
  318.41   73.63  355.51    70.2  366.63   67.67     380   67.94   398.7  67.203
  407.24      64  431.78      64   440.7  67.316  489.03   68.45  522.41    66.9
  548.38   67.41  559.51   68.74  570.63   71.09  604.01   75.02   611.7   77.26
  648.52   95.71  665.13  101.37   678.2  104.95  689.32  106.67  704.87  106.82
#Mann= 3 ,0,0
       0     .12       0   398.7     .05       0   440.7     .12       0
Bank Sta=398.7,440.7
XS Rating Curve= 0 ,0
Exp/Cntr(USF)=0,0
Exp/Cntr=0.3,0.1

Type RM Length L Ch R = 1 ,2084    ,436.4,436.4,436.4
XS GIS Cut Line= 5
2376046.70687907880377.0112530362375917.44346001880105.839080442
2375897.77293972879810.7812760642375975.04998372879611.265998818
2376070.59251085879517.128508849
#Sta/Elev= 30
       0   91.32   85.62   88.82  151.05   77.42  172.86   76.31  201.94   72.11
  234.65      69  326.42   68.98  341.52    63.7  360.09    63.7  369.17   69.16
   375.7  69.739  408.87   69.72  424.28   68.88  470.53   71.18  507.52   71.01
  533.59   73.94  576.34   75.96   586.2   76.98  613.66   76.35   659.4   77.59
  691.07   79.48  732.34   79.26  769.06   81.79  790.09   84.84  807.68   85.54
  820.92   88.57  830.73   89.98  858.37   91.54  909.74   95.96   944.2    97.6
#Mann= 3 ,0,0
       0     .12       0  326.42     .05       0   375.7     .12       0
Bank Sta=326.42,375.7
XS Rating Curve= 0 ,0
Exp/Cntr(USF)=0,0
Exp/Cntr=0.3,0.1

Type RM Length L Ch R = 1 ,1625    ,320.8,320.8,320.8
XS GIS Cut Line= 3
2376375.71196143 880226.503897792376278.76439713880031.203732035
2376225.37298491879601.262359941
#Sta/Elev= 30
       0   86.38   15.32   86.05   20.83      85   50.13   84.09   65.18   82.34
   123.4   79.61  145.38   77.33   158.2   75.12  171.02   74.13  200.06   70.55
  242.12   68.43  259.25   68.56  265.29   63.77  277.39   63.06  288.47   63.23
  295.52   69.09  298.91   69.16  344.22    69.5  360.75   70.12  373.98   70.14
   383.9   69.32  393.82   70.84  453.33   73.33  459.94    74.5  469.86   79.86
  476.47   82.39  486.39    84.4  499.08    85.9  588.89      90  651.28   93.64
#Mann= 3 ,0,0
       0     .12       0  259.25     .05       0  298.91     .12       0
Bank Sta=259.25,298.91
XS Rating Curve= 0 ,0
Exp/Cntr(USF)=0,0
Exp/Cntr=0.5,0.3

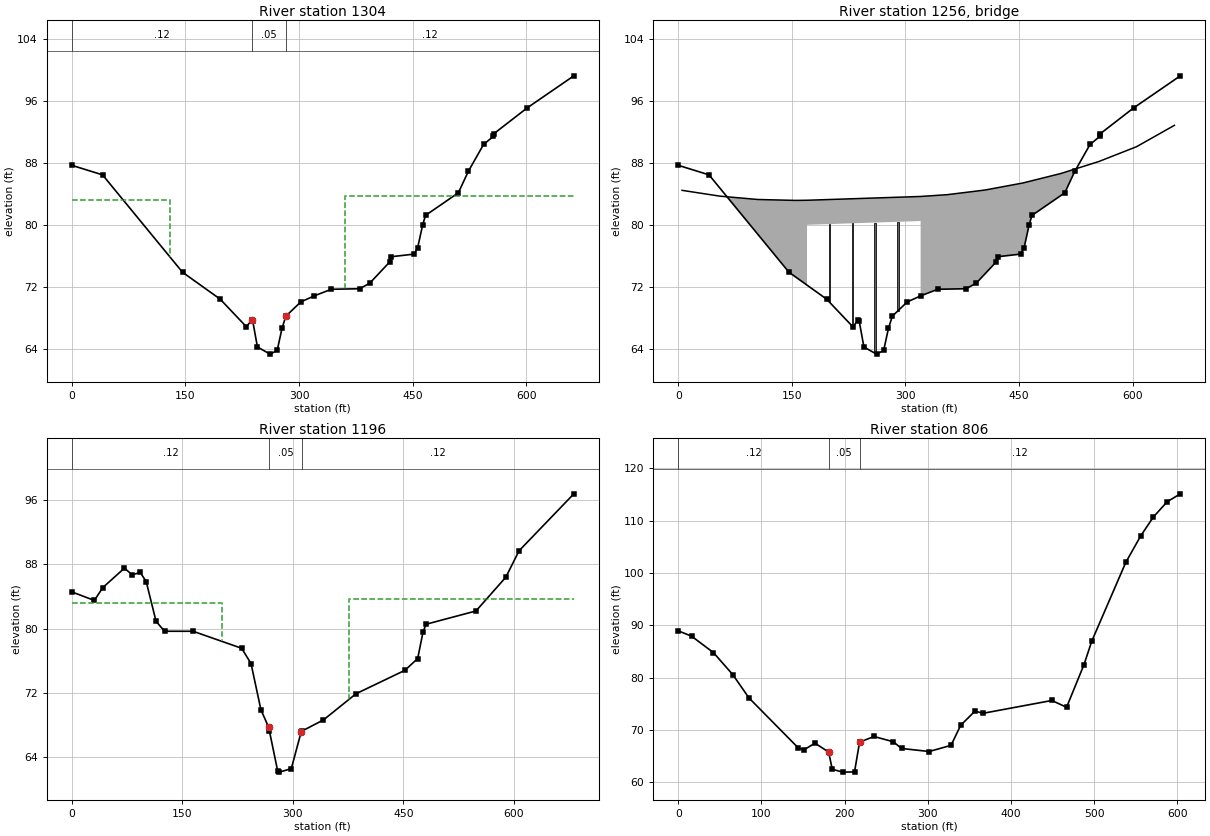
Type RM Length L Ch R = 1 ,1304    ,108.3,108.3,108.3
XS GIS Cut Line= 4
2376449.95254505 880101.623968952376535.65981204879902.108691704
2376573.59581546879774.2503098072376626.98722768879466.547170956
#Sta/Elev= 30
       0   87.68   40.61   86.45  146.18   73.88  195.86   70.41   230.5   66.84
   237.8   67.74  238.84   67.61   245.1   64.23  261.79   63.31  271.18   63.78
  277.51   66.63  282.65   68.21  302.36   70.05  320.14   70.83  342.56   71.68
  379.99   71.75  393.31   72.46  419.95   75.23  421.75   75.88  451.91   76.22
  456.58   77.03  463.24      80  467.04   81.22  510.33   84.13  523.49    86.9
  543.64   90.37  556.64   91.42  556.95   91.74  601.19   95.09  662.81   99.23
#Mann= 3 ,0,0
       0     .12       0   237.8     .05       0  282.65     .12       0
#XS Ineff= 2 , 0
       0 129.625   83.15 360.375       0   83.66
Permanent Ineff=
       F       F
Bank Sta=237.8,282.65
XS Rating Curve= 0 ,0
Exp/Cntr(USF)=0,0
Exp/Cntr=0.5,0.3

Type RM Length L Ch R = 3 ,1256    ,,,
Bridge Culvert--1,0,-1,-1, 0
Deck Dist Width WeirC Skew NumUp NumDn MinLoCord MaxHiCord MaxSubmerge Is_Ogee
40.375,46.25,2.6,0, 15, 15, , , 0.98, 0, 2,2,,
       5      55     105     155     170     170     320     320     355     405
     455     505     555     605     655
   84.45    83.7   83.27   83.15   83.17   83.17   83.66   83.66   83.89   84.49
    85.4   86.62   88.16   90.08   92.84
                                              80   80.49
                                        
      50     100     150     200     215     215     365     365     400     450
     500     550     600     605     655
   84.45    83.7   83.27   83.15   83.17   83.17   83.66   83.66   83.89   84.49
    85.4   86.62   88.16   90.08   92.84
                                           80.78   81.27
                                        
Pier Skew, UpSta & Num, DnSta & Num=  ,200, 2 ,245, 2 , 0 , 0 , 0 ,,
       2       2
       0      82
       2       2
       0      82
Pier Skew, UpSta & Num, DnSta & Num=  ,230, 2 ,275, 2 , 0 , 0 , 0 ,,
       2       2
       0      82
       2       2
       0      82
Pier Skew, UpSta & Num, DnSta & Num=  ,260, 2 ,305, 2 , 0 , 0 , 0 ,,
       2       2
       0      82
       2       2
       0      82
Pier Skew, UpSta & Num, DnSta & Num=  ,290, 2 ,335, 2 , 0 , 0 , 0 ,,
       2       2
       0      82
       2       2
       0      82
Abutment Skew #Up #Dn= , 3 , 3
     170     172     272
      78      78      28
     215     217     317
      78      78      28
Abutment Skew #Up #Dn= , 3 , 3
     218     318     320
   28.49   78.49   78.49
     263     363     365
   28.49   78.49   78.49
BR Coef=-1 , 0 , 0 ,, 0 ,,,0.8,0,,0,
WSPro=,,,, 1 ,,,, 0 ,,,, 0 ,,,,-1 ,-1 ,-1 , 0 , 0 , 0 , 0 , 0
BC Design=,, 0 ,, 0 ,,4,200,245,30,4
BC Use User HTab Curves=0
BC User HTab FreeFlow(D)= 0

Type RM Length L Ch R = 1 ,1196    ,390.5,390.5,390.5
XS GIS Cut Line= 3
2376550.93006877880115.6743405872376647.87763307879895.083505886
2376736.39497438879463.737096629
#Sta/Elev= 30
       0   84.57   30.61    83.5   42.18   85.11    71.4   87.52    82.1    86.7
   92.85   86.99     101   85.86  114.36    80.9   125.9   79.66  164.54   79.66
  230.47   77.54  243.23   75.64  256.62   69.89  267.19   67.68  268.29   67.19
  279.52   62.19  281.56    62.1  297.89   62.53   311.2  67.084  312.18   67.21
  341.58   68.61  385.68   71.87  452.04   74.79  469.39   76.26  476.54   79.52
  480.62   80.53   548.5   82.19  589.02    86.4  606.93   89.69  681.29   96.79
#Mann= 3 ,-1,0
       0     .12       0  268.29     .05       0  312.18     .12       0
#XS Ineff= 2 , 0
       0204.1625   83.15375.8375       0   83.66
Permanent Ineff=
       F       F
Bank Sta=267.19,311.2
XS Rating Curve= 0 ,0
Exp/Cntr(USF)=0,0
Exp/Cntr=0.5,0.3

Type RM Length L Ch R = 1 ,806     ,,,
XS GIS Cut Line= 5
2377008.50454103879958.0559154192377018.14609691879810.829401343
2377040.95607306879718.3072385062377039.60608759879626.166422496
 2376854.6032482879431.421241863
#Sta/Elev= 30
       0   88.97   16.01   87.95   42.32   84.81   65.69   80.58   85.07   76.14
  144.25   66.61  150.92   66.22  164.44    67.5   180.8   65.81  185.15   62.53
  197.65   61.97  211.93   62.01     218    67.7   235.4   68.78  258.59   67.77
  268.43   66.49  301.71   65.91  327.96   67.09   339.6   70.93  356.98   73.66
  366.03    73.2  449.17   75.66  466.87   74.36  487.76    82.5  497.27   87.04
     538  102.03   556.1  107.14  571.31  110.74  587.78  113.63   603.6  115.15
#Mann= 3 ,0,0
       0     .12       0   180.8     .05       0     218     .12       0
Bank Sta=180.8,218
XS Rating Curve= 0 ,0
Exp/Cntr(USF)=0,0
Exp/Cntr=0.3,0.1
LCMann Table=0

Chan Stop Cuts=-1
Use User Specified Reach Order=0
Composite Channel Slope=5

--- HighHillCreek.g01 (geometry) ---

Geom Title=Corrected Effective - FEMA
Program Version=6.60

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
River Reach=High Hill Creek ,Reach 1