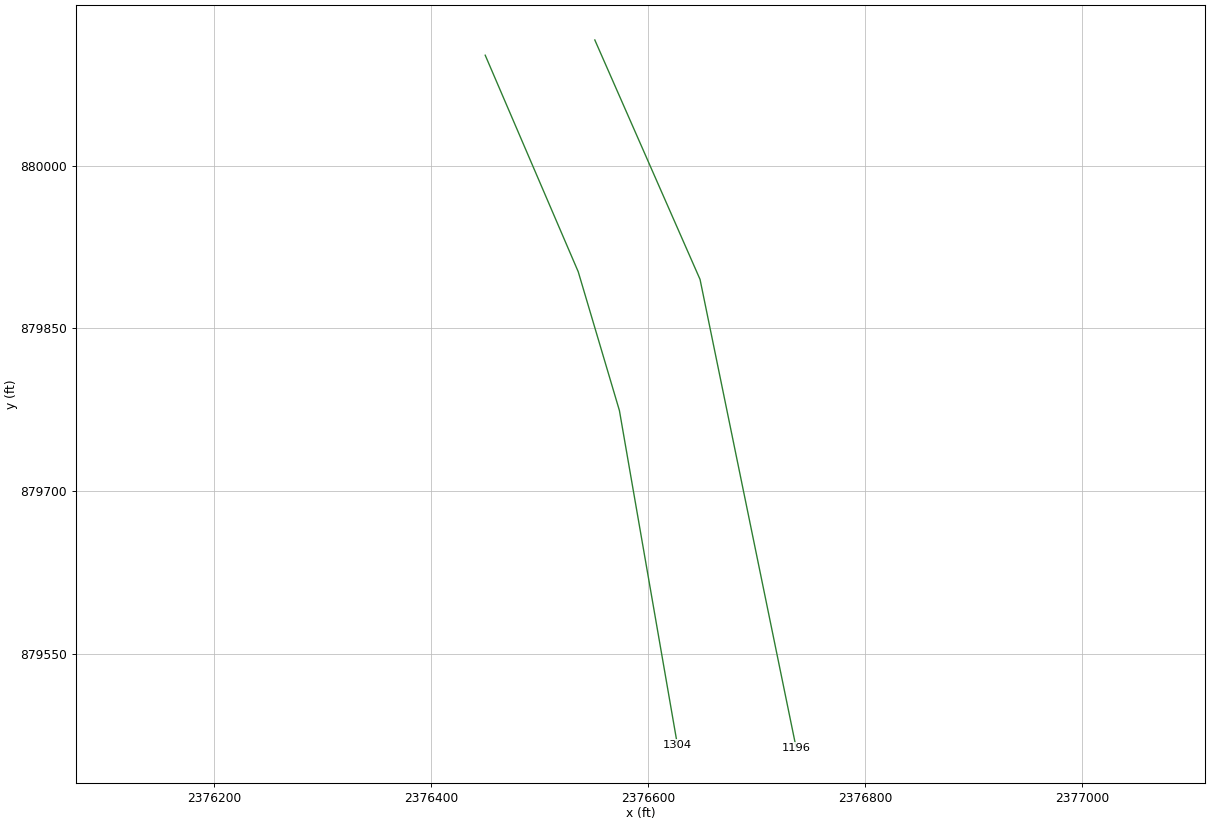
HEC-RAS study HighHillCreek.prj: S-21-356 over High Hill Creek

--- HighHillCreek.g01 (geometry) --- (continued)

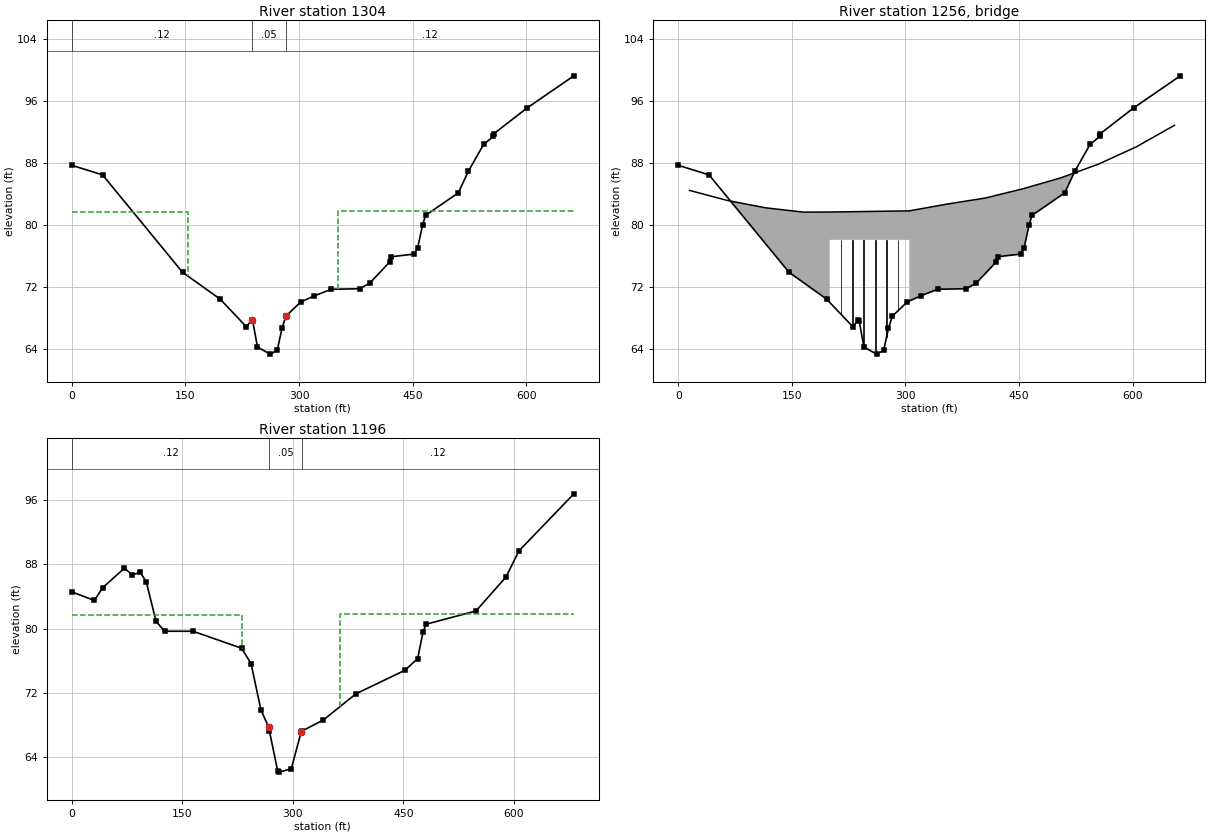
Type RM Length L Ch R = 1 ,1304    ,108.3,108.3,108.3
XS GIS Cut Line= 4
2376449.95254505 880101.623968952376535.65981204879902.108691704
2376573.59581546879774.2503098072376626.98722768879466.547170956
#Sta/Elev= 30
       0   87.68   40.61   86.45  146.18   73.88  195.86   70.41   230.5   66.84
   237.8   67.74  238.84   67.61   245.1   64.23  261.79   63.31  271.18   63.78
  277.51   66.63  282.65   68.21  302.36   70.05  320.14   70.83  342.56   71.68
  379.99   71.75  393.31   72.46  419.95   75.23  421.75   75.88  451.91   76.22
  456.58   77.03  463.24      80  467.04   81.22  510.33   84.13  523.49    86.9
  543.64   90.37  556.64   91.42  556.95   91.74  601.19   95.09  662.81   99.23
#Mann= 3 ,0,0
       0     .12       0   237.8     .05       0  282.65     .12       0
#XS Ineff= 2 , 0
       0     153   81.64     352       0    81.8
Permanent Ineff=
       F       F
Bank Sta=237.8,282.65
XS Rating Curve= 0 ,0
Exp/Cntr(USF)=0,0
Exp/Cntr=0.5,0.3

Type RM Length L Ch R = 3 ,1256    ,,,
Bridge Culvert--1,0,-1,-1, 0
Deck Dist Width WeirC Skew NumUp NumDn MinLoCord MaxHiCord MaxSubmerge Is_Ogee
47,33,2.6,0, 15, 15, , , 0.98, 0, 2,2,,
      15      65     115     165     200     200     305     305     355     405
     455     505     555     605     655
  84.438   83.14    82.2   81.64   81.65   81.65    81.8    81.8   82.68   83.45
   84.65   86.06   87.84   90.08   92.84
                                           78.06   78.06
                                        
      60     110     160     210     245     245     350     350     400     450
     500     550     600     650     700
  84.438   83.14    82.2   81.64   81.65   81.65    81.8    81.8   82.68   83.45
   84.65   86.06   87.84   90.08   92.84
                                           79.63   79.63
                                        
Pier Skew, UpSta & Num, DnSta & Num=  ,215, 2 ,260, 2 , 0 , 0 , 0 ,,
       1       1
       0      80
       1       1
       0      80
Pier Skew, UpSta & Num, DnSta & Num=  ,230, 2 ,275, 2 , 0 , 0 , 0 ,,
       1       1
       0      80
       1       1
       0      80
Pier Skew, UpSta & Num, DnSta & Num=  ,245, 2 ,290, 2 , 0 , 0 , 0 ,,
       1       1
       0      80
       1       1
       0      80
Pier Skew, UpSta & Num, DnSta & Num=  ,260, 2 ,305, 2 , 0 , 0 , 0 ,,
       1       1
       0      80
       1       1
       0      80
Pier Skew, UpSta & Num, DnSta & Num=  ,275, 2 ,320, 2 , 0 , 0 , 0 ,,
       1       1
       0      80
       1       1
       0      80
Pier Skew, UpSta & Num, DnSta & Num=  ,290, 2 ,335, 2 , 0 , 0 , 0 ,,
       1       1
       0      80
       1       1
       0      80
Abutment Skew #Up #Dn= , 2 , 2
  199.99     220
      74      54
  244.99     265
      74      54
Abutment Skew #Up #Dn= , 2 , 2
     285  305.01
      54      74
     330  350.01
      54      74
BR Coef=-1 , 0 , 0 ,, 0 ,,,0.8,0,,0,
WSPro=,,,, 1 ,,,, 0 ,,,, 0 ,,,,-1 ,-1 ,-1 , 0 , 0 , 0 , 0 , 0
BC Design=,, 0 ,, 0 ,,,,,,
BC Use User HTab Curves=0
BC User HTab FreeFlow(D)= 0

Type RM Length L Ch R = 1 ,1196    ,390.5,390.5,390.5
XS GIS Cut Line= 3
2376550.93006877880115.6743405872376647.87763307879895.083505886
2376736.39497438879463.737096629
#Sta/Elev= 30
       0   84.57   30.61    83.5   42.18   85.11    71.4   87.52    82.1    86.7
   92.85   86.99     101   85.86  114.36    80.9   125.9   79.66  164.54   79.66
  230.47   77.54  243.23   75.64  256.62   69.89  267.19   67.68  268.29   67.19
  279.52   62.19  281.56    62.1  297.89   62.53   311.2  67.084  312.18   67.21
  341.58   68.61  385.68   71.87  452.04   74.79  469.39   76.26  476.54   79.52
  480.62   80.53   548.5   82.19  589.02    86.4  606.93   89.69  681.29   96.79
#Mann= 3 ,-1,0
       0     .12       0  268.29     .05       0  312.18     .12       0
#XS Ineff= 2 , 0
       0  230.85   81.64  364.15       0    81.8
Permanent Ineff=
       F       F
Bank Sta=267.19,311.2
XS Rating Curve= 0 ,0
Exp/Cntr(USF)=0,0
Exp/Cntr=0.5,0.3

--- HighHillCreek.g02 (geometry) ---

Geom Title=Existing - SCDOT
Program Version=6.60

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
River Reach=High Hill Creek ,Reach 1
Reach XY= 30
2363243.59977666883095.1585389252366434.63516231 881068.63046019
2368423.81331766881275.8878175882370371.18916704880731.220620871
     2371160.465     881197.2497     2373858.439     880222.0221
2377959.08395706879888.1722408542378179.99401003879371.546614335
2379704.15649189879174.0132865482379662.07838656878643.361624919
2382002.04649912877858.6026855812384092.27638126880436.938589516
2384750.79872963880744.1087584062385524.28947058880225.906608263
2385426.88644899881376.5609699932386745.53589587881203.803959342
2386221.72409087881444.7862497972386368.91087905882130.214920252
2385575.25662905881669.8954552522385823.45395814882423.145488889
 2386858.0904986882431.8035352532386770.06702723883213.913723436
2387982.19351815882688.6589107082389005.59890139884108.415479815
2388592.61008984884416.209028043 2390010.7980842883647.374510951
2390354.95542716884088.9348754972390604.30716243883562.958558905
2391538.07746275884399.325837634 2393610.0421929884237.968149105

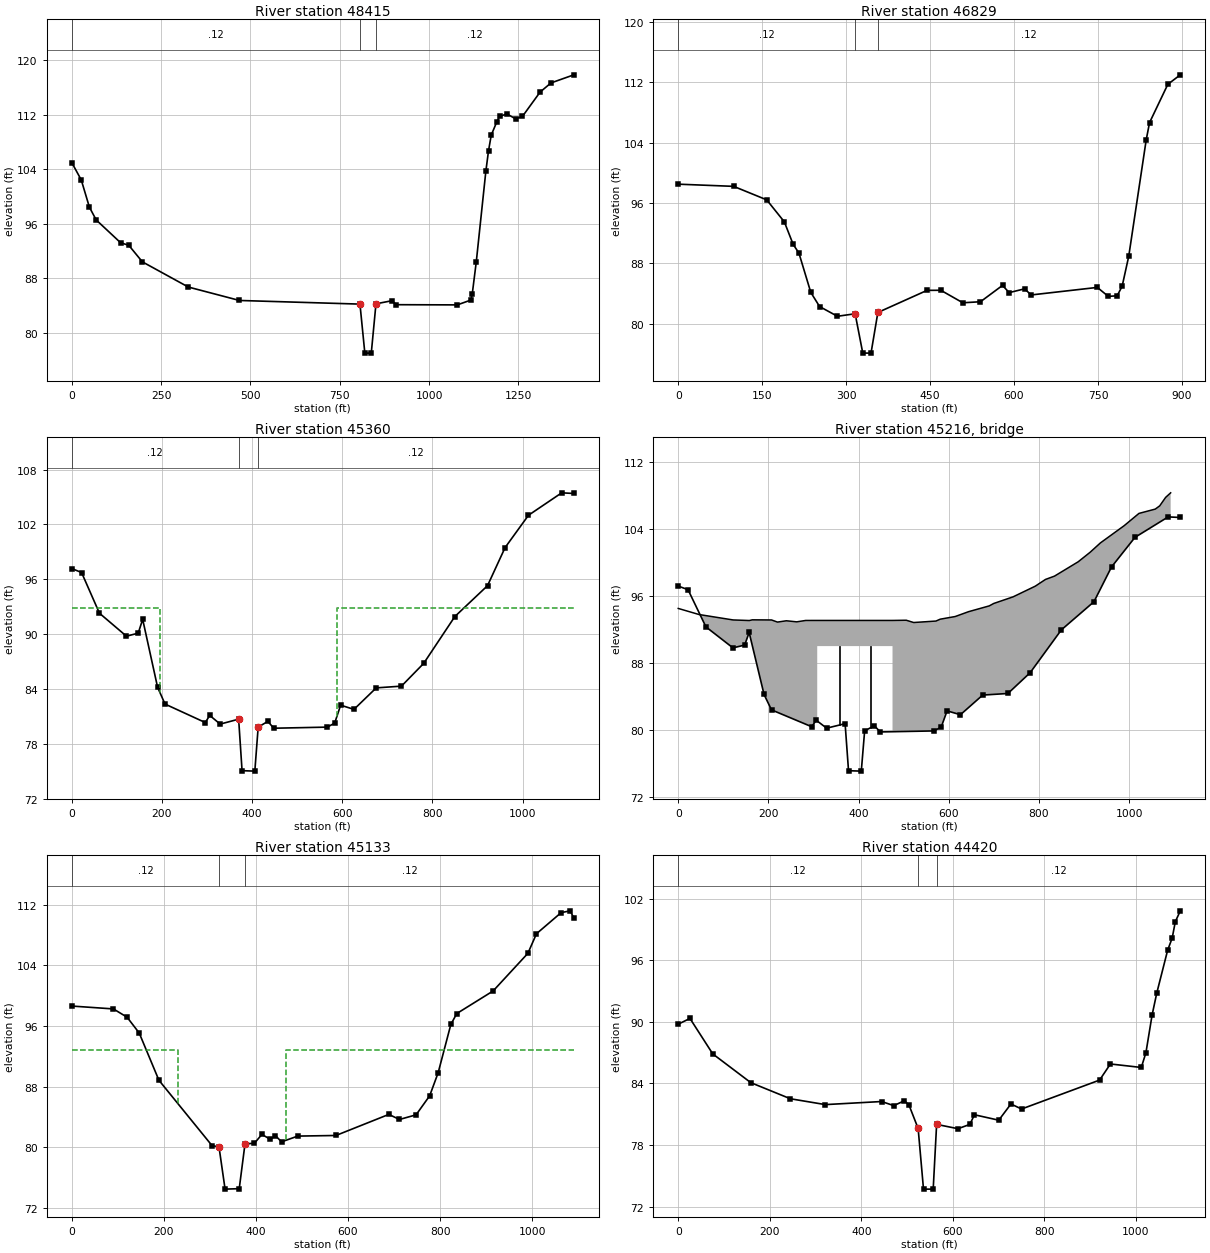
Type RM Length L Ch R = 1 ,48415   ,1585.7,1585.7,1585.7
XS GIS Cut Line= 2
  2365371.411892882855.6956462862364662.86671036 881642.17983147
#Sta/Elev= 30
       0  104.97   26.57  102.42   49.36   98.42   68.36   96.55  136.75    93.2
  159.55   92.83  197.54    90.4   326.2    86.7  469.36   84.73   806.6  84.195
  820.25      77  838.26      77   851.4  84.236  896.65    84.7  908.05   84.11
 1079.02   84.08 1117.02   84.79 1120.82   85.66 1132.21   90.43 1158.93   103.7
 1166.41   106.7 1174.01     109 1189.21   110.9 1197.31  111.74  1217.7  112.11
  1242.4  111.39  1261.4  111.75 1310.79  115.32 1341.19  116.66 1405.22  117.85
#Mann= 3 ,0,0
       0     .12       0   806.6     .05       0   851.4     .12       0
Bank Sta=806.6,851.4
XS Rating Curve= 0 ,0
Exp/Cntr(USF)=0,0
Exp/Cntr=0.3,0.1

Type RM Length L Ch R = 1 ,46829   ,1469.3,1469.3,1469.3
XS GIS Cut Line= 2
2366204.20714159881740.5968944942365708.08189925880993.145049117
#Sta/Elev= 30
       0    98.5   99.01   98.21  158.08   96.42  189.58    93.5  205.34   90.51
  215.59   89.37  236.84   84.14  252.59   82.26  284.44   80.97   316.1  81.304
  329.72   76.09  344.47   76.08   356.7  81.476  444.64   84.41  469.19   84.42
  508.57   82.76  540.08    82.9  579.46   85.07  591.27   84.11  618.84   84.61
  630.65    83.8   748.8    84.8  768.49   83.61  784.24   83.69  793.15   84.95
  804.98   88.94  836.22   104.4  842.16  106.67  874.82  111.75  897.12  113.01
#Mann= 3 ,0,0
       0     .12       0   316.1     .05       0   356.7     .12       0
Bank Sta=316.1,356.7
XS Rating Curve= 0 ,0
Exp/Cntr(USF)=0,0
Exp/Cntr=0.5,0.3

Type RM Length L Ch R = 1 ,45360   ,227.2,227.2,227.2
XS GIS Cut Line= 4
 2366924.9056944881522.1839907562366884.43137281881190.680023462
2366861.30318904 880969.034929052366818.90151881880413.958518697
#Sta/Elev= 30
       0   97.18   21.73   96.75    61.4    92.3  121.27   89.79  147.34   90.12
  157.26   91.63  190.31   84.21  206.84   82.37  296.09   80.35     306   81.13
  329.14   80.18   370.1  80.719  377.67   75.09  405.99   75.04   413.4   79.85
  434.92   80.48  447.91   79.73  566.65   79.85   583.1   80.29  596.27   82.25
  625.88   81.79  675.24   84.14  731.18   84.33  780.55   86.82  849.65   91.94
  922.04   95.31  960.96   99.47 1012.93  103.01 1086.58  105.46 1113.51  105.39
#Mann= 3 ,0,0
       0     .12       0   370.1     .05       0   413.4     .12       0
#XS Ineff= 2 , 0
       0  195.75   92.88  587.75       0   92.82
Permanent Ineff=
       F       F
Bank Sta=370.1,413.4
XS Rating Curve= 0 ,0
Exp/Cntr(USF)=0,0
Exp/Cntr=0.5,0.3

Type RM Length L Ch R = 3 ,45216   ,,,
Bridge Culvert--1,0,-1,-1, 0
Deck Dist Width WeirC Skew NumUp NumDn MinLoCord MaxHiCord MaxSubmerge Is_Ogee
112.5,46.5,2.6,0, 35, 32, , , 0.98, 0, 2,2,,
       0  45.978 121.546 157.687 164.258  206.97 220.113 239.826 262.695 282.532
  308.24  308.25  475.25  475.26 505.742  522.19 571.534 581.025 614.266 643.847
 689.806 699.653 742.362 791.735 814.533 834.493 887.096 913.378 936.375 988.939
1021.7921057.9291067.7851080.9261092.095
  94.506  93.781  93.131   93.06  93.144  93.128  92.875  93.031  92.904  93.068
   93.07   93.07   93.07   93.07  93.095  92.822  92.998  93.222   93.54  94.119
  94.813  95.101  95.888  97.169  97.979  98.375 100.093 101.224 102.352 104.408
 105.878 106.394 106.782 107.793  108.34
                                                                                
              90      90
                                                                                
                                        
       0  45.978 121.546 157.687 164.258  206.97 220.113  264.54  264.55  431.55
  431.56 505.742  522.19 571.534 581.025 614.266 643.847 689.806 699.653 742.362
 791.735 814.533 834.493 887.096 913.378 936.375 988.9391021.7921057.9291067.785
1080.9261092.095
  94.506  93.781  93.131   93.06  93.144  93.128  92.875   93.07   93.07   93.07
   93.07  93.095  92.822  92.998  93.222   93.54  94.119  94.813  95.101  95.888
  97.169  97.979  98.375 100.093 101.224 102.352 104.408 105.878 106.394 106.782
 107.793  108.34
                                                                      90      90
                                                                                
                                                                                
                
Pier Skew, UpSta & Num, DnSta & Num=  ,357.25, 2 ,313.55, 2 , 0 , 0 , 0 ,,
       3       3
       0      91
       3       3
       0      91
Pier Skew, UpSta & Num, DnSta & Num=  ,426.25, 2 ,382.55, 2 , 0 , 0 , 0 ,,
       3       3
       0      91
       3       3
       0      91
Abutment Skew #Up #Dn= , 2 , 2
  308.25  328.25
      89      69
  264.55  284.55
      89      69
Abutment Skew #Up #Dn= , 2 , 2
  455.25  475.25
      69      89
  411.55  431.55
      69      89
BR Coef=-1 , 0 , 0 ,, 0 ,,,0.8,0,,0,
WSPro=,,,, 1 ,,,, 0 ,,,, 0 ,,,,-1 ,-1 ,-1 , 0 , 0 , 0 , 0 , 0
BC Design=,, 0 ,, 0 ,,,,,,
BC Use User HTab Curves=0
BC User HTab FreeFlow(D)= 0

Type RM Length L Ch R = 1 ,45133   ,713,713,713
XS GIS Cut Line= 4
 2367055.9654024881508.6925502272367082.94828345881204.171463991
2367063.67479698880670.2958887562367067.52949428880419.740564638
#Sta/Elev= 30
       0   98.63   90.46   98.25  120.11   97.16  146.46   95.08  189.28   88.85
  304.57   80.24   319.8  80.066  332.97    74.5  363.73   74.56   376.3  80.485
   396.5   80.53  412.92   81.71  431.38   81.06  442.47   81.55   455.6   80.73
  490.81   81.49   573.8   81.57  688.72   84.35   711.7   83.68  747.81   84.29
  777.36    86.8  795.85   89.85  823.33    96.2  836.22   97.64  915.22  100.62
   990.7  105.58 1009.33  108.16 1062.89  110.94 1082.58  111.18 1090.52  110.23
#Mann= 3 ,0,0
       0     .12       0   319.8     .05       0   376.3     .12       0
#XS Ineff= 2 , 0
       0  230.45   92.88  465.65       0   92.82
Permanent Ineff=
       F       F
Bank Sta=319.8,376.3
XS Rating Curve= 0 ,0
Exp/Cntr(USF)=0,0
Exp/Cntr=0.5,0.3

Type RM Length L Ch R = 1 ,44420   ,501.1,501.1,501.1
XS GIS Cut Line= 3
 2367809.5587234 881624.333469052367670.78962081880774.372715697
2367726.68273157880545.018226697
#Sta/Elev= 30
       0   89.78   25.62   90.34   75.49   86.88   158.6   84.08  245.04   82.51
  321.51   81.94  444.52   82.24  471.11   81.84  494.39   82.32  504.36   81.89
   524.3  79.611  536.02    73.7  557.22    73.7   564.7  80.012  611.36   79.59
  637.34   80.01  647.32   80.95  700.51   80.42  727.11      82  750.38   81.51
  920.86   84.33   944.5    85.9 1012.04   85.56 1022.17   87.01 1035.68   90.69
 1045.81   92.81 1069.45   96.97 1079.59   98.19 1086.34   99.77 1097.28  100.83
#Mann= 3 ,0,0
       0     .12       0   524.3     .05       0   564.7     .12       0
Bank Sta=524.3,564.7
XS Rating Curve= 0 ,0
Exp/Cntr(USF)=0,0
Exp/Cntr=0.3,0.1

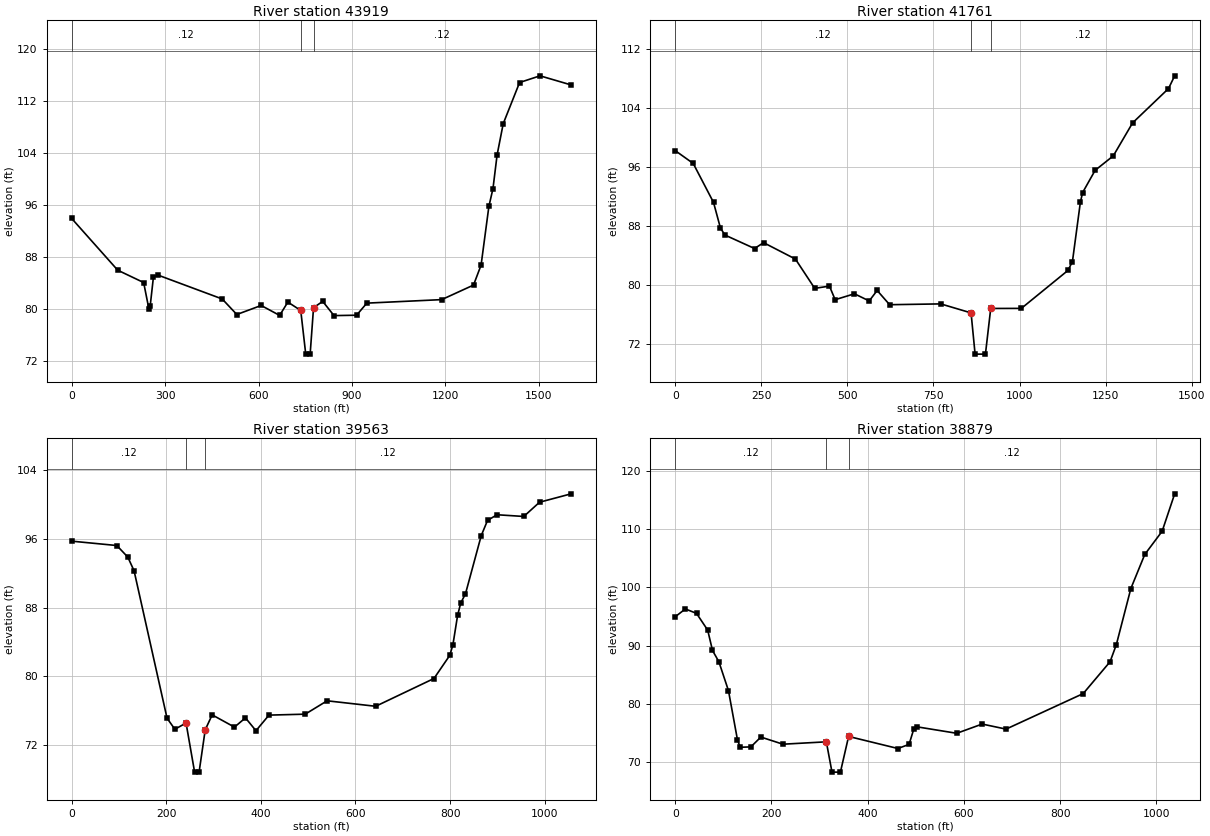
Type RM Length L Ch R = 1 ,43919   ,2157.9,2157.9,2157.9
XS GIS Cut Line= 4
2368289.25326603881857.0929439242368202.21374983881603.227688338
2368111.54758712880515.233735824 2368104.2942941880272.248419762
#Sta/Elev= 30
       0   93.99  147.92   86.02  231.17   84.12   248.1   80.03  251.98   80.44
  262.38    84.9  275.86   85.29  483.29   81.59  530.21    79.2   608.4   80.59
  667.67   79.06  694.01   81.11   735.4  79.824  751.46    73.1   765.6    73.1
   776.5  80.252  805.95   81.22  842.17   79.03   914.6   79.09  947.53   80.95
 1187.88   81.49 1290.02   83.73 1314.34   86.81 1339.34   95.84 1352.51   98.59
 1365.66  103.75 1385.36  108.57 1437.88  114.91 1503.53  115.94 1603.23  114.54
#Mann= 3 ,0,0
       0     .12       0   735.4     .05       0   776.5     .12       0
Bank Sta=735.4,776.5
XS Rating Curve= 0 ,0
Exp/Cntr(USF)=0,0
Exp/Cntr=0.3,0.1

Type RM Length L Ch R = 1 ,41761   ,2198.1,2198.1,2198.1
XS GIS Cut Line= 2
2369765.29839494881864.3462369412369620.23253461880420.940926606
#Sta/Elev= 30
       0    98.2   52.29   96.46  111.23   91.18  131.43   87.69  144.62   86.75
  230.36   84.93  256.74   85.72  349.08    83.5  405.14   79.53  448.01   79.83
  464.49   77.99  520.55   78.79  563.42   77.82  586.51   79.24  622.78   77.31
  771.18   77.42   859.3    76.2  870.98   70.61  901.03   70.61   916.4    76.8
 1005.31   76.81 1140.51   81.95 1153.71   83.15 1176.79   91.21 1183.38   92.52
 1219.66   95.53 1272.42   97.49 1328.48  101.96 1432.69  106.61 1450.68  108.34
#Mann= 3 ,0,0
       0     .12       0   859.3     .05       0   916.4     .12       0
Bank Sta=859.3,916.4
XS Rating Curve= 0 ,0
Exp/Cntr(USF)=0,0
Exp/Cntr=0.3,0.1

Type RM Length L Ch R = 1 ,39563   ,683.4,683.4,683.4
XS GIS Cut Line= 3
2371427.57182206881401.5498760072371336.50672823880778.782137588
2371263.06713644880358.707672522
#Sta/Elev= 30
       0   95.74   95.53   95.23  118.74   93.88     132   92.28  201.68   75.09
  218.22    73.8   241.9  74.526  259.96    68.8  269.43    68.8   282.4  73.736
  297.08   75.48  344.23   74.05  367.44   75.13  389.66   73.63  417.18   75.45
   493.8   75.56  540.09   77.12  642.73   76.48  765.97   79.72  799.28   82.41
  805.95   83.63  815.94   87.09   822.6   88.53  832.59    89.6   865.9   96.39
  879.23   98.16  899.21   98.82  955.84   98.62  989.14  100.28 1055.84  101.26
#Mann= 3 ,0,0
       0     .12       0   241.9     .05       0   282.4     .12       0
Bank Sta=241.9,282.4
XS Rating Curve= 0 ,0
Exp/Cntr(USF)=0,0
Exp/Cntr=0.3,0.1

Type RM Length L Ch R = 1 ,38879   ,912.8,912.8,912.8
XS GIS Cut Line= 3
2371991.58788704881331.0478678842371903.46037689880775.844553916
2371915.21071157880299.955999086
#Sta/Elev= 30
       0   94.95      21    96.3   44.25   95.54   67.51   92.65   77.48   89.15
   90.77    87.2   110.7   82.22   129.3   73.79  135.04   72.47  157.21   72.54
  178.04   74.23  223.92      73  314.12   73.41  325.86   68.19   343.4   68.19
   360.4  74.337  462.85   72.26  486.11   72.97  496.07   75.66  502.72   75.99
  585.19   74.88     638   76.47  687.68    75.6  848.06   81.72  903.86    87.2
  916.98   90.16  947.13   99.82  976.06  105.69 1012.17  109.69 1038.19  116.13
#Mann= 3 ,0,0
       0     .12       0  314.12     .05       0   360.4     .12       0
Bank Sta=314.12,360.4
XS Rating Curve= 0 ,0
Exp/Cntr(USF)=0,0
Exp/Cntr=0.5,0.3