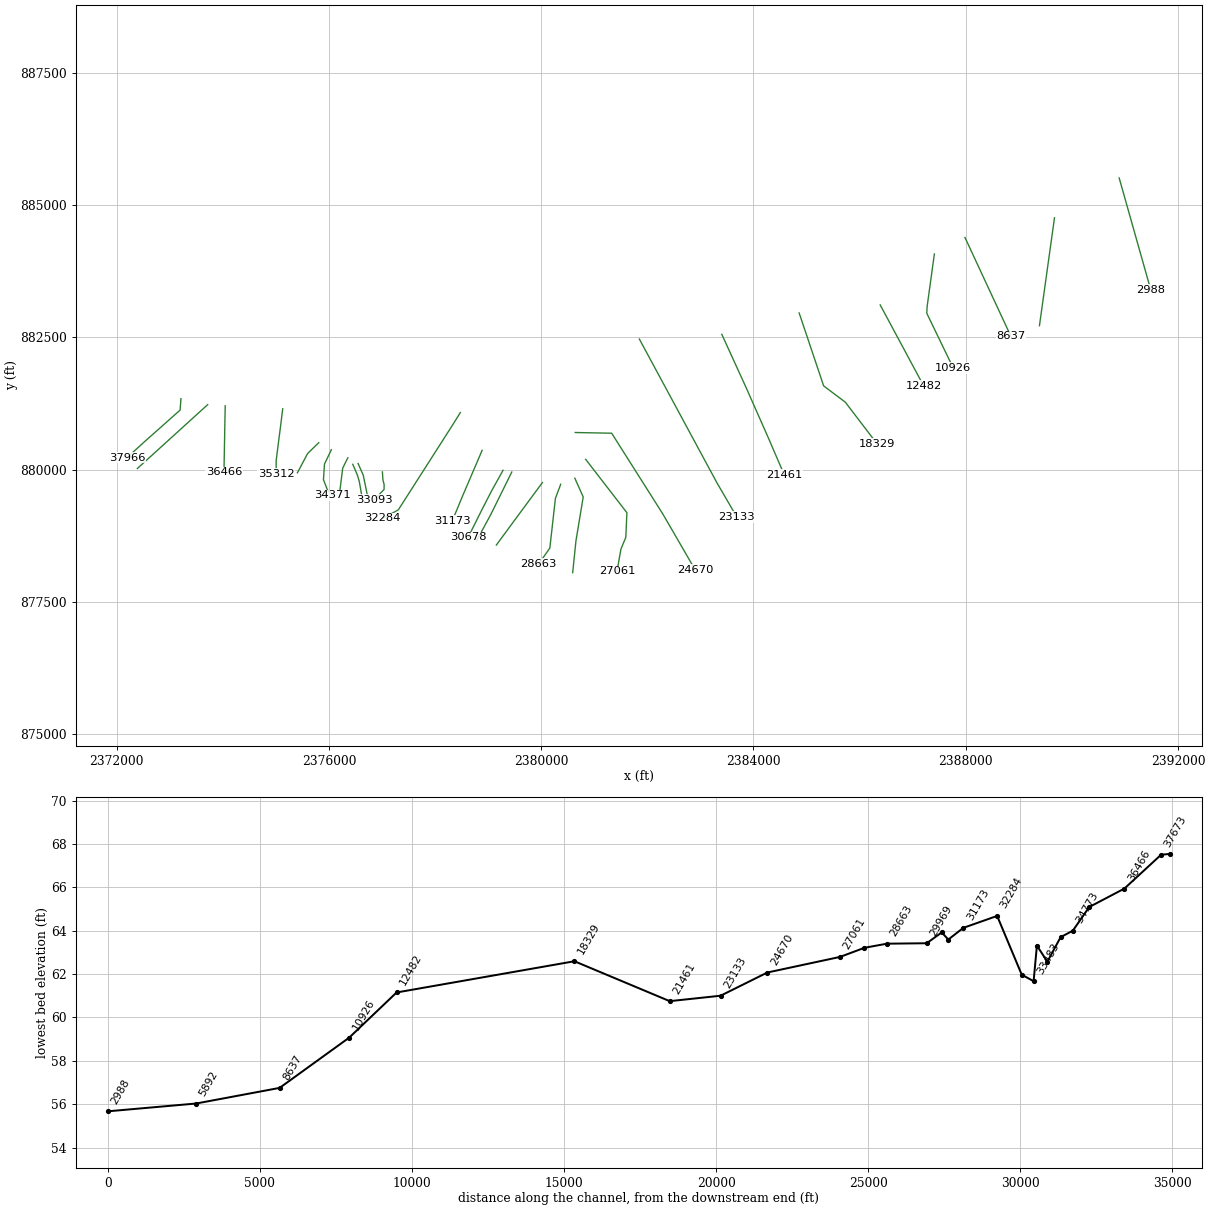
HEC-RAS study HighHillCreek.prj: S-21-356 over High Hill Creek

--- HighHillCreek.g02 (geometry) --- (continued)

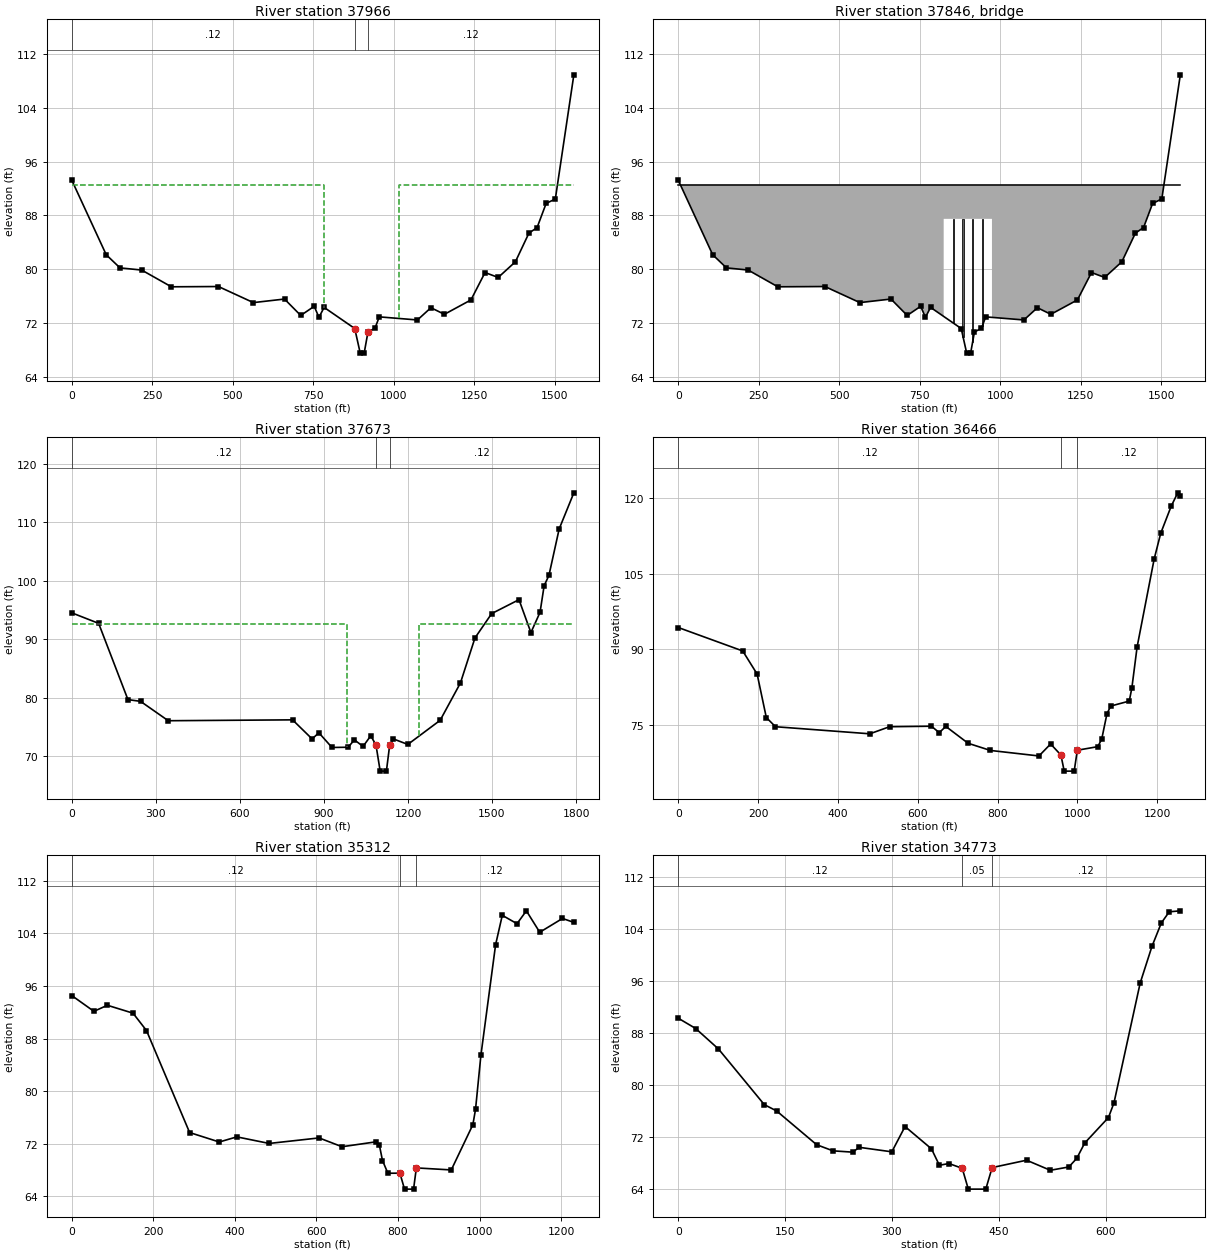
Type RM Length L Ch R = 1 ,37966   ,293.5,293.5,293.5
XS GIS Cut Line= 4
 2373212.5198401881341.6548465152373196.92097123881125.639110115
2372501.97479952880506.9903224492372197.91797148880228.048851198
#Sta/Elev= 30
       0   93.25  107.09   82.16  149.86   80.21  217.15   79.89   309.4    77.4
   455.6   77.44  564.19   75.05  660.84   75.58  711.24   73.14  753.06    74.5
  767.87   72.86  783.84   74.34     879    71.2  896.02   67.54  908.25   67.54
   920.1  70.674  941.98   71.25  955.16   72.93 1073.82   72.47 1115.62   74.29
 1157.53   73.31 1240.04   75.45 1283.72   79.52 1324.65   78.79 1378.06   81.12
 1420.08   85.38 1445.41    86.2 1473.51   89.79 1502.14   90.46 1559.62  108.91
#Mann= 3 ,0,0
       0     .12       0     879     .05       0   920.1     .12       0
#XS Ineff= 2 , 0
       0  782.55    92.6 1016.55       0    92.6
Permanent Ineff=
       F       F
Bank Sta=879,920.1
XS Rating Curve= 0 ,0
Exp/Cntr(USF)=0,0
Exp/Cntr=0.5,0.3

Type RM Length L Ch R = 3 ,37846   ,,,
Bridge Culvert--1,0,-1,-1, 0
Deck Dist Width WeirC Skew NumUp NumDn MinLoCord MaxHiCord MaxSubmerge Is_Ogee
42,145.7,2.6,0, 6, 6, , , 0.98, 0, 2,2,,
       0  824.54  824.55  974.55  974.56 1559.62
    92.6    92.6    92.6    92.6    92.6    92.6
                    87.5    87.5
       0 1035.29  1035.3  1185.3 1185.31 1792.15
    92.6    92.6    92.6    92.6    92.6    92.6
                    87.5    87.5
Pier Skew, UpSta & Num, DnSta & Num=  ,854.55, 2 ,1065.3, 2 , 0 , 0 , 0 ,,
       5       5
    67.5    87.5
       5       5
    67.5    87.5
Pier Skew, UpSta & Num, DnSta & Num=  ,884.55, 2 ,1095.3, 2 , 0 , 0 , 0 ,,
       5       5
    67.5    87.5
       5       5
    67.5    87.5
Pier Skew, UpSta & Num, DnSta & Num=  ,914.55, 2 ,1125.3, 2 , 0 , 0 , 0 ,,
       5       5
    67.5    87.5
       5       5
    67.5    87.5
Pier Skew, UpSta & Num, DnSta & Num=  ,944.55, 2 ,1155.3, 2 , 0 , 0 , 0 ,,
       5       5
    67.5    87.5
       5       5
    67.5    87.5
Abutment Skew #Up #Dn= , 2 , 2
  824.55  844.55
    86.5    66.5
 1035.29  1055.3
    86.5    66.5
Abutment Skew #Up #Dn= , 2 , 2
  954.55  974.55
    66.5    86.5
  1165.3 1185.29
    66.5    86.5
BR Coef=-1 , 0 , 0 ,, 0 ,,,0.8,0,,0,
WSPro=,,,, 1 ,,,, 0 ,,,, 0 ,,,,-1 ,-1 ,-1 , 0 , 0 , 0 , 0 , 0
BC Design=,, 0 ,, 0 ,,,,,,
BC Use User HTab Curves=0
BC User HTab FreeFlow(D)= 0

Type RM Length L Ch R = 1 ,37673   ,1206.5,1206.5,1206.5
XS GIS Cut Line= 2
2373715.94950238881228.2324393712372390.84181334880021.633565704
#Sta/Elev= 30
       0   94.54   95.93   92.74  200.45   79.72  245.47   79.42  344.45   76.11
  788.08   76.26  857.86      73  882.02   74.05  928.86   71.54  986.55   71.58
 1008.73   72.84  1039.8   71.72 1067.21   73.54  1085.971.96136 1100.88    67.5
 1123.05    67.5  1134.771.91929 1148.09      73 1199.55   72.06 1314.93   76.18
 1387.32   82.56 1439.18   90.25 1498.81   94.41 1596.36   96.79 1638.87   91.17
 1671.51   94.63 1686.13   99.18 1703.21  100.93 1739.74  108.87 1792.15  115.04
#Mann= 3 ,0,0
       0     .12       0  1085.9     .05       0  1134.7     .12       0
#XS Ineff= 2 , 0
       0   982.4    92.6  1238.2       0    92.6
Permanent Ineff=
       F       F
Bank Sta=1085.9,1134.7
XS Rating Curve= 0 ,0
Exp/Cntr(USF)=0,0
Exp/Cntr=0.5,0.3

Type RM Length L Ch R = 1 ,36466   ,1154.7,1154.7,1154.7
XS GIS Cut Line= 2
2374046.49470773881206.0258288342374022.99403835879948.740017308
#Sta/Elev= 30
       0   94.34  161.52    89.7  197.62   85.13  220.59   76.54  243.56   74.72
  479.84   73.32  529.21   74.72  634.08   74.82  653.77   73.55  670.18   74.78
  725.97   71.45  781.76   70.03  903.47   68.94  932.72   71.31   958.5   69.12
  966.72   65.94   991.7   65.94   999.6  70.074 1050.86   70.78  1060.7   72.28
 1073.83    77.3 1083.31   78.81 1129.62   79.79 1136.18    82.4 1149.31    90.5
 1191.97  107.86 1208.38  112.96 1234.63  118.32 1251.04  120.97 1257.51  120.35
#Mann= 3 ,0,0
       0     .12       0   958.5     .05       0   999.6     .12       0
Bank Sta=958.5,999.6
XS Rating Curve= 0 ,0
Exp/Cntr(USF)=0,0
Exp/Cntr=0.3,0.1

Type RM Length L Ch R = 1 ,35312   ,539,539,539
XS GIS Cut Line= 4
2375130.22613982881150.9458156392375094.23822683880857.326687737
2375006.70741348880173.6482118342375007.19970881879927.367252335
#Sta/Elev= 30
       0   94.54   54.31   92.14   87.37   93.06  150.18   91.86  183.24   89.22
  289.02    73.7  361.79   72.26  404.79   73.04  484.18   72.04  606.57   72.88
  662.81   71.54  745.51   72.28  754.24   71.84  762.05   69.44  775.28   67.51
   804.8  67.514  816.07   65.09  838.26   65.09   845.1  68.319  930.75   68.01
  983.68   74.89  990.25   77.23 1003.37   85.43 1039.47  102.28 1055.87  106.75
 1091.96  105.47 1114.93  107.43 1147.74  104.17 1203.52  106.27 1231.36  105.67
#Mann= 3 ,0,0
       0     .12       0   804.8     .05       0   845.1     .12       0
Bank Sta=804.8,845.1
XS Rating Curve= 0 ,0
Exp/Cntr(USF)=0,0
Exp/Cntr=0.3,0.1

Type RM Length L Ch R = 1 ,34773   ,401.7,401.7,401.7
XS GIS Cut Line= 3
 2375809.2555984880510.4897835882375598.50002385880303.949320524
2375407.41496958879941.449732288
#Sta/Elev= 30
       0    90.3   24.55   88.71   56.51   85.56  120.82      77  138.14   76.03
  194.33   70.83   217.3   69.89  244.86   69.69  254.25   70.43  299.87   69.74
  318.41   73.63  355.51    70.2  366.63   67.67     380   67.94   398.7  67.203
  407.24      64  431.78      64   440.7  67.316  489.03   68.45  522.41    66.9
  548.38   67.41  559.51   68.74  570.63   71.09  604.01   75.02   611.7   77.26
  648.52   95.71  665.13  101.37   678.2  104.95  689.32  106.67  704.87  106.82
#Mann= 3 ,0,0
       0     .12       0   398.7     .05       0   440.7     .12       0
Bank Sta=398.7,440.7
XS Rating Curve= 0 ,0
Exp/Cntr(USF)=0,0
Exp/Cntr=0.3,0.1

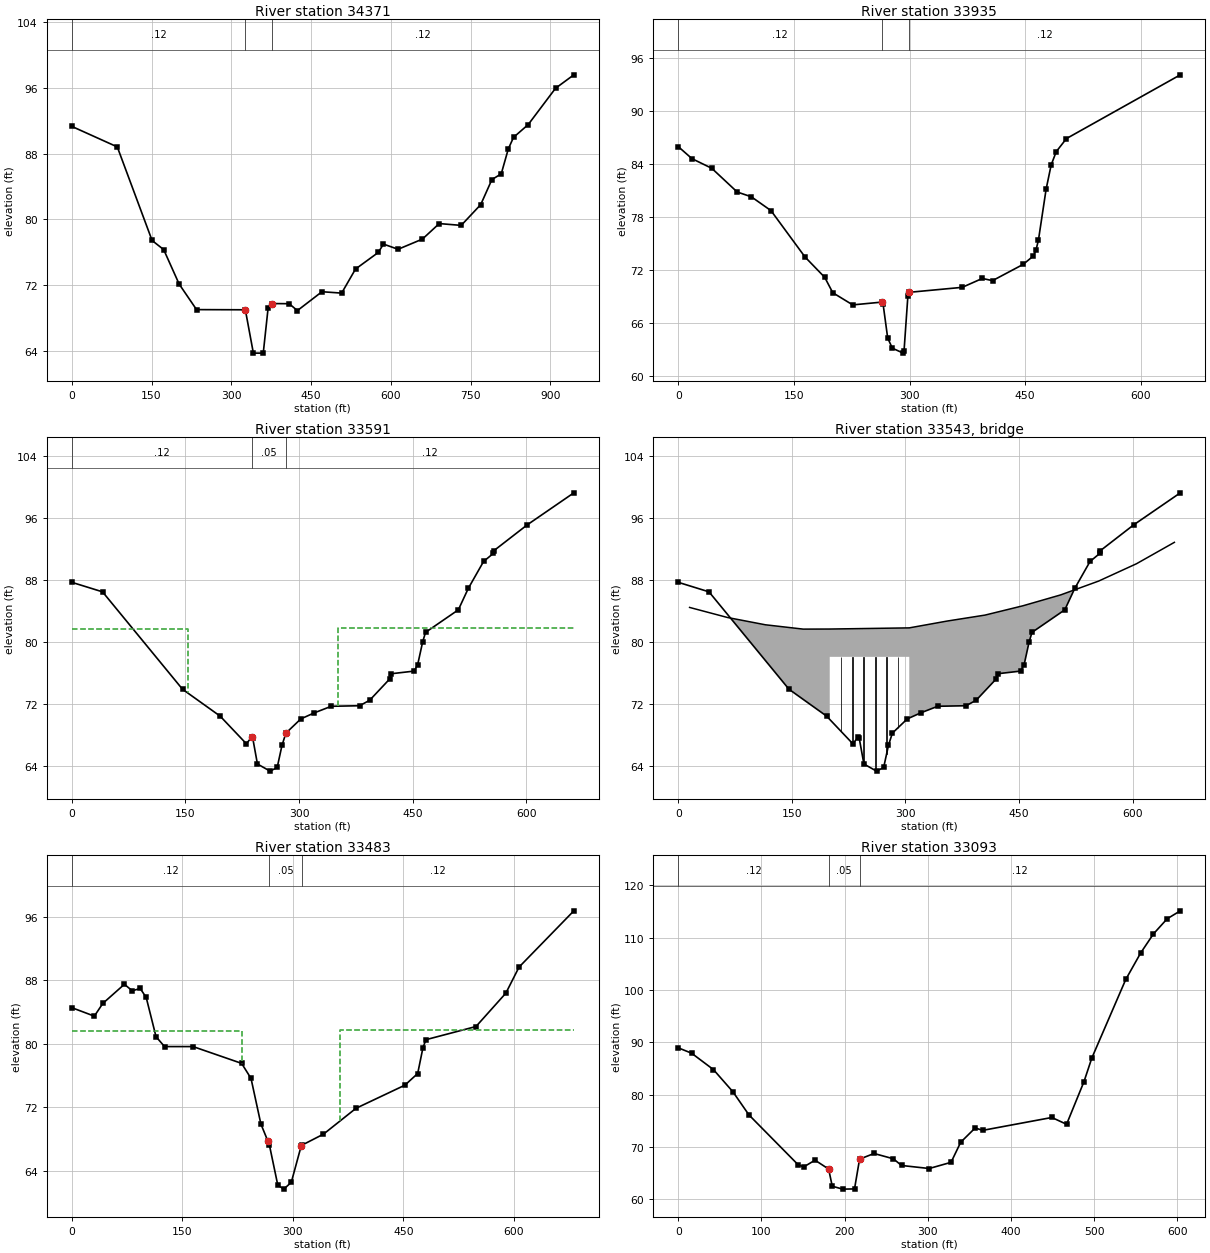
Type RM Length L Ch R = 1 ,34371   ,436.4,436.4,436.4
XS GIS Cut Line= 5
2376046.70687907880377.0112530362375917.44346001880105.839080442
2375897.77293972879810.7812760642375975.04998372879611.265998818
2376070.59251085879517.128508849
#Sta/Elev= 30
       0   91.32   85.62   88.82  151.05   77.42  172.86   76.31  201.94   72.11
  234.65      69  326.42   68.98  341.52    63.7  360.09    63.7  369.17   69.16
   375.7  69.739  408.87   69.72  424.28   68.88  470.53   71.18  507.52   71.01
  533.59   73.94  576.34   75.96   586.2   76.98  613.66   76.35   659.4   77.59
  691.07   79.48  732.34   79.26  769.06   81.79  790.09   84.84  807.68   85.54
  820.92   88.57  830.73   89.98  858.37   91.54  909.74   95.96   944.2    97.6
#Mann= 3 ,0,0
       0     .12       0  326.42     .05       0   375.7     .12       0
Bank Sta=326.42,375.7
XS Rating Curve= 0 ,0
Exp/Cntr(USF)=0,0
Exp/Cntr=0.3,0.1

Type RM Length L Ch R = 1 ,33935   ,343.3,343.3,343.3
XS GIS Cut Line= 3
2376357.22009225880223.8622021932376260.27252795880028.562036438
2376206.88111573879598.620664344
#Sta/Elev= 30
       0   85.99   17.88   84.62   43.52   83.53   76.49   80.84    94.8    80.3
  120.32   78.73   164.4   73.48  190.05   71.16  200.46   69.42  226.35   68.04
  264.65   68.36  265.65   68.19   271.7   64.28  277.73   63.13  291.85   62.57
  292.86   62.76   297.9   69.06  298.91   69.46  368.38   70.03  394.46   71.04
  407.69   70.79  447.36   72.63  460.59   73.58  463.89   74.21   467.2   75.36
   477.2   81.16  483.73    83.9  490.34   85.42  503.57    86.9  651.28   94.13
#Mann= 3 ,0,0
       0     .12       0  264.65     .05       0  298.91     .12       0
Bank Sta=264.65,298.91
XS Rating Curve= 0 ,0
Exp/Cntr(USF)=0,0
Exp/Cntr=0.5,0.3

Type RM Length L Ch R = 1 ,33591   ,108.3,108.3,108.3
XS GIS Cut Line= 4
2376449.95254505 880101.623968952376535.65981204879902.108691704
2376573.59581546879774.2503098072376626.98722768879466.547170956
#Sta/Elev= 30
       0   87.68   40.61   86.45  146.18   73.88  195.86   70.41   230.5   66.84
   237.8   67.74  238.84   67.61   245.1   64.23  261.79   63.31  271.18   63.78
  277.51   66.63  282.65   68.21  302.36   70.05  320.14   70.83  342.56   71.68
  379.99   71.75  393.31   72.46  419.95   75.23  421.75   75.88  451.91   76.22
  456.58   77.03  463.24      80  467.04   81.22  510.33   84.13  523.49    86.9
  543.64   90.37  556.64   91.42  556.95   91.74  601.19   95.09  662.81   99.23
#Mann= 3 ,0,0
       0     .12       0   237.8     .05       0  282.65     .12       0
#XS Ineff= 2 , 0
             153   81.64     352            81.8
Permanent Ineff=
       F       F
Bank Sta=237.8,282.65
XS Rating Curve= 0 ,0
Exp/Cntr(USF)=0,0
Exp/Cntr=0.5,0.3

Type RM Length L Ch R = 3 ,33543   ,,,
Bridge Culvert--1,0,-1,-1, 0
Deck Dist Width WeirC Skew NumUp NumDn MinLoCord MaxHiCord MaxSubmerge Is_Ogee
47,33,2.6,0, 15, 15, , , 0.98, 0, 2,2,,
      15      65     115     165     200     200     305     305     355     405
     455     505     555     605     655
  84.438   83.14    82.2   81.64   81.65   81.65    81.8    81.8   82.68   83.45
   84.65   86.06   87.84   90.08   92.84
                                           78.06   78.06
                                        
      60     110     160     210     245     245     350     350     400     450
     500     550     600     650     700
  84.438   83.14    82.2   81.64   81.65   81.65    81.8    81.8   82.68   83.45
   84.65   86.06   87.84   90.08   92.84
                                           79.63   79.63
                                        
Pier Skew, UpSta & Num, DnSta & Num=  ,215, 2 ,260, 2 , 0 , 0 , 0 ,,
       1       1
       0      80
       1       1
       0      80
Pier Skew, UpSta & Num, DnSta & Num=  ,230, 2 ,275, 2 , 0 , 0 , 0 ,,
       1       1
       0      80
       1       1
       0      80
Pier Skew, UpSta & Num, DnSta & Num=  ,245, 2 ,290, 2 , 0 , 0 , 0 ,,
       1       1
       0      80
       1       1
       0      80
Pier Skew, UpSta & Num, DnSta & Num=  ,260, 2 ,305, 2 , 0 , 0 , 0 ,,
       1       1
       0      80
       1       1
       0      80
Pier Skew, UpSta & Num, DnSta & Num=  ,275, 2 ,320, 2 , 0 , 0 , 0 ,,
       1       1
       0      80
       1       1
       0      80
Pier Skew, UpSta & Num, DnSta & Num=  ,290, 2 ,335, 2 , 0 , 0 , 0 ,,
       1       1
       0      80
       1       1
       0      80
Abutment Skew #Up #Dn= , 2 , 2
  199.99     220
      74      54
  244.99     265
      74      54
Abutment Skew #Up #Dn= , 2 , 2
     285  305.01
      54      74
     330  350.01
      54      74
BR Coef=-1 , 0 , 0 ,, 0 ,,,0.8,0,,0,
WSPro=,,,, 1 ,,,, 0 ,,,, 0 ,,,,-1 ,-1 ,-1 , 0 , 0 , 0 , 0 , 0
BC Design=,, 0 ,, 0 ,,,,,,
BC Use User HTab Curves=0
BC User HTab FreeFlow(D)= 0

Type RM Length L Ch R = 1 ,33483   ,390.5,390.5,390.5
XS GIS Cut Line= 3
2376550.93006877880115.6743405872376647.87763307879895.083505886
2376736.39497438879463.737096629
#Sta/Elev= 30
       0   84.57   30.61    83.5   42.18   85.11    71.4   87.52    82.1    86.7
   92.85   86.99     101   85.86  114.36    80.9   125.9   79.66  164.54   79.66
  230.47   77.54  243.23   75.64  256.62   69.89   266.267.70566  268.29   67.19
  279.52   62.19  287.68   61.67  297.89   62.53   311.2  67.084  312.18   67.21
  341.58   68.61  385.68   71.87  452.04   74.79  469.39   76.26  476.54   79.52
  480.62   80.53   548.5   82.19  589.02    86.4  606.93   89.69  681.29   96.79
#Mann= 3 ,-1,0
       0     .12       0  268.29     .05       0  312.18     .12       0
#XS Ineff= 2 , 0
          230.85   81.64  364.15            81.8
Permanent Ineff=
       F       F
Bank Sta=266.2,311.2
XS Rating Curve= 0 ,0
Exp/Cntr(USF)=0,0
Exp/Cntr=0.5,0.3

Type RM Length L Ch R = 1 ,33093   ,808.6,808.6,808.6
XS GIS Cut Line= 5
2377008.50454103879958.0559154192377018.14609691879810.829401343
2377040.95607306879718.3072385062377039.60608759879626.166422496
 2376854.6032482879431.421241863
#Sta/Elev= 30
       0   88.97   16.01   87.95   42.32   84.81   65.69   80.58   85.07   76.14
  144.25   66.61  150.92   66.22  164.44    67.5   180.8   65.81  185.15   62.53
  197.65   61.97  211.93   62.01     218    67.7   235.4   68.78  258.59   67.77
  268.43   66.49  301.71   65.91  327.96   67.09   339.6   70.93  356.98   73.66
  366.03    73.2  449.17   75.66  466.87   74.36  487.76    82.5  497.27   87.04
     538  102.03   556.1  107.14  571.31  110.74  587.78  113.63   603.6  115.15
#Mann= 3 ,0,0
       0     .12       0   180.8     .05       0     218     .12       0
Bank Sta=180.8,218
XS Rating Curve= 0 ,0
Exp/Cntr(USF)=0,0
Exp/Cntr=0.3,0.1

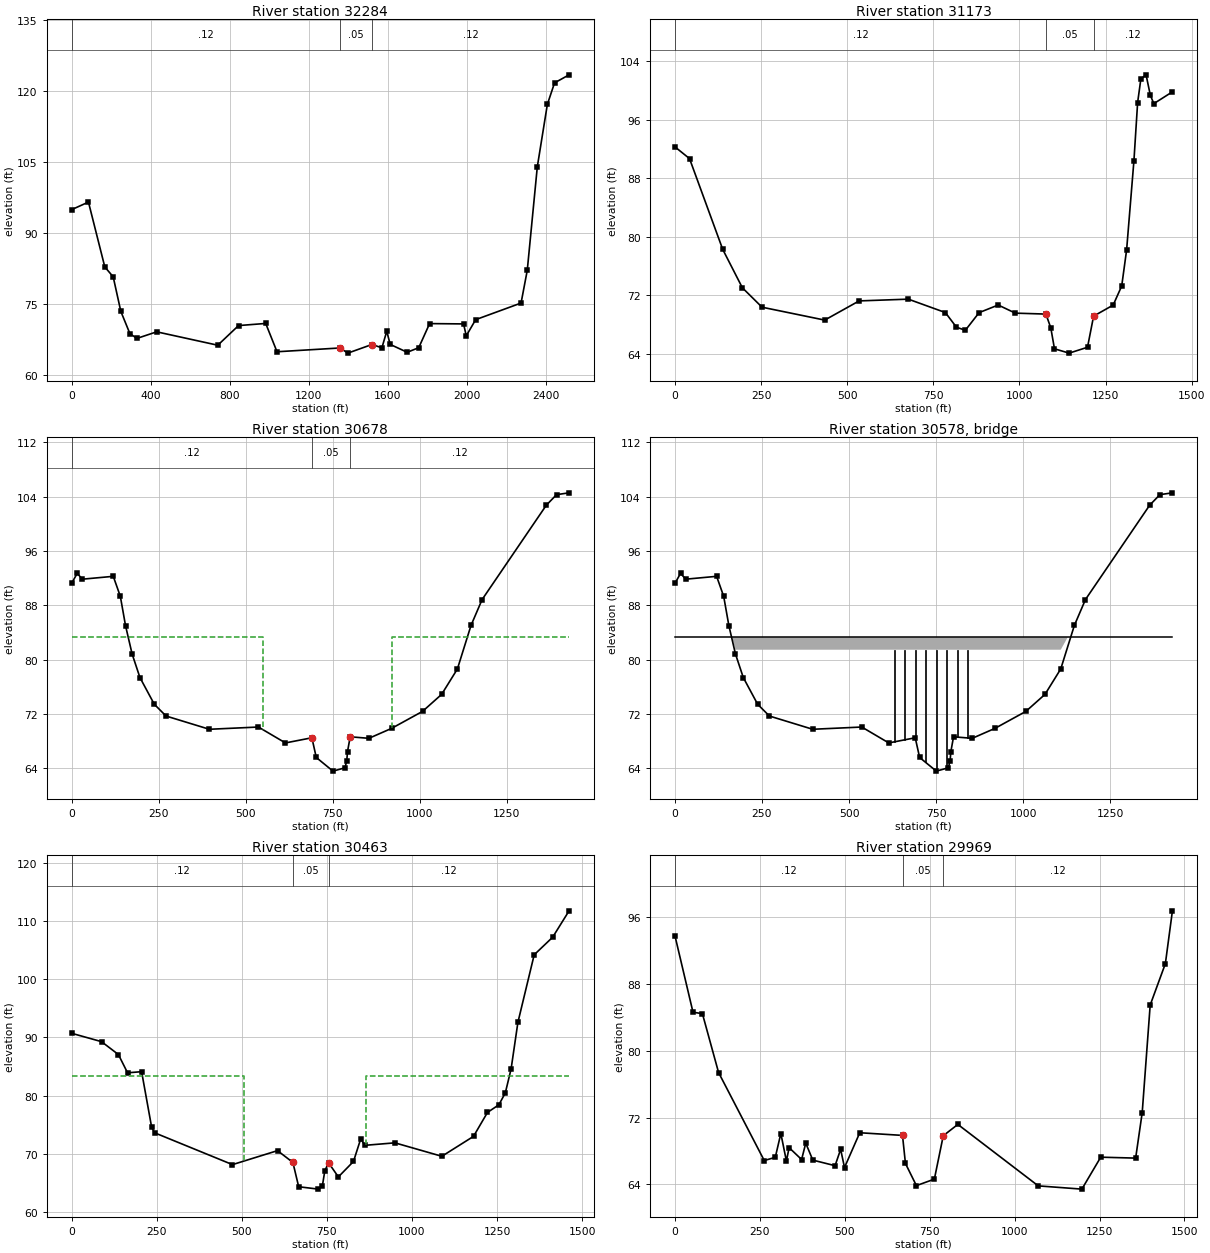
Type RM Length L Ch R = 1 ,32284   ,1110.6,1110.6,1110.6
XS GIS Cut Line= 5
2378476.81670447 881079.268953852378335.51685215880850.873984928
2377308.64001248879241.0463631552377161.40355795879159.727810899
2377011.93256069879079.062642513
#Sta/Elev= 30
       0   94.98   85.54   96.59  168.17   82.89  210.61    80.8  249.19    73.5
  295.21   68.79  330.75   67.79  430.65   69.18  739.55   66.35  844.47    70.5
  981.92   70.95 1039.06   64.97 1358.19   65.77 1397.11   64.68 1518.92    66.5
 1569.56   65.81 1593.97   69.29 1611.59   66.52 1697.33   64.86 1755.71   65.82
 1810.79   70.92 1982.57   70.85 1996.13   68.34  2043.7   71.75 2273.28   75.26
 2304.67   82.18  2355.4  104.03 2406.21  117.22 2442.58  121.77 2516.07  123.47
#Mann= 3 ,-1,0
       0     .12       0 1358.19     .05       0 1518.92     .12       0
Bank Sta=1358.19,1518.92
XS Rating Curve= 0 ,0
Exp/Cntr(USF)=0,0
Exp/Cntr=0.3,0.1

Type RM Length L Ch R = 1 ,31173   ,495.4,495.4,495.4
XS GIS Cut Line= 3
2378887.56100561880365.0157456882378519.33786266 879503.07881566
2378325.88470185879034.505597676
#Sta/Elev= 30
       0    92.3    42.5   90.69   138.8    78.3   195.9   73.05     253    70.4
   434.9   68.64   534.8   71.26   677.6    71.5   785.1   69.67   817.2   67.67
   843.1   67.25   883.1   69.66   938.5    70.7   988.2   69.59 1076.96  69.462
  1091.2   67.57  1101.8   64.72  1144.4   64.13  1197.7   64.93  1215.4   69.18
  1272.2   70.69    1297    73.3  1311.2   78.21  1332.5   90.43  1343.2   98.35
  1352.6  101.57  1367.7  102.13  1380.2   99.32  1390.3    98.2  1444.2   99.81
#Mann= 3 ,0,0
       0     .12       0 1076.96     .05       0  1215.4     .12       0
Bank Sta=1076.96,1215.4
XS Rating Curve= 0 ,0
Exp/Cntr(USF)=0,0
Exp/Cntr=0.5,0.3

Type RM Length L Ch R = 1 ,30678   ,214.9,214.9,214.9
XS GIS Cut Line= 4
2379281.99773163879989.0942886692379068.23534688879603.404517152
2378890.26439385879257.0826626052378623.90770797 878721.59280094
#Sta/Elev= 30
       0   91.21    16.2   92.69    31.2   91.84   119.8   92.26   140.1   89.31
     155      85   173.8   80.85   196.3   77.37   237.6   73.43   271.3    71.7
   395.7   69.75   536.6   70.08   614.1   67.74     69068.49918   702.6    65.6
   750.6   63.59     785   64.08  790.17   65.12   792.3   66.47     80068.64063
   853.7   68.42   918.8   69.88  1007.6   72.38  1062.6   74.89  1107.8   78.63
  1146.9   85.04  1178.8   88.85  1363.1  102.73  1392.4  104.28  1428.4  104.55
#Mann= 3 ,0,0
       0     .12       0     690     .05       0     800     .12       0
#XS Ineff= 2 , 0
       0     550   83.29     920       0   83.29
Permanent Ineff=
       F       F
Bank Sta=690,800
XS Rating Curve= 0 ,0
Exp/Cntr(USF)=0,0
Exp/Cntr=0.5,0.3

Type RM Length L Ch R = 3 ,30578   ,,,
Bridge Culvert--1,0,-1,-1, 0
Deck Dist Width WeirC Skew NumUp NumDn MinLoCord MaxHiCord MaxSubmerge Is_Ogee
50,77,2.6,0, 6, 6, , , 0.98, 0, 0,0,,
       0  599.99     600     870  870.01  1428.4
   83.29   83.29   83.29   83.29   83.29   83.29
   81.46           81.46   81.46           81.46
       0  549.99     550     820  820.01  1428.4
   83.29   83.29   83.29   83.29   83.29   83.29
   81.46           81.46   81.46           81.46
Pier Skew, UpSta & Num, DnSta & Num=  ,630, 2 ,580, 2 , 0 , 0 , 0 ,,
       3       3
   63.59   81.46
       3       3
   63.59   81.46
Pier Skew, UpSta & Num, DnSta & Num=  ,660, 2 ,610, 2 , 0 , 0 , 0 ,,
       3       3
   63.59   81.46
       3       3
   63.59   81.46
Pier Skew, UpSta & Num, DnSta & Num=  ,690, 2 ,640, 2 , 0 , 0 , 0 ,,
       3       3
   63.59   81.46
       3       3
   63.59   81.46
Pier Skew, UpSta & Num, DnSta & Num=  ,720, 2 ,670, 2 , 0 , 0 , 0 ,,
       3       3
   63.59   81.46
       3       3
   63.59   81.46
Pier Skew, UpSta & Num, DnSta & Num=  ,750, 2 ,700, 2 , 0 , 0 , 0 ,,
       3       3
   63.59   81.46
       3       3
   63.59   81.46
Pier Skew, UpSta & Num, DnSta & Num=  ,780, 2 ,730, 2 , 0 , 0 , 0 ,,
       3       3
   63.59   81.46
       3       3
   63.59   81.46
Pier Skew, UpSta & Num, DnSta & Num=  ,810, 2 ,760, 2 , 0 , 0 , 0 ,,
       3       3
   63.59   81.46
       3       3
   63.59   81.46
Pier Skew, UpSta & Num, DnSta & Num=  ,840, 2 ,790, 2 , 0 , 0 , 0 ,,
       3       3
   63.59   81.46
       3       3
   63.59   81.46
Abutment Skew #Up #Dn= , 2 , 2
     600     620
    80.5    60.5
     550     570
    80.5    60.5
Abutment Skew #Up #Dn= , 2 , 2
     850     870
    60.5    80.5
     800     820
    60.5    80.5
BR Coef=-1 , 0 , 0 ,, 0 ,,,0.8,0,,0,
WSPro=,,,, 1 ,,,, 0 ,,,, 0 ,,,,-1 ,-1 ,-1 , 0 , 0 , 0 , 0 , 0
BC Design=83.29,81.46, 0 ,, 0 ,,10,600,550,30,3
BC Use User HTab Curves=0
BC User HTab FreeFlow(D)= 0

Type RM Length L Ch R = 1 ,30463   ,494.2,494.2,494.2
XS GIS Cut Line= 3
2379446.63493058879956.1584166682379050.17211358879152.287508376
2378782.07235233878654.236461969
#Sta/Elev= 30
       0   90.69    88.1   89.25   137.6   87.04   164.6    83.9   205.9   84.09
   235.2    74.6   243.9    73.6   472.9   68.13   605.2   70.53 650.363 68.5068
   667.4   64.33   725.2   63.92   736.9   64.44   744.2   67.06755.1229 68.4464
     784   66.02   828.4   68.67   849.9   72.59   861.3   71.44   950.1   71.87
  1088.1   69.56  1181.1   72.98  1222.1   77.09  1255.7   78.41  1274.6   80.46
  1291.6   84.58  1311.5   92.55  1359.4  104.17  1413.7  107.19  1461.9  111.72
#Mann= 3 ,0,0
       0     .12       0 650.363     .05       0755.1229     .12       0
#XS Ineff= 2 , 0
       0  506.05   83.29  863.95       0   83.29
Permanent Ineff=
       F       F
Bank Sta=650.363,755.1229
XS Rating Curve= 0 ,0
Exp/Cntr(USF)=0,0
Exp/Cntr=0.5,0.3

Type RM Length L Ch R = 1 ,29969   ,1306.1,1306.1,1306.1
XS GIS Cut Line= 3
2380023.32534268879756.4374891722379380.38523308878882.616143208
2379155.91736439878576.377836641
#Sta/Elev= 30
       0   93.83    53.3   84.63      81   84.46   128.6    77.4     263   66.85
   295.5   67.23   311.9   70.09   328.2    66.8   336.3   68.39     373   66.97
   385.2   68.93     406    66.9   471.5   66.23   487.9   68.19   499.3   66.01
   544.2   70.18     670  69.862  678.65    66.5   710.9   63.84  763.82   64.62
     790  69.823   832.9   71.18  1069.6   63.81    1198   63.42  1253.5   67.25
  1356.3   67.14  1375.6   72.59  1399.1   85.49  1443.8   90.461464.561   96.79
#Mann= 3 ,0,0
       0     .12       0     670     .05       0     790     .12       0
Bank Sta=670,790
XS Rating Curve= 0 ,0
Exp/Cntr(USF)=0,0
Exp/Cntr=0.3,0.1

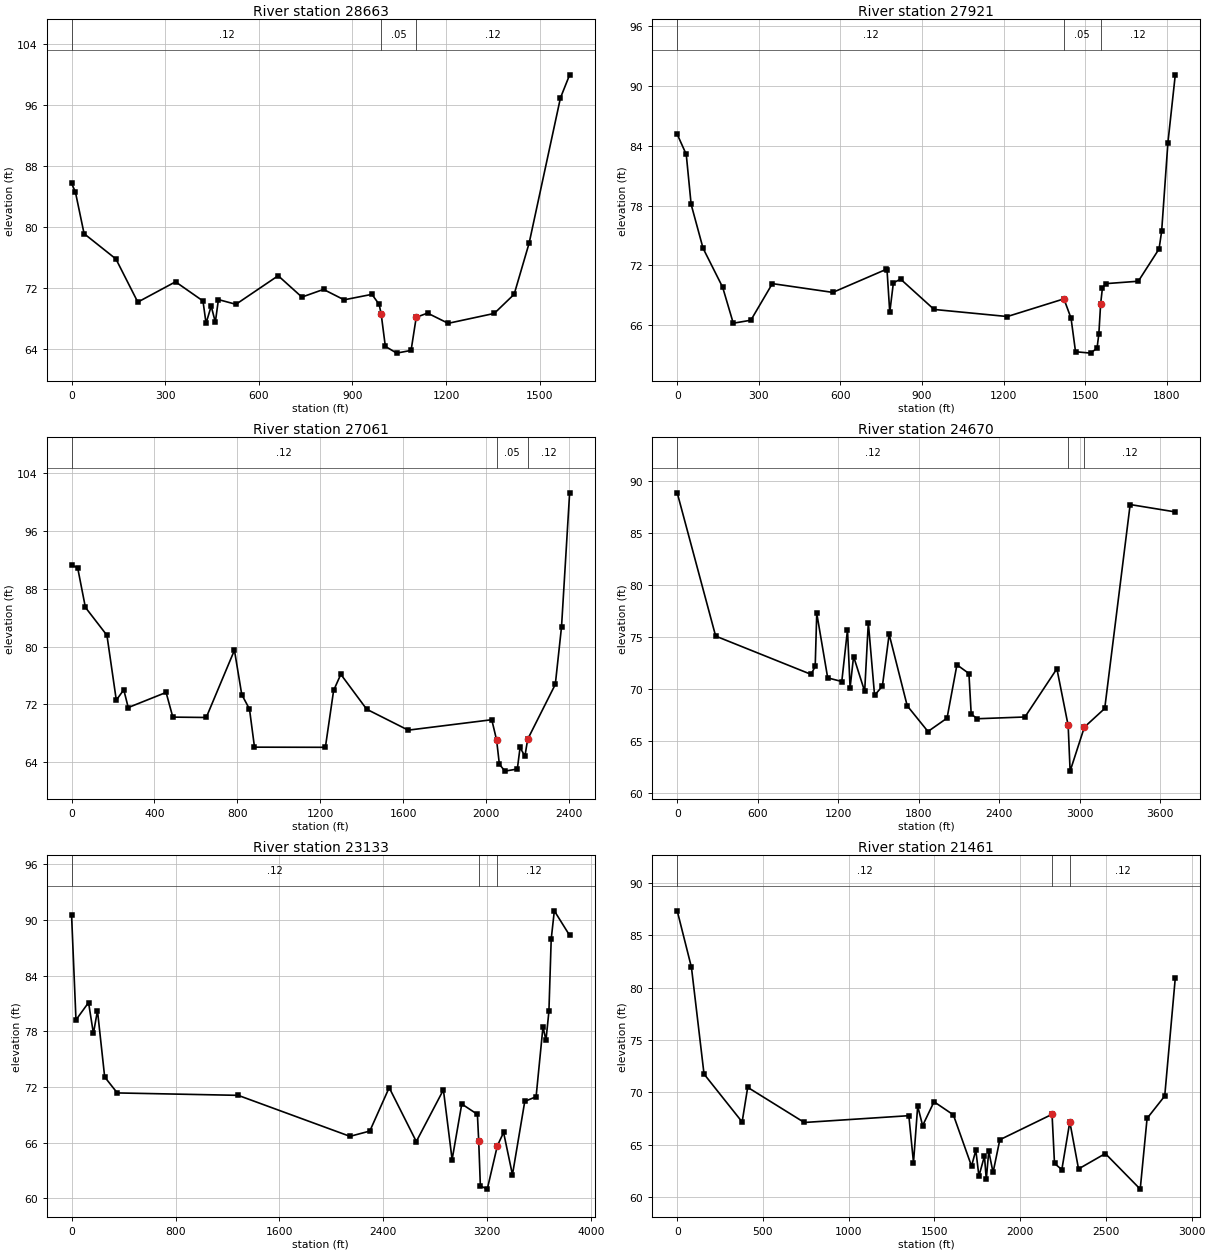
Type RM Length L Ch R = 1 ,28663   ,741.9,741.9,741.9
XS GIS Cut Line= 4
2380367.77677556879723.7515792642380268.33225671 879456.94487842
2380163.33764345878519.1279782452379953.12372149878217.554695363
#Sta/Elev= 30
       0   85.71   12.12   84.62   40.13   79.11  142.17   75.78   212.2   70.11
  333.12   72.78  421.04   70.26  430.95   67.33  447.46   69.58  460.66   67.47
  470.57   70.44  526.69   69.82  662.06   73.58  737.99   70.77  807.33   71.78
  873.36   70.41   962.5   71.13  985.61   69.81  992.14   68.53 1005.42   64.29
 1041.74    63.4 1087.96   63.76 1104.47   68.12 1140.79   68.66 1206.82   67.32
 1354.43   68.62 1418.23   71.14 1466.22   77.87 1566.54   96.96 1596.02     100
#Mann= 3 ,-1,0
       0     .12       0  992.14     .05       0 1104.47     .12       0
Bank Sta=992.14,1104.47
XS Rating Curve= 0 ,0
Exp/Cntr(USF)=0,0
Exp/Cntr=0.3,0.1

Type RM Length L Ch R = 1 ,27921   ,800.6,800.6,800.6
XS GIS Cut Line= 4
2380634.88804295879837.9077336212380792.25679347879484.615096819
2380655.32592169878654.0922449482380593.96345318878054.323601099
#Sta/Elev= 30
       0   85.16   33.23   83.14   51.19   78.13      95   73.73  167.07   69.82
  206.15   66.21   270.8   66.51  349.83   70.18  572.04    69.3  768.24   71.61
  771.56   71.52  781.54    67.3  794.84   70.26  821.44   70.63  944.48   67.59
 1213.84   66.881421.883   68.65 1448.13   66.71 1464.62   63.35 1520.38   63.21
 1543.78   63.72 1550.38   65.151556.973  68.161 1563.57   69.76 1576.76   70.18
  1695.5   70.42 1771.71   73.66 1781.25   75.43 1804.34   84.33 1831.39   91.12
#Mann= 3 ,-1,0
       0     .12       01421.883     .05       01556.973     .12       0
Bank Sta=1421.883,1556.973
XS Rating Curve= 0 ,0
Exp/Cntr(USF)=0,0
Exp/Cntr=0.3,0.1

Type RM Length L Ch R = 1 ,27061   ,2391.4,2391.4,2391.4
XS GIS Cut Line= 5
2380838.76893437880195.038226716 2381615.6353116879186.501931037
2381594.98226552878720.7848632632381503.11622156878500.097346199
2381429.28479874878082.035683653
#Sta/Elev= 30
       0   91.25   29.39   90.88   66.66   85.41  170.64   81.55  215.77    72.6
  251.86   74.02  273.36   71.57  455.98   73.66  488.44   70.25  649.74    70.2
  785.71   79.49  821.04   73.36  858.31   71.36  882.49    66.1 1224.44   66.08
 1264.19   73.93 1298.87   76.16 1423.67   71.34 1624.02   68.45 2027.12   69.89
2050.444  67.089 2063.77   63.75 2090.42   62.79 2150.39   63.08 2163.72   66.06
 2187.05   64.842200.374  67.191 2333.65   74.77 2363.63   82.71  2402.8  101.23
#Mann= 3 ,-1,0
       0     .12       02050.444     .05       02200.374     .12       0
Bank Sta=2050.444,2200.374
XS Rating Curve= 0 ,0
Exp/Cntr(USF)=0,0
Exp/Cntr=0.3,0.1

Type RM Length L Ch R = 1 ,24670   ,1537,1537,1537
XS GIS Cut Line= 4
2380640.56690893880702.1806822952381328.57436456880688.793700695
2382290.15371061879166.2218328322382901.88334896878108.474907278
#Sta/Elev= 30
       0    88.9  286.33   75.09  996.96    71.4 1028.01   72.16 1039.65   77.29
 1121.14   71.06 1226.18   70.71 1268.61   75.69 1288.01   70.11 1314.03   73.12
 1396.67   69.76 1423.84   76.39 1470.41   69.38 1528.62   70.26 1579.07   75.26
 1713.62   68.37 1868.23   65.89 2010.37   67.18  2084.1   72.32 2173.35   71.48
 2190.34   67.57 2235.45   67.12  2590.9   67.29 2828.84   71.942912.691  66.472
 2927.39   62.073033.511   66.31 3185.13   68.11 3374.64   87.77 3710.83   87.06
#Mann= 3 ,-1,0
       0     .12       02912.691     .05       03033.511     .12       0
Bank Sta=2912.691,3033.511
XS Rating Curve= 0 ,0
Exp/Cntr(USF)=0,0
Exp/Cntr=0.3,0.1

Type RM Length L Ch R = 1 ,23133   ,1671.8,1671.8,1671.8
XS GIS Cut Line= 3
2381849.49831392882468.8855487422383305.00756306879764.490505228
2383687.19139872879104.668215656
#Sta/Elev= 30
       0   90.54   33.92   79.24   130.8   81.11  168.06   77.78  199.38   80.24
  254.77   73.09   351.7   71.37 1282.18   71.11 2142.93   66.69  2295.7   67.26
 2444.74   71.94 2653.41   66.13 2862.07    71.7 2929.14   64.18 3003.34   70.18
 3123.82   69.06 3133.81   66.19 3146.57   61.35 3199.64      61 3277.26   65.67
 3325.31   67.11 3393.56   62.55 3488.36   70.46 3575.57   70.96 3628.65   78.51
  3651.4   77.04 3674.15   80.15 3691.85   87.95 3715.86      91 3833.71   88.35
#Mann= 3 ,-1,0
       0     .12       0 3133.81     .05       0 3277.26     .12       0
Bank Sta=3133.81,3277.26
XS Rating Curve= 0 ,0
Exp/Cntr(USF)=0,0
Exp/Cntr=0.3,0.1

Type RM Length L Ch R = 1 ,21461   ,3132.3,3132.3,3132.3
XS GIS Cut Line= 4
2383403.76462963882557.2133575992383873.14596332881525.606967196
2384283.57575879880593.8006116932384580.68829309879901.898321468
#Sta/Elev= 30
       0   87.35   82.99   81.95  156.39   71.75  378.59   67.17  411.03   70.48
  741.09   67.12  1350.7   67.77 1377.94   63.29 1402.36   68.68 1431.21   66.82
  1497.7    69.1 1610.42   67.85 1716.41   62.95  1741.5   64.47 1759.43   61.99
  1791.7   63.91 1802.45   61.68 1816.79   64.38 1841.89   62.34 1881.33   65.47
 2185.94    67.9 2200.23    63.2 2243.08   62.62  2289.5   67.18 2340.39   62.68
 2496.61   64.15 2700.15   60.75 2740.09   67.51 2842.98   69.65 2904.56   80.93
#Mann= 3 ,-1,0
       0     .12       0 2185.94     .05       0  2289.5     .12       0
Bank Sta=2185.94,2289.5
XS Rating Curve= 0 ,0
Exp/Cntr(USF)=0,0
Exp/Cntr=0.3,0.1

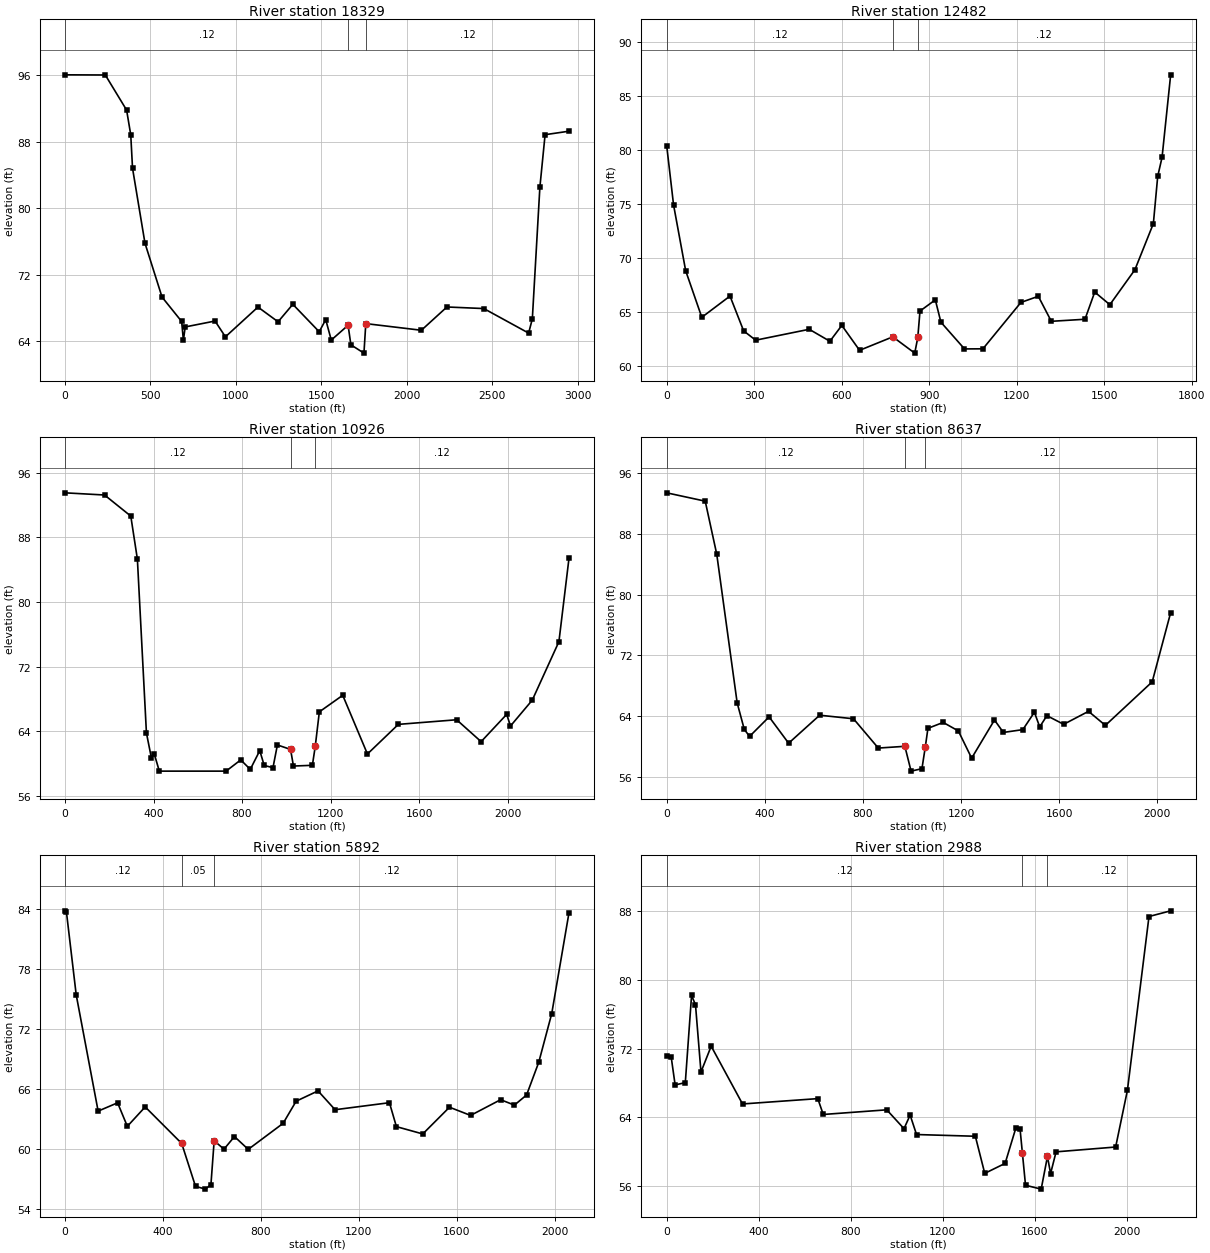
Type RM Length L Ch R = 1 ,18329   ,5846.5,5846.5,5846.5
XS GIS Cut Line= 4
2384861.08884799882961.2116369842385322.65978337 881583.18826467
2385730.71524799881275.474307745 2386326.0748603880492.810547741
#Sta/Elev= 30
       0   96.06   235.8   96.04   360.4   91.82   384.6   88.85     395   84.83
   467.7   75.82   567.6   69.33   682.2    66.4   692.6   64.13     703   65.74
   877.6   66.45   938.3   64.55  1128.6   68.13  1246.2   66.36  1332.6   68.46
  1486.9   65.16    1525   66.62  1557.4   64.16  1655.8   65.94  1672.2   63.59
  1748.5   62.59  1759.4   66.14  2084.4   65.34  2233.9   68.14  2449.7   67.95
  2711.7      65  2733.4   66.71  2777.5   82.54    2808   88.862947.715   89.28
#Mann= 3 ,0,0
       0     .12       0  1655.8     .05       0  1759.4     .12       0
Bank Sta=1655.8,1759.4
XS Rating Curve= 0 ,0
Exp/Cntr(USF)=0,0
Exp/Cntr=0.3,0.1

Type RM Length L Ch R = 1 ,12482   ,1556,1556,1556
XS GIS Cut Line= 2
2386388.22568789883112.7701817712387203.92517011881589.386217271
#Sta/Elev= 30
       0   80.39    23.6   74.89    65.1   68.79   120.4   64.47   217.1   66.44
   263.9   63.21   305.1   62.35   488.8   63.36   559.6   62.25   600.5   63.72
   661.4   61.41   775.3   62.66   850.5   61.15     861    62.6   868.5   65.05
   921.1   66.09   940.2   64.02  1021.1   61.54  1084.3   61.55  1214.6   65.85
  1274.2   66.42  1318.8    64.1  1434.2   64.29  1467.7   66.81  1519.5   65.64
  1605.4   68.88  1668.7   73.16  1683.6   77.54  1698.5    79.31728.023   86.95
#Mann= 3 ,0,0
       0     .12       0   775.3     .05       0     861     .12       0
Bank Sta=775.3,861
XS Rating Curve= 0 ,0
Exp/Cntr(USF)=0,0
Exp/Cntr=0.3,0.1

Type RM Length L Ch R = 1 ,10926   ,2289.3,2289.3,2289.3
XS GIS Cut Line= 4
2387409.09703967884075.5545618532387272.55723904883082.227512276
2387265.73024901882955.928196694 2387764.1005213881921.639206928
#Sta/Elev= 30
       0   93.53   178.7   93.26   297.3   90.65   327.1   85.32     368   63.79
   390.1   60.75     403   61.24   426.2   59.07   727.9   59.07   794.1   60.46
   837.2   59.29   880.2   61.61   900.1   59.77   939.8    59.5   959.7   62.31
  1019.2   61.76  1032.3    59.7  1117.8   59.79  1130.7   62.12  1149.3   66.41
    1255   68.46  1366.6   61.19  1506.3   64.86  1769.7   65.43  1880.3   62.72
  1995.8    66.1    2013   64.66  2111.4   67.86  2231.8    75.12277.248   85.41
#Mann= 3 ,0,0
       0     .12       0  1019.2     .05       0  1130.7     .12       0
Bank Sta=1019.2,1130.7
XS Rating Curve= 0 ,0
Exp/Cntr(USF)=0,0
Exp/Cntr=0.3,0.1

Type RM Length L Ch R = 1 ,8637    ,2745.2,2745.2,2745.2
XS GIS Cut Line= 2
2387985.97769732884386.182608285 2388849.5919363882522.414329696
#Sta/Elev= 30
       0   93.43   157.1   92.33   204.1   85.33   287.3   65.74   316.3   62.25
   337.9   61.33   417.5    63.9     497   60.43   623.6   64.12   761.4   63.65
   862.5   59.79   970.8   60.02   996.1   56.75  1040.4   57.07  1053.9    59.9
  1064.8   62.39  1126.9   63.17  1188.7   62.05    1243   58.46    1336   63.49
  1372.2   61.85  1451.7   62.22  1498.7   64.51  1520.4   62.58  1549.7   64.06
  1618.1   62.92  1719.3   64.63    1788   62.78  1978.9   68.522054.133   77.64
#Mann= 3 ,0,0
       0     .12       0   970.8     .05       0  1053.9     .12       0
Bank Sta=970.8,1053.9
XS Rating Curve= 0 ,0
Exp/Cntr(USF)=0,0
Exp/Cntr=0.3,0.1

Type RM Length L Ch R = 1 ,5892    ,2903.6,2903.6,2903.6
XS GIS Cut Line= 2
 2389672.2442351884758.2535649992389388.92414879882720.397040608
#Sta/Elev= 30
       0   83.82     6.1   83.66    45.8   75.43   135.3   63.82   214.8   64.65
   254.5    62.3   327.4   64.24   476.5   60.59   532.8   56.31   573.5   56.03
   595.8   56.49     609   60.86   649.1   60.02   691.8   61.28   748.1      60
   890.5    62.6   943.6   64.81    1033   65.84  1102.6   63.96  1324.5   64.66
    1353   62.27  1460.6   61.54  1569.7   64.21  1655.8   63.39  1778.4   64.96
  1834.7   64.42  1884.4   65.43  1934.1    68.7  1987.1   73.562057.457   83.62
#Mann= 3 ,0,0
       0     .12       0   476.5     .05       0     609     .12       0
Bank Sta=476.5,609
XS Rating Curve= 0 ,0
Exp/Cntr(USF)=0,0
Exp/Cntr=0.3,0.1

Type RM Length L Ch R = 1 ,2988    ,,,
XS GIS Cut Line= 2
2390890.86195571885512.6359634752391484.81008845883403.096043754
#Sta/Elev= 30
       0   71.15    19.6   71.02    36.7   67.77      81   68.04   108.2   78.16
   125.3   77.08   149.1   69.27   193.5   72.27   329.8   65.56     657   66.18
   680.9   64.34     957   64.88    1032   62.69  1058.6   64.27  1086.5   62.01
  1342.2   61.81  1383.1    57.5  1471.7   58.66  1518.7    62.8  1536.5   62.69
  1546.7   59.89  1560.4   56.12  1628.5   55.67  1655.8   59.46  1669.4   57.48
  1693.3      60  1952.3   60.56  2003.5   67.15  2097.3   87.33 2191.56   87.99
#Mann= 3 ,0,0
       0     .12       0  1546.7     .05       0  1655.8     .12       0
Bank Sta=1546.7,1655.8
XS Rating Curve= 0 ,0
Exp/Cntr(USF)=0,0
Exp/Cntr=0.3,0.1
LCMann Table=0

--- HighHillCreek.g03 (geometry) ---

Geom Title=Existing Calibration
Program Version=6.60

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
River Reach=High Hill Creek ,Reach 1
Reach XY= 30
2363243.59977666883095.1585389252366434.63516231 881068.63046019
2368423.81331766881275.8878175882370371.18916704880731.220620871
     2371160.465     881197.2497     2373858.439     880222.0221
2377959.08395706879888.1722408542378179.99401003879371.546614335
2379704.15649189879174.0132865482379662.07838656878643.361624919
2382002.04649912877858.6026855812384092.27638126880436.938589516
2384750.79872963880744.1087584062385524.28947058880225.906608263
2385426.88644899881376.5609699932386745.53589587881203.803959342
2386221.72409087881444.7862497972386368.91087905882130.214920252
2385575.25662905881669.8954552522385823.45395814882423.145488889
 2386858.0904986882431.8035352532386770.06702723883213.913723436
2387982.19351815882688.6589107082389005.59890139884108.415479815
2388592.61008984884416.209028043 2390010.7980842883647.374510951
2390354.95542716884088.9348754972390604.30716243883562.958558905
2391538.07746275884399.325837634 2393610.0421929884237.968149105