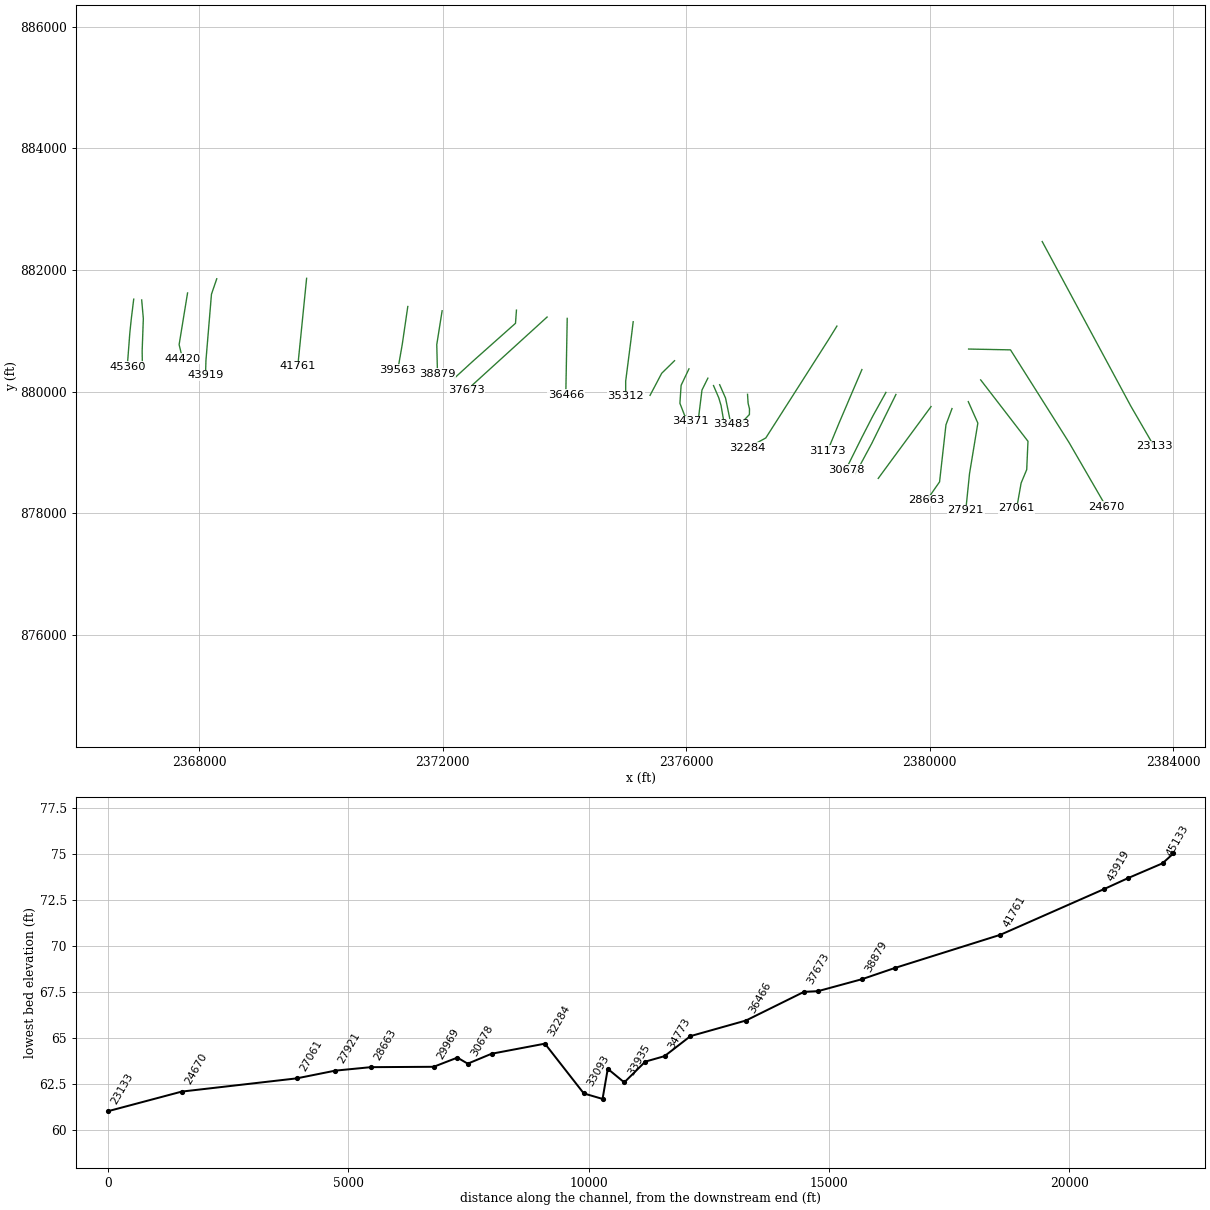
HEC-RAS study HighHillCreek.prj: S-21-356 over High Hill Creek

--- HighHillCreek.g04 (geometry) --- (continued)

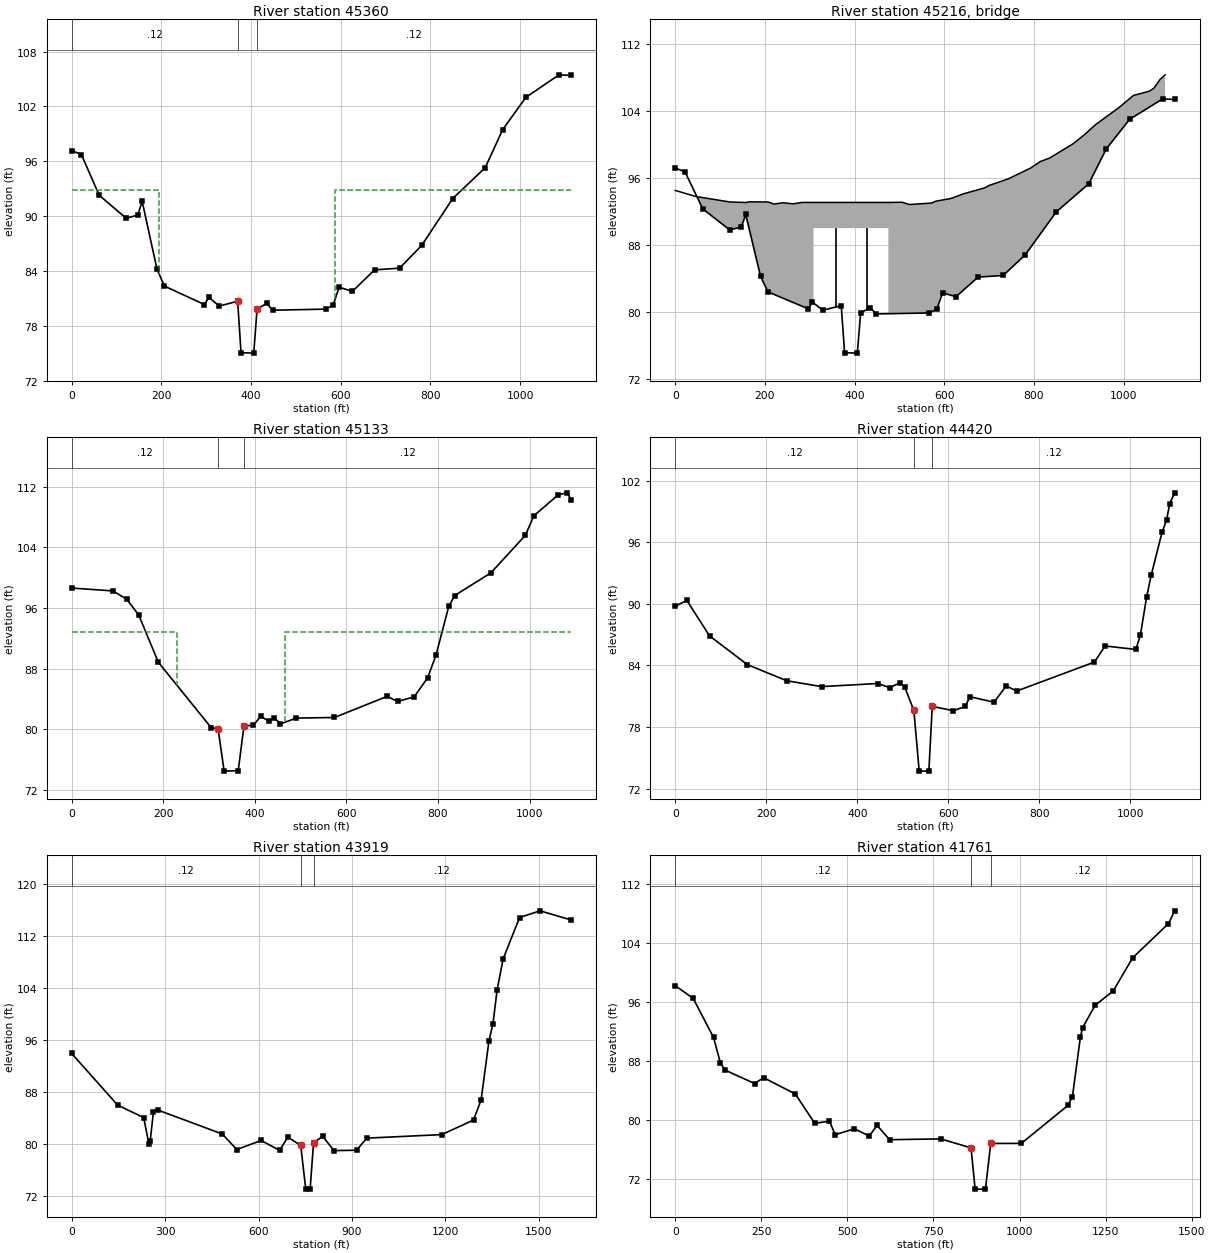
Type RM Length L Ch R = 1 ,45360   ,227.2,227.2,227.2
XS GIS Cut Line= 4
 2366924.9056944881522.1839907562366884.43137281881190.680023462
2366861.30318904 880969.034929052366818.90151881880413.958518697
#Sta/Elev= 30
       0   97.18   21.73   96.75    61.4    92.3  121.27   89.79  147.34   90.12
  157.26   91.63  190.31   84.21  206.84   82.37  296.09   80.35     306   81.13
  329.14   80.18   370.1  80.719  377.67   75.09  405.99   75.04   413.4   79.85
  434.92   80.48  447.91   79.73  566.65   79.85   583.1   80.29  596.27   82.25
  625.88   81.79  675.24   84.14  731.18   84.33  780.55   86.82  849.65   91.94
  922.04   95.31  960.96   99.47 1012.93  103.01 1086.58  105.46 1113.51  105.39
#Mann= 3 ,0,0
       0     .12       0   370.1     .05       0   413.4     .12       0
#XS Ineff= 2 , 0
       0  195.75   92.88  587.75       0   92.82
Permanent Ineff=
       F       F
Bank Sta=370.1,413.4
XS Rating Curve= 0 ,0
Exp/Cntr(USF)=0,0
Exp/Cntr=0.5,0.3

Type RM Length L Ch R = 3 ,45216   ,,,
Bridge Culvert--1,0,-1,-1, 0
Deck Dist Width WeirC Skew NumUp NumDn MinLoCord MaxHiCord MaxSubmerge Is_Ogee
112.5,46.5,2.6,0, 35, 32, , , 0.98, 0, 2,2,,
       0  45.978 121.546 157.687 164.258  206.97 220.113 239.826 262.695 282.532
  308.24  308.25  475.25  475.26 505.742  522.19 571.534 581.025 614.266 643.847
 689.806 699.653 742.362 791.735 814.533 834.493 887.096 913.378 936.375 988.939
1021.7921057.9291067.7851080.9261092.095
  94.506  93.781  93.131   93.06  93.144  93.128  92.875  93.031  92.904  93.068
   93.07   93.07   93.07   93.07  93.095  92.822  92.998  93.222   93.54  94.119
  94.813  95.101  95.888  97.169  97.979  98.375 100.093 101.224 102.352 104.408
 105.878 106.394 106.782 107.793  108.34
                                                                                
              90      90
                                                                                
                                        
       0  45.978 121.546 157.687 164.258  206.97 220.113  264.54  264.55  431.55
  431.56 505.742  522.19 571.534 581.025 614.266 643.847 689.806 699.653 742.362
 791.735 814.533 834.493 887.096 913.378 936.375 988.9391021.7921057.9291067.785
1080.9261092.095
  94.506  93.781  93.131   93.06  93.144  93.128  92.875   93.07   93.07   93.07
   93.07  93.095  92.822  92.998  93.222   93.54  94.119  94.813  95.101  95.888
  97.169  97.979  98.375 100.093 101.224 102.352 104.408 105.878 106.394 106.782
 107.793  108.34
                                                                      90      90
                                                                                
                                                                                
                
Pier Skew, UpSta & Num, DnSta & Num=  ,357.25, 2 ,313.55, 2 , 0 , 0 , 0 ,,
       3       3
       0      91
       3       3
       0      91
Pier Skew, UpSta & Num, DnSta & Num=  ,426.25, 2 ,382.55, 2 , 0 , 0 , 0 ,,
       3       3
       0      91
       3       3
       0      91
Abutment Skew #Up #Dn= , 2 , 2
  308.25  328.25
      89      69
  264.55  284.55
      89      69
Abutment Skew #Up #Dn= , 2 , 2
  455.25  475.25
      69      89
  411.55  431.55
      69      89
BR Coef=-1 , 0 , 0 ,, 0 ,,,0.8,0,,0,
WSPro=,,,, 1 ,,,, 0 ,,,, 0 ,,,,-1 ,-1 ,-1 , 0 , 0 , 0 , 0 , 0
BC Design=,, 0 ,, 0 ,,,,,,
BC Use User HTab Curves=0
BC User HTab FreeFlow(D)= 0

Type RM Length L Ch R = 1 ,45133   ,713,713,713
XS GIS Cut Line= 4
 2367055.9654024881508.6925502272367082.94828345881204.171463991
2367063.67479698880670.2958887562367067.52949428880419.740564638
#Sta/Elev= 30
       0   98.63   90.46   98.25  120.11   97.16  146.46   95.08  189.28   88.85
  304.57   80.24   319.8  80.066  332.97    74.5  363.73   74.56   376.3  80.485
   396.5   80.53  412.92   81.71  431.38   81.06  442.47   81.55   455.6   80.73
  490.81   81.49   573.8   81.57  688.72   84.35   711.7   83.68  747.81   84.29
  777.36    86.8  795.85   89.85  823.33    96.2  836.22   97.64  915.22  100.62
   990.7  105.58 1009.33  108.16 1062.89  110.94 1082.58  111.18 1090.52  110.23
#Mann= 3 ,0,0
       0     .12       0   319.8     .05       0   376.3     .12       0
#XS Ineff= 2 , 0
       0  230.45   92.88  465.65       0   92.82
Permanent Ineff=
       F       F
Bank Sta=319.8,376.3
XS Rating Curve= 0 ,0
Exp/Cntr(USF)=0,0
Exp/Cntr=0.5,0.3

Type RM Length L Ch R = 1 ,44420   ,501.1,501.1,501.1
XS GIS Cut Line= 3
 2367809.5587234 881624.333469052367670.78962081880774.372715697
2367726.68273157880545.018226697
#Sta/Elev= 30
       0   89.78   25.62   90.34   75.49   86.88   158.6   84.08  245.04   82.51
  321.51   81.94  444.52   82.24  471.11   81.84  494.39   82.32  504.36   81.89
   524.3  79.611  536.02    73.7  557.22    73.7   564.7  80.012  611.36   79.59
  637.34   80.01  647.32   80.95  700.51   80.42  727.11      82  750.38   81.51
  920.86   84.33   944.5    85.9 1012.04   85.56 1022.17   87.01 1035.68   90.69
 1045.81   92.81 1069.45   96.97 1079.59   98.19 1086.34   99.77 1097.28  100.83
#Mann= 3 ,0,0
       0     .12       0   524.3     .05       0   564.7     .12       0
Bank Sta=524.3,564.7
XS Rating Curve= 0 ,0
Exp/Cntr(USF)=0,0
Exp/Cntr=0.3,0.1

Type RM Length L Ch R = 1 ,43919   ,2157.9,2157.9,2157.9
XS GIS Cut Line= 4
2368289.25326603881857.0929439242368202.21374983881603.227688338
2368111.54758712880515.233735824 2368104.2942941880272.248419762
#Sta/Elev= 30
       0   93.99  147.92   86.02  231.17   84.12   248.1   80.03  251.98   80.44
  262.38    84.9  275.86   85.29  483.29   81.59  530.21    79.2   608.4   80.59
  667.67   79.06  694.01   81.11   735.4  79.824  751.46    73.1   765.6    73.1
   776.5  80.252  805.95   81.22  842.17   79.03   914.6   79.09  947.53   80.95
 1187.88   81.49 1290.02   83.73 1314.34   86.81 1339.34   95.84 1352.51   98.59
 1365.66  103.75 1385.36  108.57 1437.88  114.91 1503.53  115.94 1603.23  114.54
#Mann= 3 ,0,0
       0     .12       0   735.4     .05       0   776.5     .12       0
Bank Sta=735.4,776.5
XS Rating Curve= 0 ,0
Exp/Cntr(USF)=0,0
Exp/Cntr=0.3,0.1

Type RM Length L Ch R = 1 ,41761   ,2198.1,2198.1,2198.1
XS GIS Cut Line= 2
2369765.29839494881864.3462369412369620.23253461880420.940926606
#Sta/Elev= 30
       0    98.2   52.29   96.46  111.23   91.18  131.43   87.69  144.62   86.75
  230.36   84.93  256.74   85.72  349.08    83.5  405.14   79.53  448.01   79.83
  464.49   77.99  520.55   78.79  563.42   77.82  586.51   79.24  622.78   77.31
  771.18   77.42   859.3    76.2  870.98   70.61  901.03   70.61   916.4    76.8
 1005.31   76.81 1140.51   81.95 1153.71   83.15 1176.79   91.21 1183.38   92.52
 1219.66   95.53 1272.42   97.49 1328.48  101.96 1432.69  106.61 1450.68  108.34
#Mann= 3 ,0,0
       0     .12       0   859.3     .05       0   916.4     .12       0
Bank Sta=859.3,916.4
XS Rating Curve= 0 ,0
Exp/Cntr(USF)=0,0
Exp/Cntr=0.3,0.1

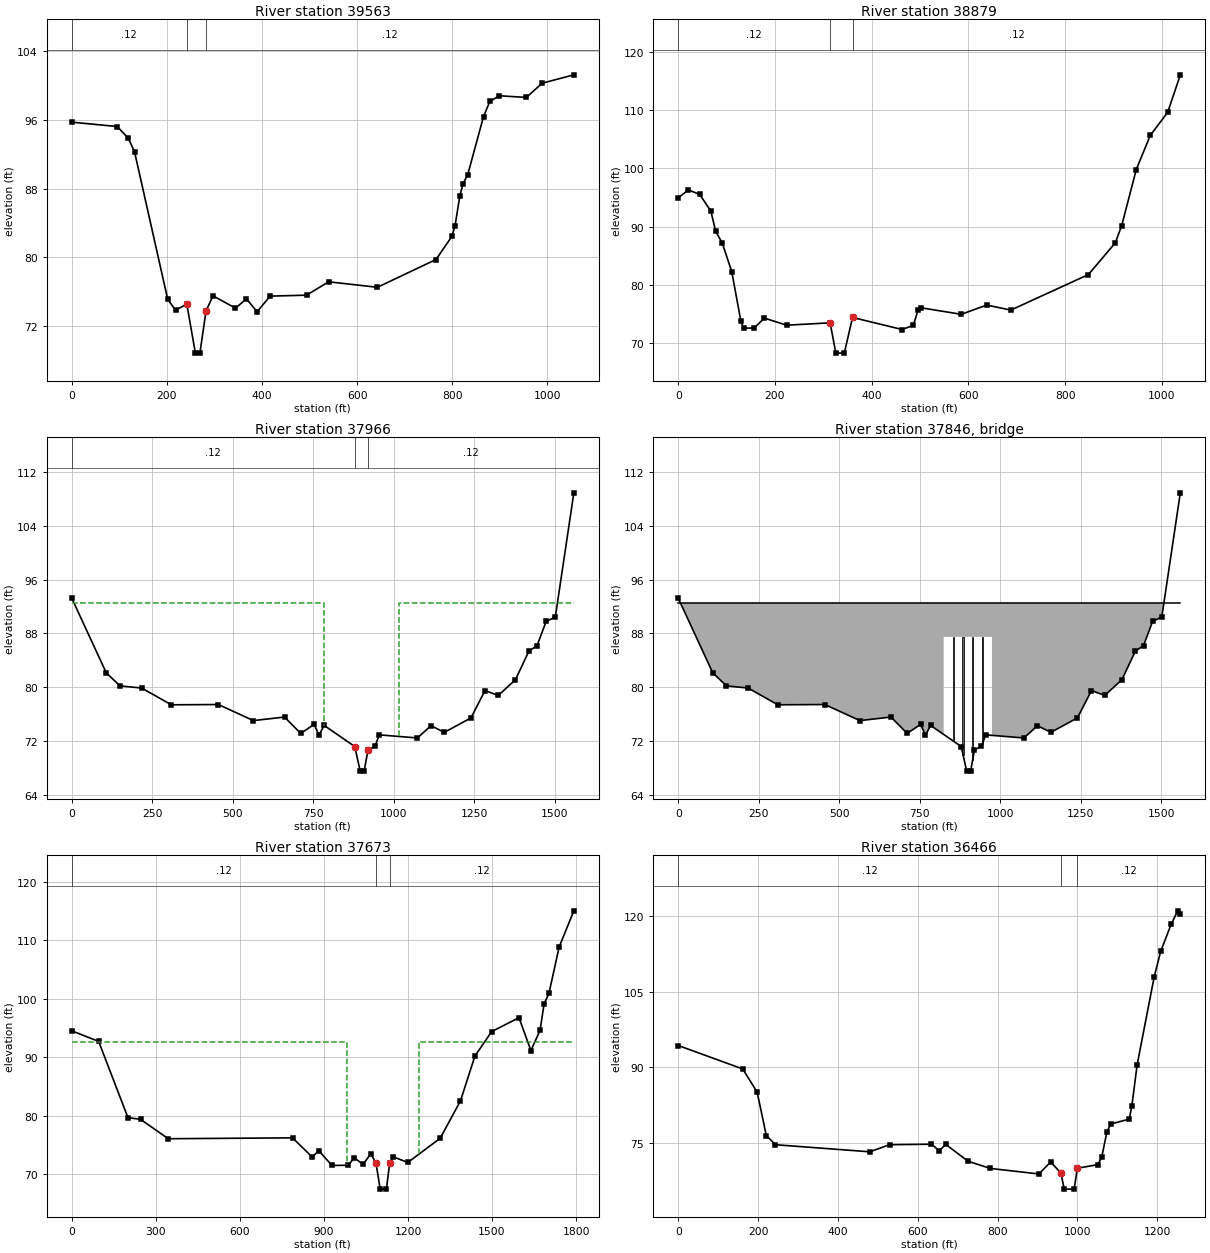
Type RM Length L Ch R = 1 ,39563   ,683.4,683.4,683.4
XS GIS Cut Line= 3
2371427.57182206881401.5498760072371336.50672823880778.782137588
2371263.06713644880358.707672522
#Sta/Elev= 30
       0   95.74   95.53   95.23  118.74   93.88     132   92.28  201.68   75.09
  218.22    73.8   241.9  74.526  259.96    68.8  269.43    68.8   282.4  73.736
  297.08   75.48  344.23   74.05  367.44   75.13  389.66   73.63  417.18   75.45
   493.8   75.56  540.09   77.12  642.73   76.48  765.97   79.72  799.28   82.41
  805.95   83.63  815.94   87.09   822.6   88.53  832.59    89.6   865.9   96.39
  879.23   98.16  899.21   98.82  955.84   98.62  989.14  100.28 1055.84  101.26
#Mann= 3 ,0,0
       0     .12       0   241.9     .05       0   282.4     .12       0
Bank Sta=241.9,282.4
XS Rating Curve= 0 ,0
Exp/Cntr(USF)=0,0
Exp/Cntr=0.3,0.1

Type RM Length L Ch R = 1 ,38879   ,912.8,912.8,912.8
XS GIS Cut Line= 3
2371991.58788704881331.0478678842371903.46037689880775.844553916
2371915.21071157880299.955999086
#Sta/Elev= 30
       0   94.95      21    96.3   44.25   95.54   67.51   92.65   77.48   89.15
   90.77    87.2   110.7   82.22   129.3   73.79  135.04   72.47  157.21   72.54
  178.04   74.23  223.92      73  314.12   73.41  325.86   68.19   343.4   68.19
   360.4  74.337  462.85   72.26  486.11   72.97  496.07   75.66  502.72   75.99
  585.19   74.88     638   76.47  687.68    75.6  848.06   81.72  903.86    87.2
  916.98   90.16  947.13   99.82  976.06  105.69 1012.17  109.69 1038.19  116.13
#Mann= 3 ,0,0
       0     .12       0  314.12     .05       0   360.4     .12       0
Bank Sta=314.12,360.4
XS Rating Curve= 0 ,0
Exp/Cntr(USF)=0,0
Exp/Cntr=0.5,0.3

Type RM Length L Ch R = 1 ,37966   ,293.5,293.5,293.5
XS GIS Cut Line= 4
 2373212.5198401881341.6548465152373196.92097123881125.639110115
2372501.97479952880506.9903224492372197.91797148880228.048851198
#Sta/Elev= 30
       0   93.25  107.09   82.16  149.86   80.21  217.15   79.89   309.4    77.4
   455.6   77.44  564.19   75.05  660.84   75.58  711.24   73.14  753.06    74.5
  767.87   72.86  783.84   74.34     879    71.2  896.02   67.54  908.25   67.54
   920.1  70.674  941.98   71.25  955.16   72.93 1073.82   72.47 1115.62   74.29
 1157.53   73.31 1240.04   75.45 1283.72   79.52 1324.65   78.79 1378.06   81.12
 1420.08   85.38 1445.41    86.2 1473.51   89.79 1502.14   90.46 1559.62  108.91
#Mann= 3 ,0,0
       0     .12       0     879     .05       0   920.1     .12       0
#XS Ineff= 2 , 0
       0  782.55    92.6 1016.55       0    92.6
Permanent Ineff=
       F       F
Bank Sta=879,920.1
XS Rating Curve= 0 ,0
Exp/Cntr(USF)=0,0
Exp/Cntr=0.5,0.3

Type RM Length L Ch R = 3 ,37846   ,,,
Bridge Culvert--1,0,-1,-1, 0
Deck Dist Width WeirC Skew NumUp NumDn MinLoCord MaxHiCord MaxSubmerge Is_Ogee
42,145.7,2.6,0, 6, 6, , , 0.98, 0, 2,2,,
       0  824.54  824.55  974.55  974.56 1559.62
    92.6    92.6    92.6    92.6    92.6    92.6
                    87.5    87.5
       0 1035.29  1035.3  1185.3 1185.31 1792.15
    92.6    92.6    92.6    92.6    92.6    92.6
                    87.5    87.5
Pier Skew, UpSta & Num, DnSta & Num=  ,854.55, 2 ,1065.3, 2 , 0 , 0 , 0 ,,
       5       5
    67.5    87.5
       5       5
    67.5    87.5
Pier Skew, UpSta & Num, DnSta & Num=  ,884.55, 2 ,1095.3, 2 , 0 , 0 , 0 ,,
       5       5
    67.5    87.5
       5       5
    67.5    87.5
Pier Skew, UpSta & Num, DnSta & Num=  ,914.55, 2 ,1125.3, 2 , 0 , 0 , 0 ,,
       5       5
    67.5    87.5
       5       5
    67.5    87.5
Pier Skew, UpSta & Num, DnSta & Num=  ,944.55, 2 ,1155.3, 2 , 0 , 0 , 0 ,,
       5       5
    67.5    87.5
       5       5
    67.5    87.5
Abutment Skew #Up #Dn= , 2 , 2
  824.55  844.55
    86.5    66.5
 1035.29  1055.3
    86.5    66.5
Abutment Skew #Up #Dn= , 2 , 2
  954.55  974.55
    66.5    86.5
  1165.3 1185.29
    66.5    86.5
BR Coef=-1 , 0 , 0 ,, 0 ,,,0.8,0,,0,
WSPro=,,,, 1 ,,,, 0 ,,,, 0 ,,,,-1 ,-1 ,-1 , 0 , 0 , 0 , 0 , 0
BC Design=,, 0 ,, 0 ,,,,,,
BC Use User HTab Curves=0
BC User HTab FreeFlow(D)= 0

Type RM Length L Ch R = 1 ,37673   ,1206.5,1206.5,1206.5
XS GIS Cut Line= 2
2373715.94950238881228.2324393712372390.84181334880021.633565704
#Sta/Elev= 30
       0   94.54   95.93   92.74  200.45   79.72  245.47   79.42  344.45   76.11
  788.08   76.26  857.86      73  882.02   74.05  928.86   71.54  986.55   71.58
 1008.73   72.84  1039.8   71.72 1067.21   73.54  1085.971.96136 1100.88    67.5
 1123.05    67.5  1134.771.91929 1148.09      73 1199.55   72.06 1314.93   76.18
 1387.32   82.56 1439.18   90.25 1498.81   94.41 1596.36   96.79 1638.87   91.17
 1671.51   94.63 1686.13   99.18 1703.21  100.93 1739.74  108.87 1792.15  115.04
#Mann= 3 ,0,0
       0     .12       0  1085.9     .05       0  1134.7     .12       0
#XS Ineff= 2 , 0
       0   982.4    92.6  1238.2       0    92.6
Permanent Ineff=
       F       F
Bank Sta=1085.9,1134.7
XS Rating Curve= 0 ,0
Exp/Cntr(USF)=0,0
Exp/Cntr=0.5,0.3

Type RM Length L Ch R = 1 ,36466   ,1154.7,1154.7,1154.7
XS GIS Cut Line= 2
2374046.49470773881206.0258288342374022.99403835879948.740017308
#Sta/Elev= 30
       0   94.34  161.52    89.7  197.62   85.13  220.59   76.54  243.56   74.72
  479.84   73.32  529.21   74.72  634.08   74.82  653.77   73.55  670.18   74.78
  725.97   71.45  781.76   70.03  903.47   68.94  932.72   71.31   958.5   69.12
  966.72   65.94   991.7   65.94   999.6  70.074 1050.86   70.78  1060.7   72.28
 1073.83    77.3 1083.31   78.81 1129.62   79.79 1136.18    82.4 1149.31    90.5
 1191.97  107.86 1208.38  112.96 1234.63  118.32 1251.04  120.97 1257.51  120.35
#Mann= 3 ,0,0
       0     .12       0   958.5     .05       0   999.6     .12       0
Bank Sta=958.5,999.6
XS Rating Curve= 0 ,0
Exp/Cntr(USF)=0,0
Exp/Cntr=0.3,0.1

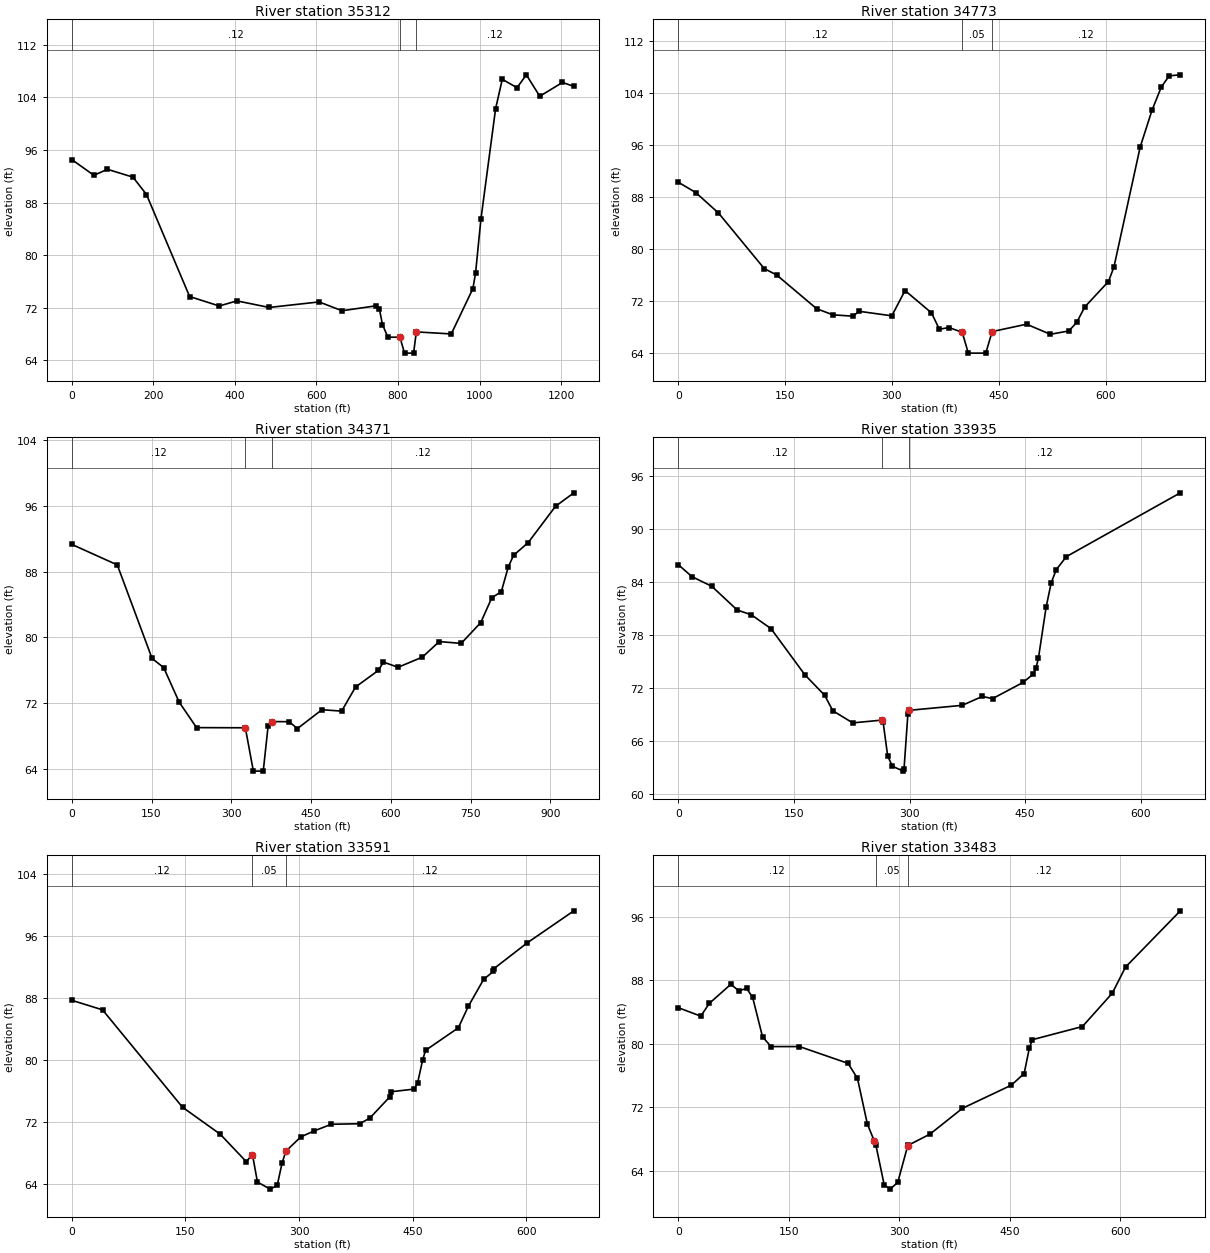
Type RM Length L Ch R = 1 ,35312   ,539,539,539
XS GIS Cut Line= 4
2375130.22613982881150.9458156392375094.23822683880857.326687737
2375006.70741348880173.6482118342375007.19970881879927.367252335
#Sta/Elev= 30
       0   94.54   54.31   92.14   87.37   93.06  150.18   91.86  183.24   89.22
  289.02    73.7  361.79   72.26  404.79   73.04  484.18   72.04  606.57   72.88
  662.81   71.54  745.51   72.28  754.24   71.84  762.05   69.44  775.28   67.51
   804.8  67.514  816.07   65.09  838.26   65.09   845.1  68.319  930.75   68.01
  983.68   74.89  990.25   77.23 1003.37   85.43 1039.47  102.28 1055.87  106.75
 1091.96  105.47 1114.93  107.43 1147.74  104.17 1203.52  106.27 1231.36  105.67
#Mann= 3 ,0,0
       0     .12       0   804.8     .05       0   845.1     .12       0
Bank Sta=804.8,845.1
XS Rating Curve= 0 ,0
Exp/Cntr(USF)=0,0
Exp/Cntr=0.3,0.1

Type RM Length L Ch R = 1 ,34773   ,401.7,401.7,401.7
XS GIS Cut Line= 3
 2375809.2555984880510.4897835882375598.50002385880303.949320524
2375407.41496958879941.449732288
#Sta/Elev= 30
       0    90.3   24.55   88.71   56.51   85.56  120.82      77  138.14   76.03
  194.33   70.83   217.3   69.89  244.86   69.69  254.25   70.43  299.87   69.74
  318.41   73.63  355.51    70.2  366.63   67.67     380   67.94   398.7  67.203
  407.24      64  431.78      64   440.7  67.316  489.03   68.45  522.41    66.9
  548.38   67.41  559.51   68.74  570.63   71.09  604.01   75.02   611.7   77.26
  648.52   95.71  665.13  101.37   678.2  104.95  689.32  106.67  704.87  106.82
#Mann= 3 ,0,0
       0     .12       0   398.7     .05       0   440.7     .12       0
Bank Sta=398.7,440.7
XS Rating Curve= 0 ,0
Exp/Cntr(USF)=0,0
Exp/Cntr=0.3,0.1

Type RM Length L Ch R = 1 ,34371   ,436.4,436.4,436.4
XS GIS Cut Line= 5
2376046.70687907880377.0112530362375917.44346001880105.839080442
2375897.77293972879810.7812760642375975.04998372879611.265998818
2376070.59251085879517.128508849
#Sta/Elev= 30
       0   91.32   85.62   88.82  151.05   77.42  172.86   76.31  201.94   72.11
  234.65      69  326.42   68.98  341.52    63.7  360.09    63.7  369.17   69.16
   375.7  69.739  408.87   69.72  424.28   68.88  470.53   71.18  507.52   71.01
  533.59   73.94  576.34   75.96   586.2   76.98  613.66   76.35   659.4   77.59
  691.07   79.48  732.34   79.26  769.06   81.79  790.09   84.84  807.68   85.54
  820.92   88.57  830.73   89.98  858.37   91.54  909.74   95.96   944.2    97.6
#Mann= 3 ,0,0
       0     .12       0  326.42     .05       0   375.7     .12       0
Bank Sta=326.42,375.7
XS Rating Curve= 0 ,0
Exp/Cntr(USF)=0,0
Exp/Cntr=0.3,0.1

Type RM Length L Ch R = 1 ,33935   ,343.3,343.3,343.3
XS GIS Cut Line= 3
2376357.22009225880223.8622021932376260.27252795880028.562036438
2376206.88111573879598.620664344
#Sta/Elev= 30
       0   85.99   17.88   84.62   43.52   83.53   76.49   80.84    94.8    80.3
  120.32   78.73   164.4   73.48  190.05   71.16  200.46   69.42  226.35   68.04
  264.65   68.36  265.65   68.19   271.7   64.28  277.73   63.13  291.85   62.57
  292.86   62.76   297.9   69.06  298.91   69.46  368.38   70.03  394.46   71.04
  407.69   70.79  447.36   72.63  460.59   73.58  463.89   74.21   467.2   75.36
   477.2   81.16  483.73    83.9  490.34   85.42  503.57    86.9  651.28   94.13
#Mann= 3 ,0,0
       0     .12       0  264.65     .05       0  298.91     .12       0
Bank Sta=264.65,298.91
XS Rating Curve= 0 ,0
Exp/Cntr(USF)=0,0
Exp/Cntr=0.3,0.1

Type RM Length L Ch R = 1 ,33591   ,108.3,108.3,108.3
XS GIS Cut Line= 4
2376449.95254505 880101.623968952376535.65981204879902.108691704
2376573.59581546879774.2503098072376626.98722768879466.547170956
#Sta/Elev= 30
       0   87.68   40.61   86.45  146.18   73.88  195.86   70.41   230.5   66.84
   237.8   67.74  238.84   67.61   245.1   64.23  261.79   63.31  271.18   63.78
  277.51   66.63  282.65   68.21  302.36   70.05  320.14   70.83  342.56   71.68
  379.99   71.75  393.31   72.46  419.95   75.23  421.75   75.88  451.91   76.22
  456.58   77.03  463.24      80  467.04   81.22  510.33   84.13  523.49    86.9
  543.64   90.37  556.64   91.42  556.95   91.74  601.19   95.09  662.81   99.23
#Mann= 3 ,0,0
       0     .12       0   237.8     .05       0  282.65     .12       0
Bank Sta=237.8,282.65
XS Rating Curve= 0 ,0
Exp/Cntr(USF)=0,0
Exp/Cntr=0.3,0.1

Type RM Length L Ch R = 1 ,33483   ,390.5,390.5,390.5
XS GIS Cut Line= 3
2376550.93006877880115.6743405872376647.87763307879895.083505886
2376736.39497438879463.737096629
#Sta/Elev= 30
       0   84.57   30.61    83.5   42.18   85.11    71.4   87.52    82.1    86.7
   92.85   86.99     101   85.86  114.36    80.9   125.9   79.66  164.54   79.66
  230.47   77.54  243.23   75.64  256.62   69.89   266.267.70566  268.29   67.19
  279.52   62.19  287.68   61.67  297.89   62.53   311.2  67.084  312.18   67.21
  341.58   68.61  385.68   71.87  452.04   74.79  469.39   76.26  476.54   79.52
  480.62   80.53   548.5   82.19  589.02    86.4  606.93   89.69  681.29   96.79
#Mann= 3 ,-1,0
       0     .12       0  268.29     .05       0  312.18     .12       0
Bank Sta=266.2,311.2
XS Rating Curve= 0 ,0
Exp/Cntr(USF)=0,0
Exp/Cntr=0.3,0.1

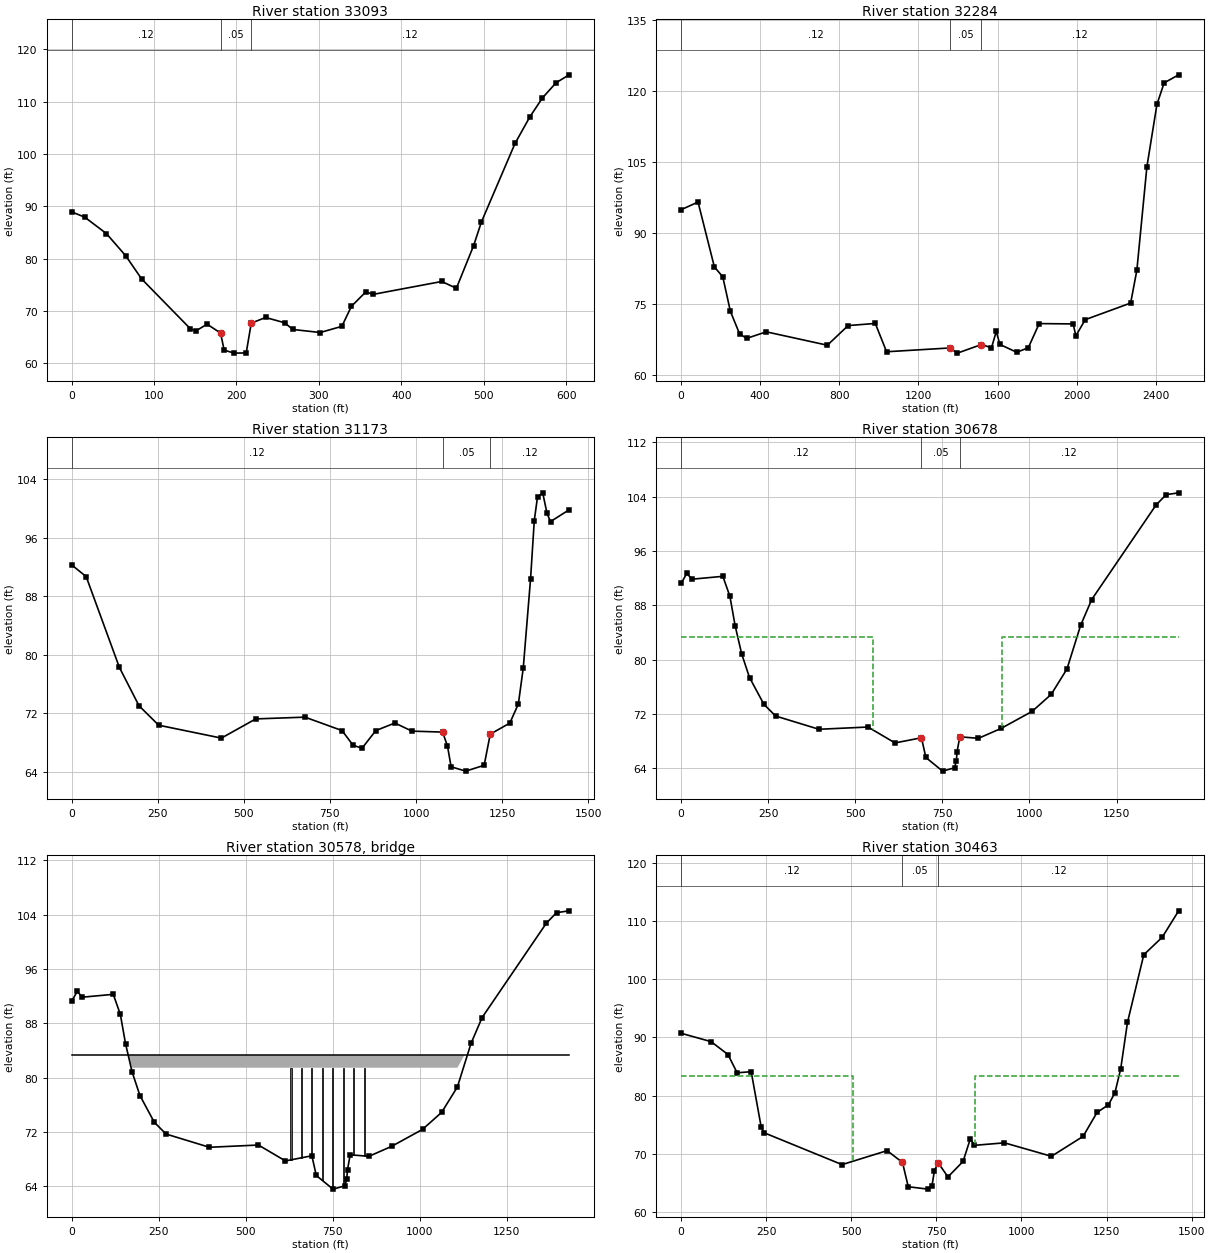
Type RM Length L Ch R = 1 ,33093   ,808.6,808.6,808.6
XS GIS Cut Line= 5
2377008.50454103879958.0559154192377018.14609691879810.829401343
2377040.95607306879718.3072385062377039.60608759879626.166422496
 2376854.6032482879431.421241863
#Sta/Elev= 30
       0   88.97   16.01   87.95   42.32   84.81   65.69   80.58   85.07   76.14
  144.25   66.61  150.92   66.22  164.44    67.5   180.8   65.81  185.15   62.53
  197.65   61.97  211.93   62.01     218    67.7   235.4   68.78  258.59   67.77
  268.43   66.49  301.71   65.91  327.96   67.09   339.6   70.93  356.98   73.66
  366.03    73.2  449.17   75.66  466.87   74.36  487.76    82.5  497.27   87.04
     538  102.03   556.1  107.14  571.31  110.74  587.78  113.63   603.6  115.15
#Mann= 3 ,0,0
       0     .12       0   180.8     .05       0     218     .12       0
Bank Sta=180.8,218
XS Rating Curve= 0 ,0
Exp/Cntr(USF)=0,0
Exp/Cntr=0.3,0.1

Type RM Length L Ch R = 1 ,32284   ,1110.6,1110.6,1110.6
XS GIS Cut Line= 5
2378476.81670447 881079.268953852378335.51685215880850.873984928
2377308.64001248879241.0463631552377161.40355795879159.727810899
2377011.93256069879079.062642513
#Sta/Elev= 30
       0   94.98   85.54   96.59  168.17   82.89  210.61    80.8  249.19    73.5
  295.21   68.79  330.75   67.79  430.65   69.18  739.55   66.35  844.47    70.5
  981.92   70.95 1039.06   64.97 1358.19   65.77 1397.11   64.68 1518.92    66.5
 1569.56   65.81 1593.97   69.29 1611.59   66.52 1697.33   64.86 1755.71   65.82
 1810.79   70.92 1982.57   70.85 1996.13   68.34  2043.7   71.75 2273.28   75.26
 2304.67   82.18  2355.4  104.03 2406.21  117.22 2442.58  121.77 2516.07  123.47
#Mann= 3 ,-1,0
       0     .12       0 1358.19     .05       0 1518.92     .12       0
Bank Sta=1358.19,1518.92
XS Rating Curve= 0 ,0
Exp/Cntr(USF)=0,0
Exp/Cntr=0.3,0.1

Type RM Length L Ch R = 1 ,31173   ,495.4,495.4,495.4
XS GIS Cut Line= 3
2378887.56100561880365.0157456882378519.33786266 879503.07881566
2378325.88470185879034.505597676
#Sta/Elev= 30
       0    92.3    42.5   90.69   138.8    78.3   195.9   73.05     253    70.4
   434.9   68.64   534.8   71.26   677.6    71.5   785.1   69.67   817.2   67.67
   843.1   67.25   883.1   69.66   938.5    70.7   988.2   69.59 1076.96  69.462
  1091.2   67.57  1101.8   64.72  1144.4   64.13  1197.7   64.93  1215.4   69.18
  1272.2   70.69    1297    73.3  1311.2   78.21  1332.5   90.43  1343.2   98.35
  1352.6  101.57  1367.7  102.13  1380.2   99.32  1390.3    98.2  1444.2   99.81
#Mann= 3 ,0,0
       0     .12       0 1076.96     .05       0  1215.4     .12       0
Bank Sta=1076.96,1215.4
XS Rating Curve= 0 ,0
Exp/Cntr(USF)=0,0
Exp/Cntr=0.5,0.3

Type RM Length L Ch R = 1 ,30678   ,214.9,214.9,214.9
XS GIS Cut Line= 4
2379281.99773163879989.0942886692379068.23534688879603.404517152
2378890.26439385879257.0826626052378623.90770797 878721.59280094
#Sta/Elev= 30
       0   91.21    16.2   92.69    31.2   91.84   119.8   92.26   140.1   89.31
     155      85   173.8   80.85   196.3   77.37   237.6   73.43   271.3    71.7
   395.7   69.75   536.6   70.08   614.1   67.74     69068.49918   702.6    65.6
   750.6   63.59     785   64.08  790.17   65.12   792.3   66.47     80068.64063
   853.7   68.42   918.8   69.88  1007.6   72.38  1062.6   74.89  1107.8   78.63
  1146.9   85.04  1178.8   88.85  1363.1  102.73  1392.4  104.28  1428.4  104.55
#Mann= 3 ,0,0
       0     .12       0     690     .05       0     800     .12       0
#XS Ineff= 2 , 0
       0     550   83.29     920       0   83.29
Permanent Ineff=
       F       F
Bank Sta=690,800
XS Rating Curve= 0 ,0
Exp/Cntr(USF)=0,0
Exp/Cntr=0.5,0.3

Type RM Length L Ch R = 3 ,30578   ,,,
Bridge Culvert--1,0,-1,-1, 0
Deck Dist Width WeirC Skew NumUp NumDn MinLoCord MaxHiCord MaxSubmerge Is_Ogee
50,77,2.6,0, 6, 6, , , 0.98, 0, 0,0,,
       0  599.99     600     870  870.01  1428.4
   83.29   83.29   83.29   83.29   83.29   83.29
   81.46           81.46   81.46           81.46
       0  549.99     550     820  820.01  1428.4
   83.29   83.29   83.29   83.29   83.29   83.29
   81.46           81.46   81.46           81.46
Pier Skew, UpSta & Num, DnSta & Num=  ,630, 2 ,580, 2 , 0 , 0 , 0 ,,
       3       3
   63.59   81.46
       3       3
   63.59   81.46
Pier Skew, UpSta & Num, DnSta & Num=  ,660, 2 ,610, 2 , 0 , 0 , 0 ,,
       3       3
   63.59   81.46
       3       3
   63.59   81.46
Pier Skew, UpSta & Num, DnSta & Num=  ,690, 2 ,640, 2 , 0 , 0 , 0 ,,
       3       3
   63.59   81.46
       3       3
   63.59   81.46
Pier Skew, UpSta & Num, DnSta & Num=  ,720, 2 ,670, 2 , 0 , 0 , 0 ,,
       3       3
   63.59   81.46
       3       3
   63.59   81.46
Pier Skew, UpSta & Num, DnSta & Num=  ,750, 2 ,700, 2 , 0 , 0 , 0 ,,
       3       3
   63.59   81.46
       3       3
   63.59   81.46
Pier Skew, UpSta & Num, DnSta & Num=  ,780, 2 ,730, 2 , 0 , 0 , 0 ,,
       3       3
   63.59   81.46
       3       3
   63.59   81.46
Pier Skew, UpSta & Num, DnSta & Num=  ,810, 2 ,760, 2 , 0 , 0 , 0 ,,
       3       3
   63.59   81.46
       3       3
   63.59   81.46
Pier Skew, UpSta & Num, DnSta & Num=  ,840, 2 ,790, 2 , 0 , 0 , 0 ,,
       3       3
   63.59   81.46
       3       3
   63.59   81.46
Abutment Skew #Up #Dn= , 2 , 2
     600     620
    80.5    60.5
     550     570
    80.5    60.5
Abutment Skew #Up #Dn= , 2 , 2
     850     870
    60.5    80.5
     800     820
    60.5    80.5
BR Coef=-1 , 0 , 0 ,, 0 ,,,0.8,0,,0,
WSPro=,,,, 1 ,,,, 0 ,,,, 0 ,,,,-1 ,-1 ,-1 , 0 , 0 , 0 , 0 , 0
BC Design=83.29,81.46, 0 ,, 0 ,,10,600,550,30,3
BC Use User HTab Curves=0
BC User HTab FreeFlow(D)= 0

Type RM Length L Ch R = 1 ,30463   ,494.2,494.2,494.2
XS GIS Cut Line= 3
2379446.63493058879956.1584166682379050.17211358879152.287508376
2378782.07235233878654.236461969
#Sta/Elev= 30
       0   90.69    88.1   89.25   137.6   87.04   164.6    83.9   205.9   84.09
   235.2    74.6   243.9    73.6   472.9   68.13   605.2   70.53 650.363 68.5068
   667.4   64.33   725.2   63.92   736.9   64.44   744.2   67.06755.1229 68.4464
     784   66.02   828.4   68.67   849.9   72.59   861.3   71.44   950.1   71.87
  1088.1   69.56  1181.1   72.98  1222.1   77.09  1255.7   78.41  1274.6   80.46
  1291.6   84.58  1311.5   92.55  1359.4  104.17  1413.7  107.19  1461.9  111.72
#Mann= 3 ,0,0
       0     .12       0 650.363     .05       0755.1229     .12       0
#XS Ineff= 2 , 0
       0  506.05   83.29  863.95       0   83.29
Permanent Ineff=
       F       F
Bank Sta=650.363,755.1229
XS Rating Curve= 0 ,0
Exp/Cntr(USF)=0,0
Exp/Cntr=0.5,0.3

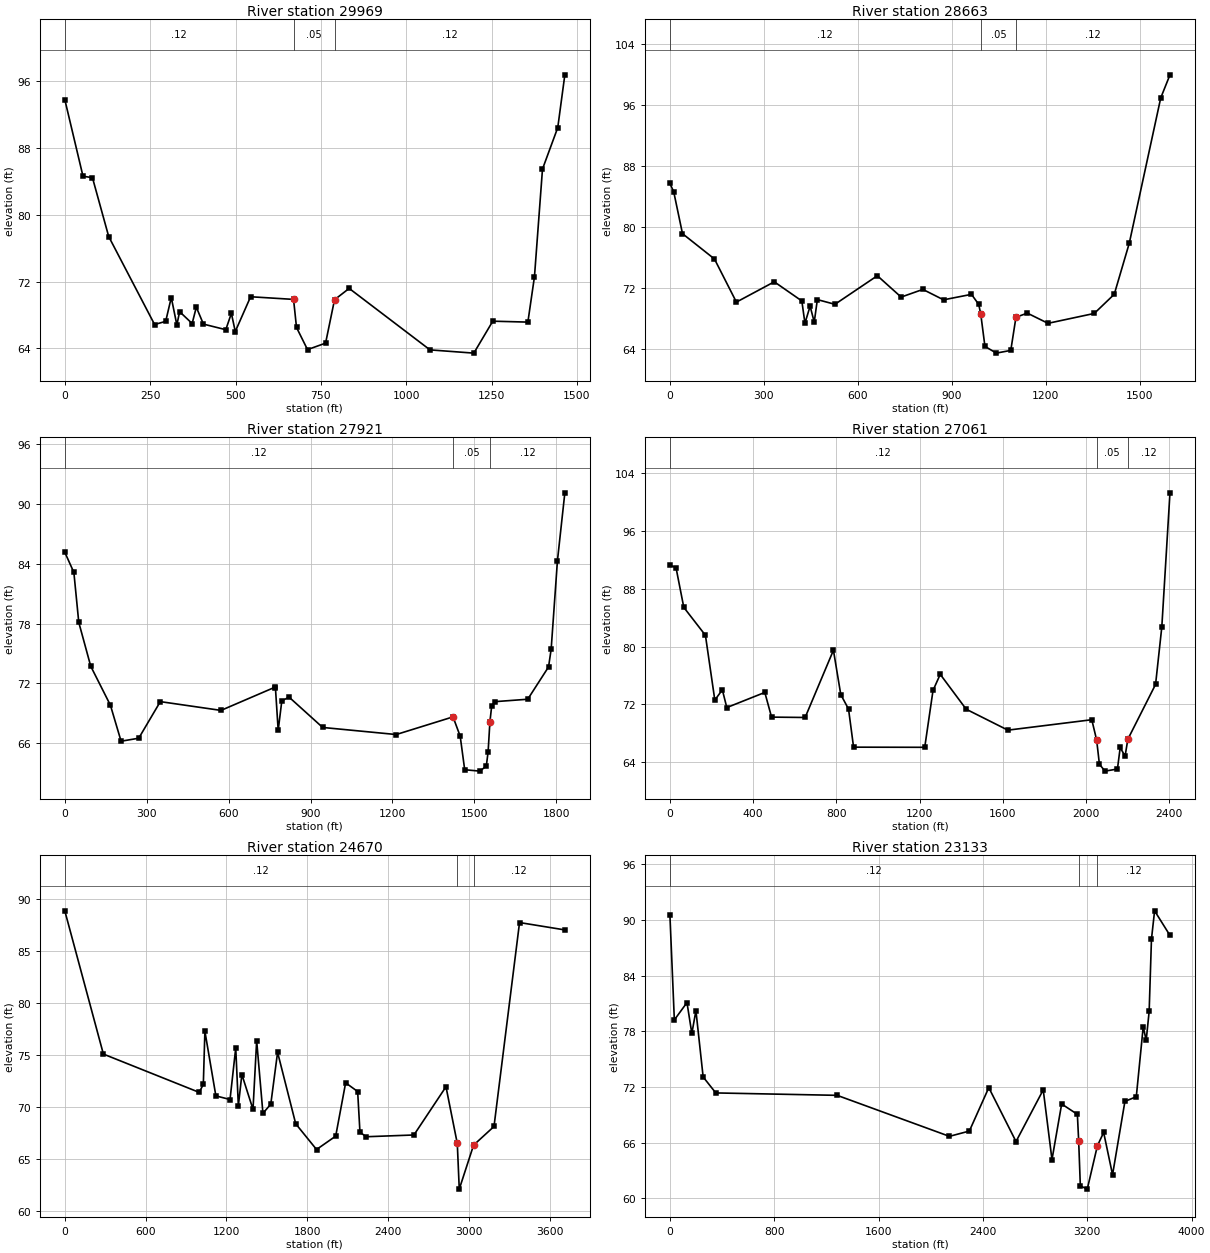
Type RM Length L Ch R = 1 ,29969   ,1306.1,1306.1,1306.1
XS GIS Cut Line= 3
2380023.32534268879756.4374891722379380.38523308878882.616143208
2379155.91736439878576.377836641
#Sta/Elev= 30
       0   93.83    53.3   84.63      81   84.46   128.6    77.4     263   66.85
   295.5   67.23   311.9   70.09   328.2    66.8   336.3   68.39     373   66.97
   385.2   68.93     406    66.9   471.5   66.23   487.9   68.19   499.3   66.01
   544.2   70.18     670  69.862  678.65    66.5   710.9   63.84  763.82   64.62
     790  69.823   832.9   71.18  1069.6   63.81    1198   63.42  1253.5   67.25
  1356.3   67.14  1375.6   72.59  1399.1   85.49  1443.8   90.461464.561   96.79
#Mann= 3 ,0,0
       0     .12       0     670     .05       0     790     .12       0
Bank Sta=670,790
XS Rating Curve= 0 ,0
Exp/Cntr(USF)=0,0
Exp/Cntr=0.3,0.1

Type RM Length L Ch R = 1 ,28663   ,741.9,741.9,741.9
XS GIS Cut Line= 4
2380367.77677556879723.7515792642380268.33225671 879456.94487842
2380163.33764345878519.1279782452379953.12372149878217.554695363
#Sta/Elev= 30
       0   85.71   12.12   84.62   40.13   79.11  142.17   75.78   212.2   70.11
  333.12   72.78  421.04   70.26  430.95   67.33  447.46   69.58  460.66   67.47
  470.57   70.44  526.69   69.82  662.06   73.58  737.99   70.77  807.33   71.78
  873.36   70.41   962.5   71.13  985.61   69.81  992.14   68.53 1005.42   64.29
 1041.74    63.4 1087.96   63.76 1104.47   68.12 1140.79   68.66 1206.82   67.32
 1354.43   68.62 1418.23   71.14 1466.22   77.87 1566.54   96.96 1596.02     100
#Mann= 3 ,-1,0
       0     .12       0  992.14     .05       0 1104.47     .12       0
Bank Sta=992.14,1104.47
XS Rating Curve= 0 ,0
Exp/Cntr(USF)=0,0
Exp/Cntr=0.3,0.1

Type RM Length L Ch R = 1 ,27921   ,800.6,800.6,800.6
XS GIS Cut Line= 4
2380634.88804295879837.9077336212380792.25679347879484.615096819
2380655.32592169878654.0922449482380593.96345318878054.323601099
#Sta/Elev= 30
       0   85.16   33.23   83.14   51.19   78.13      95   73.73  167.07   69.82
  206.15   66.21   270.8   66.51  349.83   70.18  572.04    69.3  768.24   71.61
  771.56   71.52  781.54    67.3  794.84   70.26  821.44   70.63  944.48   67.59
 1213.84   66.881421.883   68.65 1448.13   66.71 1464.62   63.35 1520.38   63.21
 1543.78   63.72 1550.38   65.151556.973  68.161 1563.57   69.76 1576.76   70.18
  1695.5   70.42 1771.71   73.66 1781.25   75.43 1804.34   84.33 1831.39   91.12
#Mann= 3 ,-1,0
       0     .12       01421.883     .05       01556.973     .12       0
Bank Sta=1421.883,1556.973
XS Rating Curve= 0 ,0
Exp/Cntr(USF)=0,0
Exp/Cntr=0.3,0.1

Type RM Length L Ch R = 1 ,27061   ,2391.4,2391.4,2391.4
XS GIS Cut Line= 5
2380838.76893437880195.038226716 2381615.6353116879186.501931037
2381594.98226552878720.7848632632381503.11622156878500.097346199
2381429.28479874878082.035683653
#Sta/Elev= 30
       0   91.25   29.39   90.88   66.66   85.41  170.64   81.55  215.77    72.6
  251.86   74.02  273.36   71.57  455.98   73.66  488.44   70.25  649.74    70.2
  785.71   79.49  821.04   73.36  858.31   71.36  882.49    66.1 1224.44   66.08
 1264.19   73.93 1298.87   76.16 1423.67   71.34 1624.02   68.45 2027.12   69.89
2050.444  67.089 2063.77   63.75 2090.42   62.79 2150.39   63.08 2163.72   66.06
 2187.05   64.842200.374  67.191 2333.65   74.77 2363.63   82.71  2402.8  101.23
#Mann= 3 ,-1,0
       0     .12       02050.444     .05       02200.374     .12       0
Bank Sta=2050.444,2200.374
XS Rating Curve= 0 ,0
Exp/Cntr(USF)=0,0
Exp/Cntr=0.3,0.1

Type RM Length L Ch R = 1 ,24670   ,1537,1537,1537
XS GIS Cut Line= 4
2380640.56690893880702.1806822952381328.57436456880688.793700695
2382290.15371061879166.2218328322382901.88334896878108.474907278
#Sta/Elev= 30
       0    88.9  286.33   75.09  996.96    71.4 1028.01   72.16 1039.65   77.29
 1121.14   71.06 1226.18   70.71 1268.61   75.69 1288.01   70.11 1314.03   73.12
 1396.67   69.76 1423.84   76.39 1470.41   69.38 1528.62   70.26 1579.07   75.26
 1713.62   68.37 1868.23   65.89 2010.37   67.18  2084.1   72.32 2173.35   71.48
 2190.34   67.57 2235.45   67.12  2590.9   67.29 2828.84   71.942912.691  66.472
 2927.39   62.073033.511   66.31 3185.13   68.11 3374.64   87.77 3710.83   87.06
#Mann= 3 ,-1,0
       0     .12       02912.691     .05       03033.511     .12       0
Bank Sta=2912.691,3033.511
XS Rating Curve= 0 ,0
Exp/Cntr(USF)=0,0
Exp/Cntr=0.3,0.1

Type RM Length L Ch R = 1 ,23133   ,1671.8,1671.8,1671.8
XS GIS Cut Line= 3
2381849.49831392882468.8855487422383305.00756306879764.490505228
2383687.19139872879104.668215656
#Sta/Elev= 30
       0   90.54   33.92   79.24   130.8   81.11  168.06   77.78  199.38   80.24
  254.77   73.09   351.7   71.37 1282.18   71.11 2142.93   66.69  2295.7   67.26
 2444.74   71.94 2653.41   66.13 2862.07    71.7 2929.14   64.18 3003.34   70.18
 3123.82   69.06 3133.81   66.19 3146.57   61.35 3199.64      61 3277.26   65.67
 3325.31   67.11 3393.56   62.55 3488.36   70.46 3575.57   70.96 3628.65   78.51
  3651.4   77.04 3674.15   80.15 3691.85   87.95 3715.86      91 3833.71   88.35
#Mann= 3 ,-1,0
       0     .12       0 3133.81     .05       0 3277.26     .12       0
Bank Sta=3133.81,3277.26
XS Rating Curve= 0 ,0
Exp/Cntr(USF)=0,0
Exp/Cntr=0.3,0.1