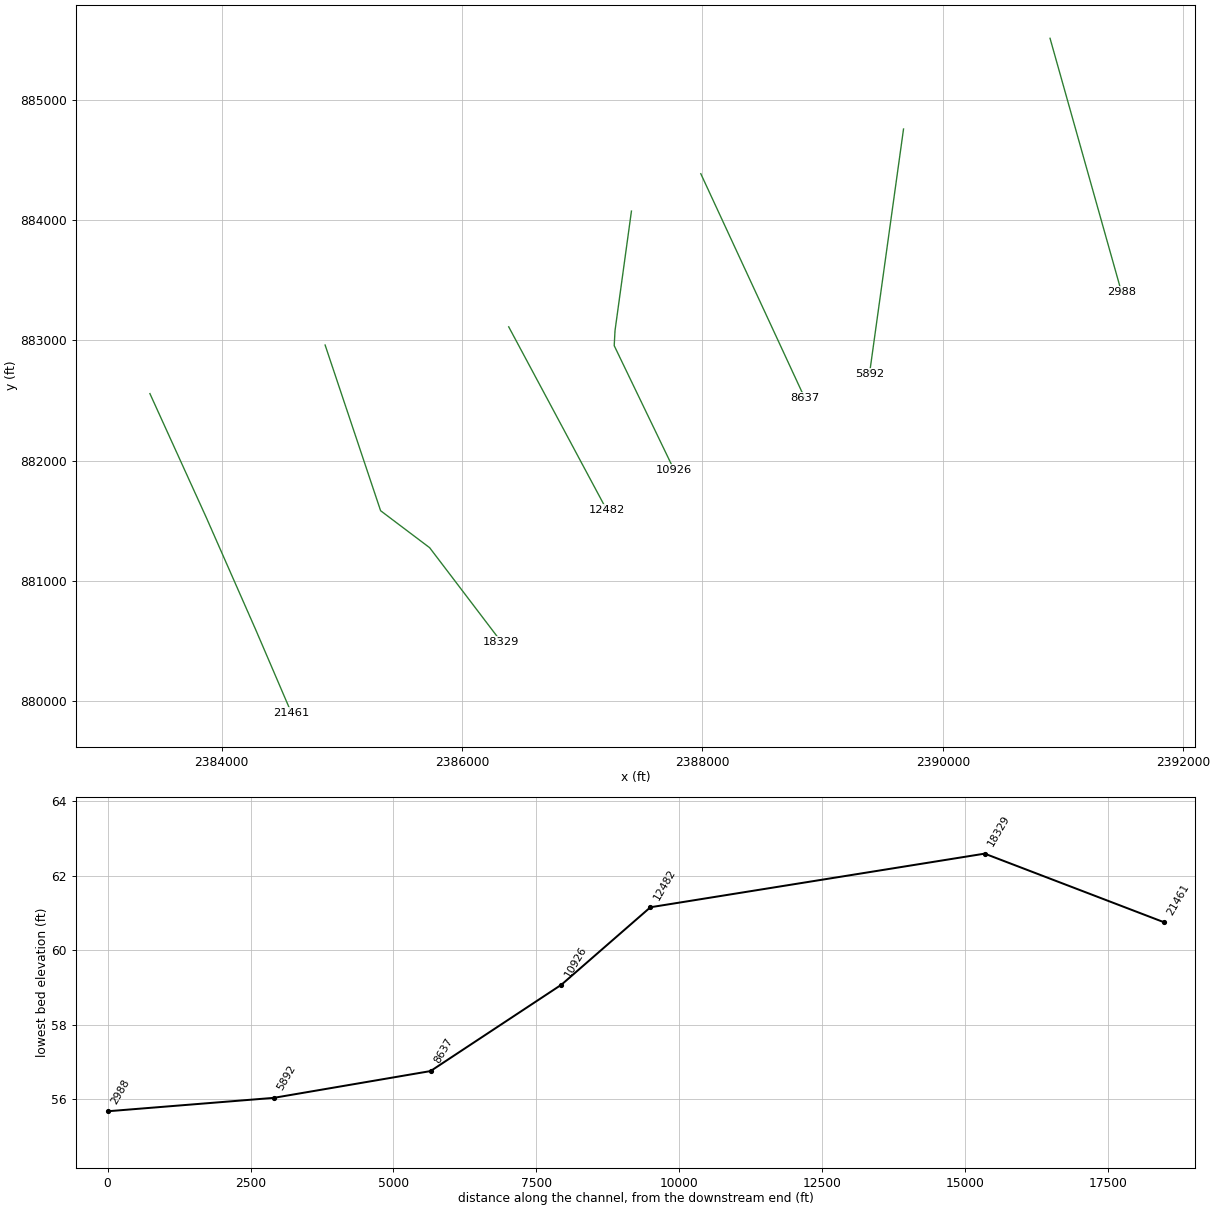
HEC-RAS study HighHillCreek.prj: S-21-356 over High Hill Creek

--- HighHillCreek.g04 (geometry) --- (continued)

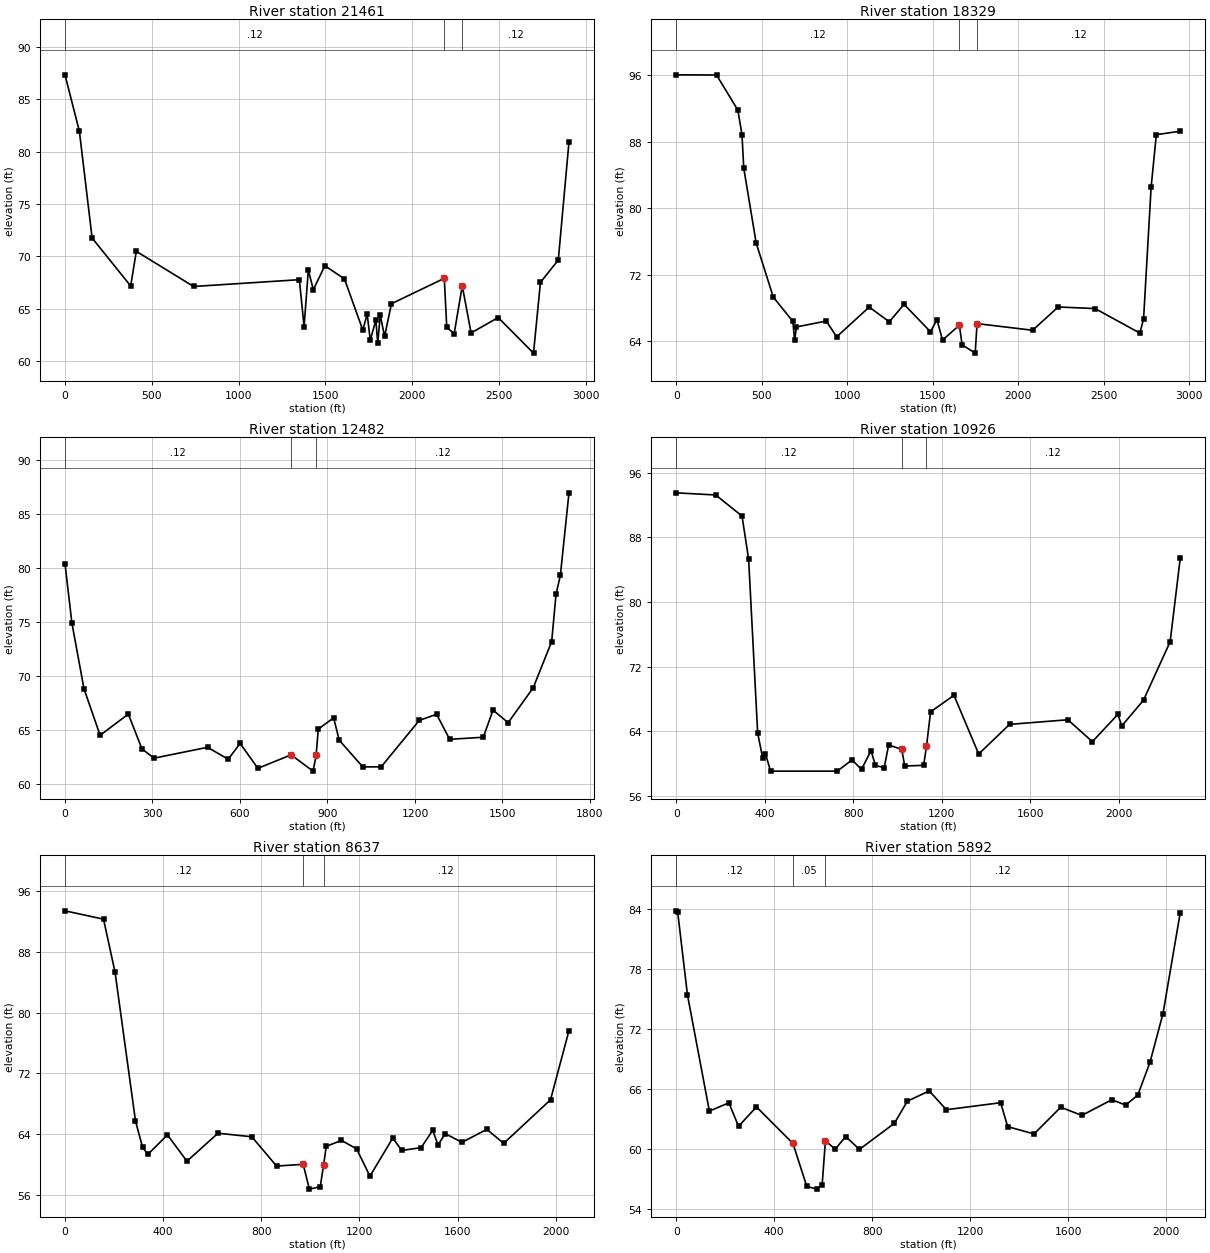
Type RM Length L Ch R = 1 ,21461   ,3132.3,3132.3,3132.3
XS GIS Cut Line= 4
2383403.76462963882557.2133575992383873.14596332881525.606967196
2384283.57575879880593.8006116932384580.68829309879901.898321468
#Sta/Elev= 30
       0   87.35   82.99   81.95  156.39   71.75  378.59   67.17  411.03   70.48
  741.09   67.12  1350.7   67.77 1377.94   63.29 1402.36   68.68 1431.21   66.82
  1497.7    69.1 1610.42   67.85 1716.41   62.95  1741.5   64.47 1759.43   61.99
  1791.7   63.91 1802.45   61.68 1816.79   64.38 1841.89   62.34 1881.33   65.47
 2185.94    67.9 2200.23    63.2 2243.08   62.62  2289.5   67.18 2340.39   62.68
 2496.61   64.15 2700.15   60.75 2740.09   67.51 2842.98   69.65 2904.56   80.93
#Mann= 3 ,-1,0
       0     .12       0 2185.94     .05       0  2289.5     .12       0
Bank Sta=2185.94,2289.5
XS Rating Curve= 0 ,0
Exp/Cntr(USF)=0,0
Exp/Cntr=0.3,0.1

Type RM Length L Ch R = 1 ,18329   ,5846.5,5846.5,5846.5
XS GIS Cut Line= 4
2384861.08884799882961.2116369842385322.65978337 881583.18826467
2385730.71524799881275.474307745 2386326.0748603880492.810547741
#Sta/Elev= 30
       0   96.06   235.8   96.04   360.4   91.82   384.6   88.85     395   84.83
   467.7   75.82   567.6   69.33   682.2    66.4   692.6   64.13     703   65.74
   877.6   66.45   938.3   64.55  1128.6   68.13  1246.2   66.36  1332.6   68.46
  1486.9   65.16    1525   66.62  1557.4   64.16  1655.8   65.94  1672.2   63.59
  1748.5   62.59  1759.4   66.14  2084.4   65.34  2233.9   68.14  2449.7   67.95
  2711.7      65  2733.4   66.71  2777.5   82.54    2808   88.862947.715   89.28
#Mann= 3 ,0,0
       0     .12       0  1655.8     .05       0  1759.4     .12       0
Bank Sta=1655.8,1759.4
XS Rating Curve= 0 ,0
Exp/Cntr(USF)=0,0
Exp/Cntr=0.3,0.1

Type RM Length L Ch R = 1 ,12482   ,1556,1556,1556
XS GIS Cut Line= 2
2386388.22568789883112.7701817712387203.92517011881589.386217271
#Sta/Elev= 30
       0   80.39    23.6   74.89    65.1   68.79   120.4   64.47   217.1   66.44
   263.9   63.21   305.1   62.35   488.8   63.36   559.6   62.25   600.5   63.72
   661.4   61.41   775.3   62.66   850.5   61.15     861    62.6   868.5   65.05
   921.1   66.09   940.2   64.02  1021.1   61.54  1084.3   61.55  1214.6   65.85
  1274.2   66.42  1318.8    64.1  1434.2   64.29  1467.7   66.81  1519.5   65.64
  1605.4   68.88  1668.7   73.16  1683.6   77.54  1698.5    79.31728.023   86.95
#Mann= 3 ,0,0
       0     .12       0   775.3     .05       0     861     .12       0
Bank Sta=775.3,861
XS Rating Curve= 0 ,0
Exp/Cntr(USF)=0,0
Exp/Cntr=0.3,0.1

Type RM Length L Ch R = 1 ,10926   ,2289.3,2289.3,2289.3
XS GIS Cut Line= 4
2387409.09703967884075.5545618532387272.55723904883082.227512276
2387265.73024901882955.928196694 2387764.1005213881921.639206928
#Sta/Elev= 30
       0   93.53   178.7   93.26   297.3   90.65   327.1   85.32     368   63.79
   390.1   60.75     403   61.24   426.2   59.07   727.9   59.07   794.1   60.46
   837.2   59.29   880.2   61.61   900.1   59.77   939.8    59.5   959.7   62.31
  1019.2   61.76  1032.3    59.7  1117.8   59.79  1130.7   62.12  1149.3   66.41
    1255   68.46  1366.6   61.19  1506.3   64.86  1769.7   65.43  1880.3   62.72
  1995.8    66.1    2013   64.66  2111.4   67.86  2231.8    75.12277.248   85.41
#Mann= 3 ,0,0
       0     .12       0  1019.2     .05       0  1130.7     .12       0
Bank Sta=1019.2,1130.7
XS Rating Curve= 0 ,0
Exp/Cntr(USF)=0,0
Exp/Cntr=0.3,0.1

Type RM Length L Ch R = 1 ,8637    ,2745.2,2745.2,2745.2
XS GIS Cut Line= 2
2387985.97769732884386.182608285 2388849.5919363882522.414329696
#Sta/Elev= 30
       0   93.43   157.1   92.33   204.1   85.33   287.3   65.74   316.3   62.25
   337.9   61.33   417.5    63.9     497   60.43   623.6   64.12   761.4   63.65
   862.5   59.79   970.8   60.02   996.1   56.75  1040.4   57.07  1053.9    59.9
  1064.8   62.39  1126.9   63.17  1188.7   62.05    1243   58.46    1336   63.49
  1372.2   61.85  1451.7   62.22  1498.7   64.51  1520.4   62.58  1549.7   64.06
  1618.1   62.92  1719.3   64.63    1788   62.78  1978.9   68.522054.133   77.64
#Mann= 3 ,0,0
       0     .12       0   970.8     .05       0  1053.9     .12       0
Bank Sta=970.8,1053.9
XS Rating Curve= 0 ,0
Exp/Cntr(USF)=0,0
Exp/Cntr=0.3,0.1

Type RM Length L Ch R = 1 ,5892    ,2903.6,2903.6,2903.6
XS GIS Cut Line= 2
 2389672.2442351884758.2535649992389388.92414879882720.397040608
#Sta/Elev= 30
       0   83.82     6.1   83.66    45.8   75.43   135.3   63.82   214.8   64.65
   254.5    62.3   327.4   64.24   476.5   60.59   532.8   56.31   573.5   56.03
   595.8   56.49     609   60.86   649.1   60.02   691.8   61.28   748.1      60
   890.5    62.6   943.6   64.81    1033   65.84  1102.6   63.96  1324.5   64.66
    1353   62.27  1460.6   61.54  1569.7   64.21  1655.8   63.39  1778.4   64.96
  1834.7   64.42  1884.4   65.43  1934.1    68.7  1987.1   73.562057.457   83.62
#Mann= 3 ,0,0
       0     .12       0   476.5     .05       0     609     .12       0
Bank Sta=476.5,609
XS Rating Curve= 0 ,0
Exp/Cntr(USF)=0,0
Exp/Cntr=0.3,0.1

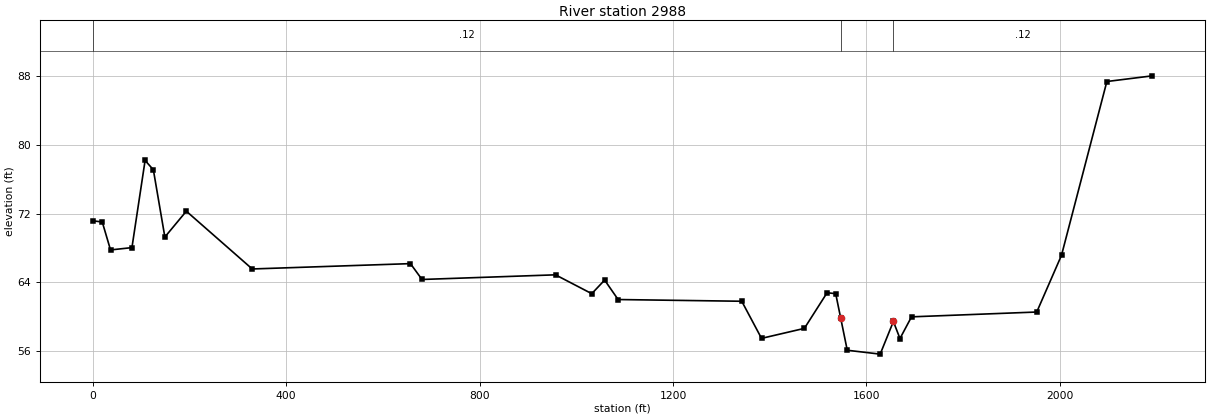
Type RM Length L Ch R = 1 ,2988    ,,,
XS GIS Cut Line= 2
2390890.86195571885512.6359634752391484.81008845883403.096043754
#Sta/Elev= 30
       0   71.15    19.6   71.02    36.7   67.77      81   68.04   108.2   78.16
   125.3   77.08   149.1   69.27   193.5   72.27   329.8   65.56     657   66.18
   680.9   64.34     957   64.88    1032   62.69  1058.6   64.27  1086.5   62.01
  1342.2   61.81  1383.1    57.5  1471.7   58.66  1518.7    62.8  1536.5   62.69
  1546.7   59.89  1560.4   56.12  1628.5   55.67  1655.8   59.46  1669.4   57.48
  1693.3      60  1952.3   60.56  2003.5   67.15  2097.3   87.33 2191.56   87.99
#Mann= 3 ,0,0
       0     .12       0  1546.7     .05       0  1655.8     .12       0
Bank Sta=1546.7,1655.8
XS Rating Curve= 0 ,0
Exp/Cntr(USF)=0,0
Exp/Cntr=0.3,0.1
LCMann Table=0

--- HighHillCreek.g05 (geometry) ---

Geom Title=Proposed - SCDOT
Program Version=6.60

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
River Reach=High Hill Creek ,Reach 1
Reach XY= 30
2363243.59977666883095.1585389252366434.63516231 881068.63046019
2368423.81331766881275.8878175882370371.18916704880731.220620871
     2371160.465     881197.2497     2373858.439     880222.0221
2377959.08395706879888.1722408542378179.99401003879371.546614335
2379704.15649189879174.0132865482379662.07838656878643.361624919
2382002.04649912877858.6026855812384092.27638126880436.938589516
2384750.79872963880744.1087584062385524.28947058880225.906608263
2385426.88644899881376.5609699932386745.53589587881203.803959342
2386221.72409087881444.7862497972386368.91087905882130.214920252
2385575.25662905881669.8954552522385823.45395814882423.145488889
 2386858.0904986882431.8035352532386770.06702723883213.913723436
2387982.19351815882688.6589107082389005.59890139884108.415479815
2388592.61008984884416.209028043 2390010.7980842883647.374510951
2390354.95542716884088.9348754972390604.30716243883562.958558905
2391538.07746275884399.325837634 2393610.0421929884237.968149105

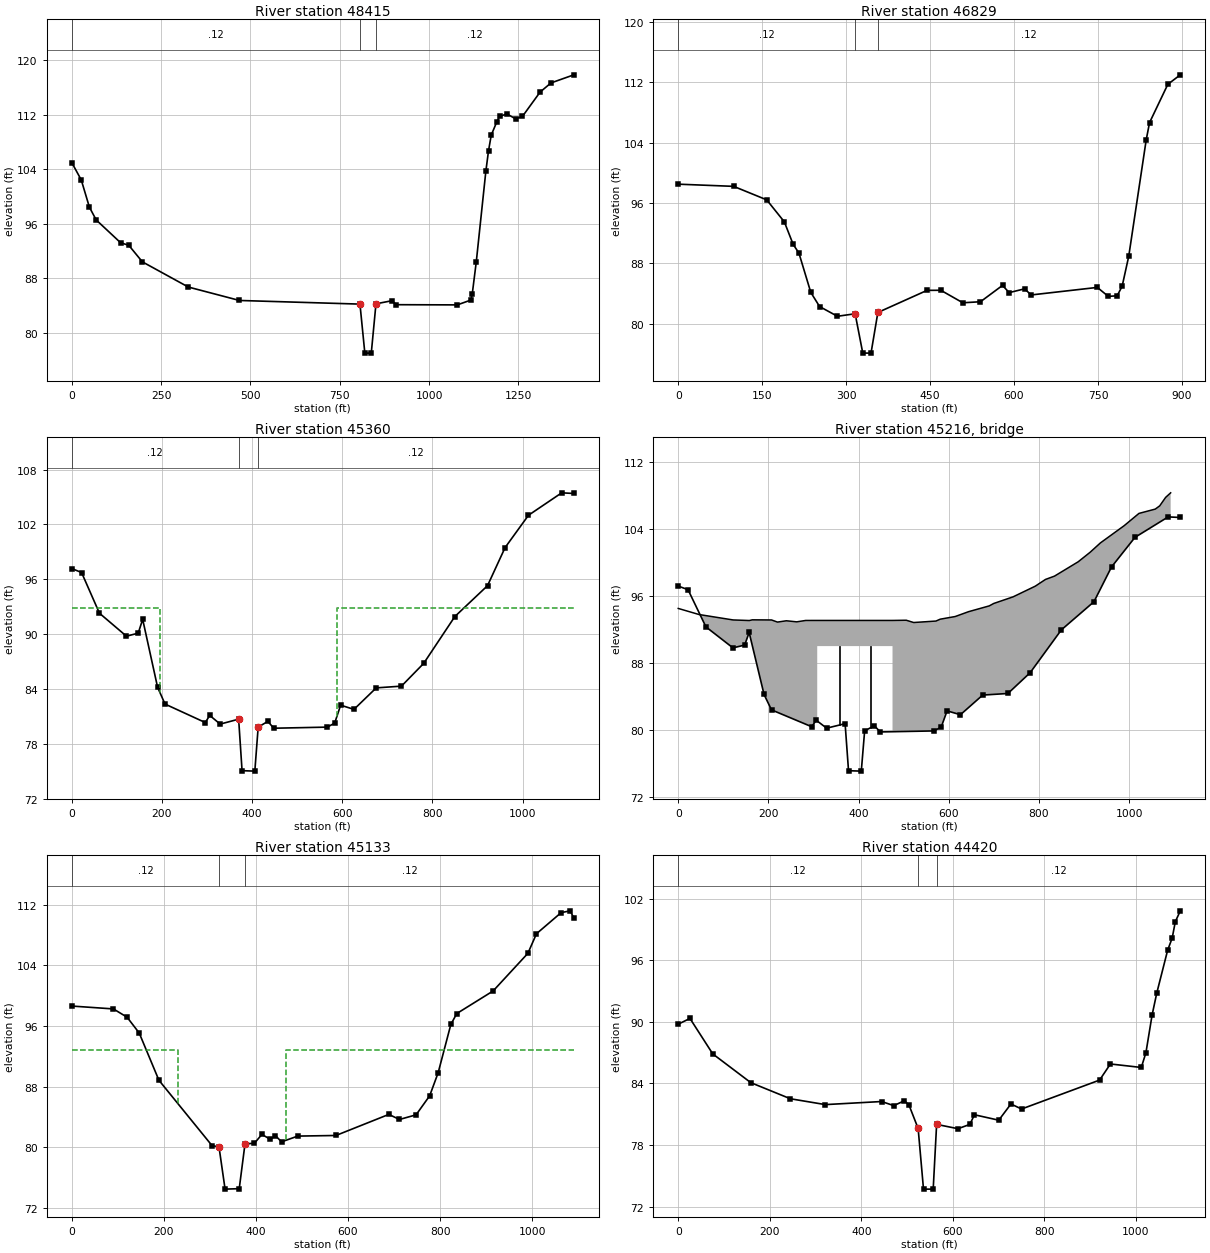
Type RM Length L Ch R = 1 ,48415   ,1585.7,1585.7,1585.7
XS GIS Cut Line= 2
  2365371.411892882855.6956462862364662.86671036 881642.17983147
#Sta/Elev= 30
       0  104.97   26.57  102.42   49.36   98.42   68.36   96.55  136.75    93.2
  159.55   92.83  197.54    90.4   326.2    86.7  469.36   84.73   806.6  84.195
  820.25      77  838.26      77   851.4  84.236  896.65    84.7  908.05   84.11
 1079.02   84.08 1117.02   84.79 1120.82   85.66 1132.21   90.43 1158.93   103.7
 1166.41   106.7 1174.01     109 1189.21   110.9 1197.31  111.74  1217.7  112.11
  1242.4  111.39  1261.4  111.75 1310.79  115.32 1341.19  116.66 1405.22  117.85
#Mann= 3 ,0,0
       0     .12       0   806.6     .05       0   851.4     .12       0
Bank Sta=806.6,851.4
XS Rating Curve= 0 ,0
Exp/Cntr(USF)=0,0
Exp/Cntr=0.3,0.1

Type RM Length L Ch R = 1 ,46829   ,1469.3,1469.3,1469.3
XS GIS Cut Line= 2
2366204.20714159881740.5968944942365708.08189925880993.145049117
#Sta/Elev= 30
       0    98.5   99.01   98.21  158.08   96.42  189.58    93.5  205.34   90.51
  215.59   89.37  236.84   84.14  252.59   82.26  284.44   80.97   316.1  81.304
  329.72   76.09  344.47   76.08   356.7  81.476  444.64   84.41  469.19   84.42
  508.57   82.76  540.08    82.9  579.46   85.07  591.27   84.11  618.84   84.61
  630.65    83.8   748.8    84.8  768.49   83.61  784.24   83.69  793.15   84.95
  804.98   88.94  836.22   104.4  842.16  106.67  874.82  111.75  897.12  113.01
#Mann= 3 ,0,0
       0     .12       0   316.1     .05       0   356.7     .12       0
Bank Sta=316.1,356.7
XS Rating Curve= 0 ,0
Exp/Cntr(USF)=0,0
Exp/Cntr=0.5,0.3

Type RM Length L Ch R = 1 ,45360   ,227.2,227.2,227.2
XS GIS Cut Line= 4
 2366924.9056944881522.1839907562366884.43137281881190.680023462
2366861.30318904 880969.034929052366818.90151881880413.958518697
#Sta/Elev= 30
       0   97.18   21.73   96.75    61.4    92.3  121.27   89.79  147.34   90.12
  157.26   91.63  190.31   84.21  206.84   82.37  296.09   80.35     306   81.13
  329.14   80.18   370.1  80.719  377.67   75.09  405.99   75.04   413.4   79.85
  434.92   80.48  447.91   79.73  566.65   79.85   583.1   80.29  596.27   82.25
  625.88   81.79  675.24   84.14  731.18   84.33  780.55   86.82  849.65   91.94
  922.04   95.31  960.96   99.47 1012.93  103.01 1086.58  105.46 1113.51  105.39
#Mann= 3 ,0,0
       0     .12       0   370.1     .05       0   413.4     .12       0
#XS Ineff= 2 , 0
       0  195.75   92.88  587.75       0   92.82
Permanent Ineff=
       F       F
Bank Sta=370.1,413.4
XS Rating Curve= 0 ,0
Exp/Cntr(USF)=0,0
Exp/Cntr=0.5,0.3

Type RM Length L Ch R = 3 ,45216   ,,,
Bridge Culvert--1,0,-1,-1, 0
Deck Dist Width WeirC Skew NumUp NumDn MinLoCord MaxHiCord MaxSubmerge Is_Ogee
112.5,46.5,2.6,0, 35, 32, , , 0.98, 0, 2,2,,
       0  45.978 121.546 157.687 164.258  206.97 220.113 239.826 262.695 282.532
  308.24  308.25  475.25  475.26 505.742  522.19 571.534 581.025 614.266 643.847
 689.806 699.653 742.362 791.735 814.533 834.493 887.096 913.378 936.375 988.939
1021.7921057.9291067.7851080.9261092.095
  94.506  93.781  93.131   93.06  93.144  93.128  92.875  93.031  92.904  93.068
   93.07   93.07   93.07   93.07  93.095  92.822  92.998  93.222   93.54  94.119
  94.813  95.101  95.888  97.169  97.979  98.375 100.093 101.224 102.352 104.408
 105.878 106.394 106.782 107.793  108.34
                                                                                
              90      90
                                                                                
                                        
       0  45.978 121.546 157.687 164.258  206.97 220.113  264.54  264.55  431.55
  431.56 505.742  522.19 571.534 581.025 614.266 643.847 689.806 699.653 742.362
 791.735 814.533 834.493 887.096 913.378 936.375 988.9391021.7921057.9291067.785
1080.9261092.095
  94.506  93.781  93.131   93.06  93.144  93.128  92.875   93.07   93.07   93.07
   93.07  93.095  92.822  92.998  93.222   93.54  94.119  94.813  95.101  95.888
  97.169  97.979  98.375 100.093 101.224 102.352 104.408 105.878 106.394 106.782
 107.793  108.34
                                                                      90      90
                                                                                
                                                                                
                
Pier Skew, UpSta & Num, DnSta & Num=  ,357.25, 2 ,313.55, 2 , 0 , 0 , 0 ,,
       3       3
       0      91
       3       3
       0      91
Pier Skew, UpSta & Num, DnSta & Num=  ,426.25, 2 ,382.55, 2 , 0 , 0 , 0 ,,
       3       3
       0      91
       3       3
       0      91
Abutment Skew #Up #Dn= , 2 , 2
  308.25  328.25
      89      69
  264.55  284.55
      89      69
Abutment Skew #Up #Dn= , 2 , 2
  455.25  475.25
      69      89
  411.55  431.55
      69      89
BR Coef=-1 , 0 , 0 ,, 0 ,,,0.8,0,,0,
WSPro=,,,, 1 ,,,, 0 ,,,, 0 ,,,,-1 ,-1 ,-1 , 0 , 0 , 0 , 0 , 0
BC Design=,, 0 ,, 0 ,,,,,,
BC Use User HTab Curves=0
BC User HTab FreeFlow(D)= 0

Type RM Length L Ch R = 1 ,45133   ,713,713,713
XS GIS Cut Line= 4
 2367055.9654024881508.6925502272367082.94828345881204.171463991
2367063.67479698880670.2958887562367067.52949428880419.740564638
#Sta/Elev= 30
       0   98.63   90.46   98.25  120.11   97.16  146.46   95.08  189.28   88.85
  304.57   80.24   319.8  80.066  332.97    74.5  363.73   74.56   376.3  80.485
   396.5   80.53  412.92   81.71  431.38   81.06  442.47   81.55   455.6   80.73
  490.81   81.49   573.8   81.57  688.72   84.35   711.7   83.68  747.81   84.29
  777.36    86.8  795.85   89.85  823.33    96.2  836.22   97.64  915.22  100.62
   990.7  105.58 1009.33  108.16 1062.89  110.94 1082.58  111.18 1090.52  110.23
#Mann= 3 ,0,0
       0     .12       0   319.8     .05       0   376.3     .12       0
#XS Ineff= 2 , 0
       0  230.45   92.88  465.65       0   92.82
Permanent Ineff=
       F       F
Bank Sta=319.8,376.3
XS Rating Curve= 0 ,0
Exp/Cntr(USF)=0,0
Exp/Cntr=0.5,0.3

Type RM Length L Ch R = 1 ,44420   ,501.1,501.1,501.1
XS GIS Cut Line= 3
 2367809.5587234 881624.333469052367670.78962081880774.372715697
2367726.68273157880545.018226697
#Sta/Elev= 30
       0   89.78   25.62   90.34   75.49   86.88   158.6   84.08  245.04   82.51
  321.51   81.94  444.52   82.24  471.11   81.84  494.39   82.32  504.36   81.89
   524.3  79.611  536.02    73.7  557.22    73.7   564.7  80.012  611.36   79.59
  637.34   80.01  647.32   80.95  700.51   80.42  727.11      82  750.38   81.51
  920.86   84.33   944.5    85.9 1012.04   85.56 1022.17   87.01 1035.68   90.69
 1045.81   92.81 1069.45   96.97 1079.59   98.19 1086.34   99.77 1097.28  100.83
#Mann= 3 ,0,0
       0     .12       0   524.3     .05       0   564.7     .12       0
Bank Sta=524.3,564.7
XS Rating Curve= 0 ,0
Exp/Cntr(USF)=0,0
Exp/Cntr=0.3,0.1

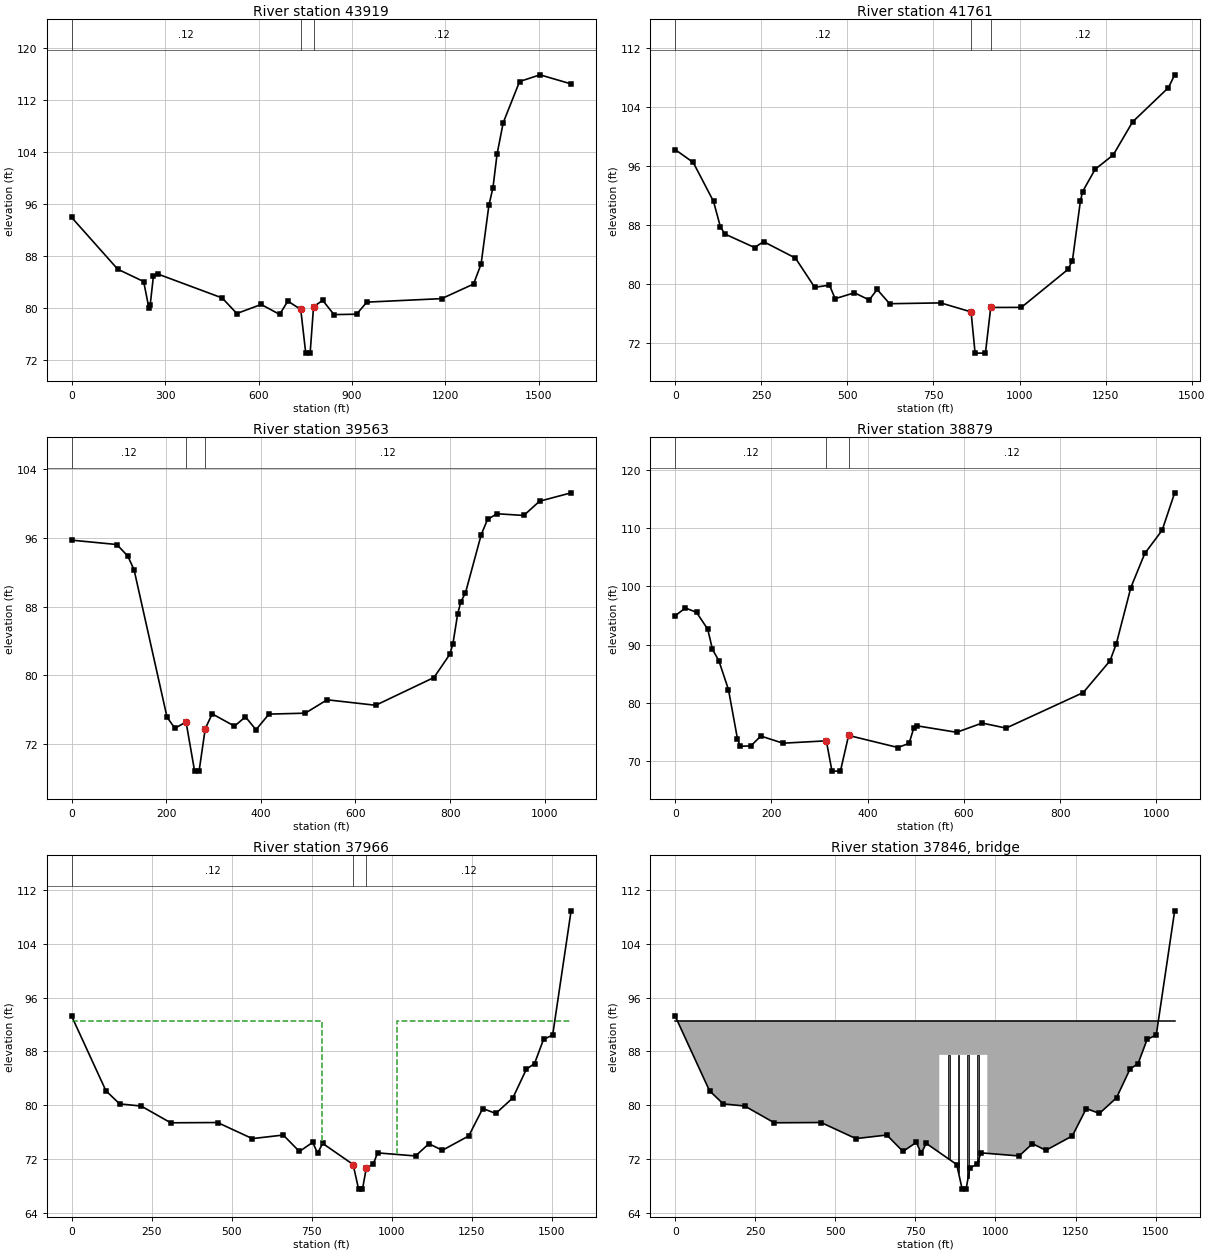
Type RM Length L Ch R = 1 ,43919   ,2157.9,2157.9,2157.9
XS GIS Cut Line= 4
2368289.25326603881857.0929439242368202.21374983881603.227688338
2368111.54758712880515.233735824 2368104.2942941880272.248419762
#Sta/Elev= 30
       0   93.99  147.92   86.02  231.17   84.12   248.1   80.03  251.98   80.44
  262.38    84.9  275.86   85.29  483.29   81.59  530.21    79.2   608.4   80.59
  667.67   79.06  694.01   81.11   735.4  79.824  751.46    73.1   765.6    73.1
   776.5  80.252  805.95   81.22  842.17   79.03   914.6   79.09  947.53   80.95
 1187.88   81.49 1290.02   83.73 1314.34   86.81 1339.34   95.84 1352.51   98.59
 1365.66  103.75 1385.36  108.57 1437.88  114.91 1503.53  115.94 1603.23  114.54
#Mann= 3 ,0,0
       0     .12       0   735.4     .05       0   776.5     .12       0
Bank Sta=735.4,776.5
XS Rating Curve= 0 ,0
Exp/Cntr(USF)=0,0
Exp/Cntr=0.3,0.1

Type RM Length L Ch R = 1 ,41761   ,2198.1,2198.1,2198.1
XS GIS Cut Line= 2
2369765.29839494881864.3462369412369620.23253461880420.940926606
#Sta/Elev= 30
       0    98.2   52.29   96.46  111.23   91.18  131.43   87.69  144.62   86.75
  230.36   84.93  256.74   85.72  349.08    83.5  405.14   79.53  448.01   79.83
  464.49   77.99  520.55   78.79  563.42   77.82  586.51   79.24  622.78   77.31
  771.18   77.42   859.3    76.2  870.98   70.61  901.03   70.61   916.4    76.8
 1005.31   76.81 1140.51   81.95 1153.71   83.15 1176.79   91.21 1183.38   92.52
 1219.66   95.53 1272.42   97.49 1328.48  101.96 1432.69  106.61 1450.68  108.34
#Mann= 3 ,0,0
       0     .12       0   859.3     .05       0   916.4     .12       0
Bank Sta=859.3,916.4
XS Rating Curve= 0 ,0
Exp/Cntr(USF)=0,0
Exp/Cntr=0.3,0.1

Type RM Length L Ch R = 1 ,39563   ,683.4,683.4,683.4
XS GIS Cut Line= 3
2371427.57182206881401.5498760072371336.50672823880778.782137588
2371263.06713644880358.707672522
#Sta/Elev= 30
       0   95.74   95.53   95.23  118.74   93.88     132   92.28  201.68   75.09
  218.22    73.8   241.9  74.526  259.96    68.8  269.43    68.8   282.4  73.736
  297.08   75.48  344.23   74.05  367.44   75.13  389.66   73.63  417.18   75.45
   493.8   75.56  540.09   77.12  642.73   76.48  765.97   79.72  799.28   82.41
  805.95   83.63  815.94   87.09   822.6   88.53  832.59    89.6   865.9   96.39
  879.23   98.16  899.21   98.82  955.84   98.62  989.14  100.28 1055.84  101.26
#Mann= 3 ,0,0
       0     .12       0   241.9     .05       0   282.4     .12       0
Bank Sta=241.9,282.4
XS Rating Curve= 0 ,0
Exp/Cntr(USF)=0,0
Exp/Cntr=0.3,0.1

Type RM Length L Ch R = 1 ,38879   ,912.8,912.8,912.8
XS GIS Cut Line= 3
2371991.58788704881331.0478678842371903.46037689880775.844553916
2371915.21071157880299.955999086
#Sta/Elev= 30
       0   94.95      21    96.3   44.25   95.54   67.51   92.65   77.48   89.15
   90.77    87.2   110.7   82.22   129.3   73.79  135.04   72.47  157.21   72.54
  178.04   74.23  223.92      73  314.12   73.41  325.86   68.19   343.4   68.19
   360.4  74.337  462.85   72.26  486.11   72.97  496.07   75.66  502.72   75.99
  585.19   74.88     638   76.47  687.68    75.6  848.06   81.72  903.86    87.2
  916.98   90.16  947.13   99.82  976.06  105.69 1012.17  109.69 1038.19  116.13
#Mann= 3 ,0,0
       0     .12       0  314.12     .05       0   360.4     .12       0
Bank Sta=314.12,360.4
XS Rating Curve= 0 ,0
Exp/Cntr(USF)=0,0
Exp/Cntr=0.5,0.3

Type RM Length L Ch R = 1 ,37966   ,293.5,293.5,293.5
XS GIS Cut Line= 4
 2373212.5198401881341.6548465152373196.92097123881125.639110115
2372501.97479952880506.9903224492372197.91797148880228.048851198
#Sta/Elev= 30
       0   93.25  107.09   82.16  149.86   80.21  217.15   79.89   309.4    77.4
   455.6   77.44  564.19   75.05  660.84   75.58  711.24   73.14  753.06    74.5
  767.87   72.86  783.84   74.34     879    71.2  896.02   67.54  908.25   67.54
   920.1  70.674  941.98   71.25  955.16   72.93 1073.82   72.47 1115.62   74.29
 1157.53   73.31 1240.04   75.45 1283.72   79.52 1324.65   78.79 1378.06   81.12
 1420.08   85.38 1445.41    86.2 1473.51   89.79 1502.14   90.46 1559.62  108.91
#Mann= 3 ,0,0
       0     .12       0     879     .05       0   920.1     .12       0
#XS Ineff= 2 , 0
       0  782.55    92.6 1016.55       0    92.6
Permanent Ineff=
       F       F
Bank Sta=879,920.1
XS Rating Curve= 0 ,0
Exp/Cntr(USF)=0,0
Exp/Cntr=0.5,0.3

Type RM Length L Ch R = 3 ,37846   ,,,
Bridge Culvert--1,0,-1,-1, 0
Deck Dist Width WeirC Skew NumUp NumDn MinLoCord MaxHiCord MaxSubmerge Is_Ogee
42,145.7,2.6,0, 6, 6, , , 0.98, 0, 2,2,,
       0  824.54  824.55  974.55  974.56 1559.62
    92.6    92.6    92.6    92.6    92.6    92.6
                    87.5    87.5
       0 1035.29  1035.3  1185.3 1185.31 1792.15
    92.6    92.6    92.6    92.6    92.6    92.6
                    87.5    87.5
Pier Skew, UpSta & Num, DnSta & Num=  ,854.55, 2 ,1065.3, 2 , 0 , 0 , 0 ,,
       5       5
    67.5    87.5
       5       5
    67.5    87.5
Pier Skew, UpSta & Num, DnSta & Num=  ,884.55, 2 ,1095.3, 2 , 0 , 0 , 0 ,,
       5       5
    67.5    87.5
       5       5
    67.5    87.5
Pier Skew, UpSta & Num, DnSta & Num=  ,914.55, 2 ,1125.3, 2 , 0 , 0 , 0 ,,
       5       5
    67.5    87.5
       5       5
    67.5    87.5
Pier Skew, UpSta & Num, DnSta & Num=  ,944.55, 2 ,1155.3, 2 , 0 , 0 , 0 ,,
       5       5
    67.5    87.5
       5       5
    67.5    87.5
Abutment Skew #Up #Dn= , 2 , 2
  824.55  844.55
    86.5    66.5
 1035.29  1055.3
    86.5    66.5
Abutment Skew #Up #Dn= , 2 , 2
  954.55  974.55
    66.5    86.5
  1165.3 1185.29
    66.5    86.5
BR Coef=-1 , 0 , 0 ,, 0 ,,,0.8,0,,0,
WSPro=,,,, 1 ,,,, 0 ,,,, 0 ,,,,-1 ,-1 ,-1 , 0 , 0 , 0 , 0 , 0
BC Design=,, 0 ,, 0 ,,,,,,
BC Use User HTab Curves=0
BC User HTab FreeFlow(D)= 0

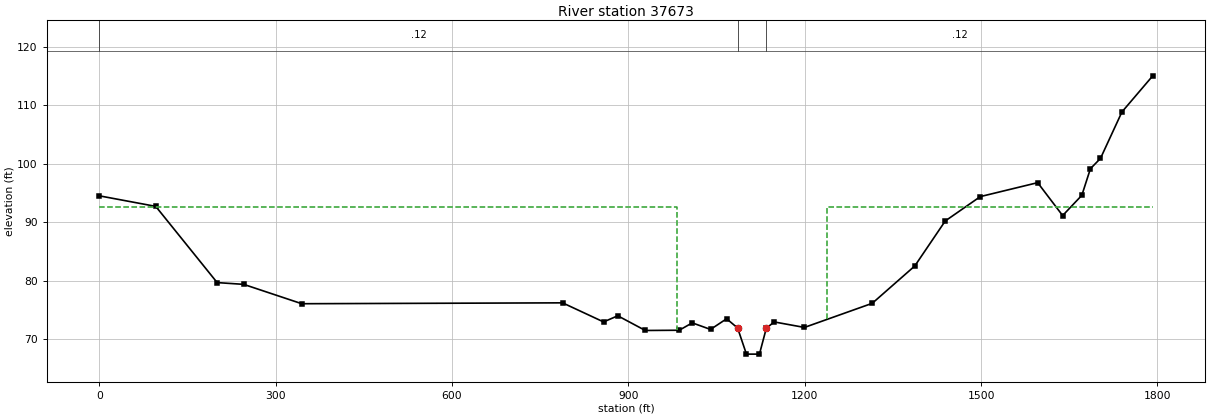
Type RM Length L Ch R = 1 ,37673   ,1206.5,1206.5,1206.5
XS GIS Cut Line= 2
2373715.94950238881228.2324393712372390.84181334880021.633565704
#Sta/Elev= 30
       0   94.54   95.93   92.74  200.45   79.72  245.47   79.42  344.45   76.11
  788.08   76.26  857.86      73  882.02   74.05  928.86   71.54  986.55   71.58
 1008.73   72.84  1039.8   71.72 1067.21   73.54  1085.971.96136 1100.88    67.5
 1123.05    67.5  1134.771.91929 1148.09      73 1199.55   72.06 1314.93   76.18
 1387.32   82.56 1439.18   90.25 1498.81   94.41 1596.36   96.79 1638.87   91.17
 1671.51   94.63 1686.13   99.18 1703.21  100.93 1739.74  108.87 1792.15  115.04
#Mann= 3 ,0,0
       0     .12       0  1085.9     .05       0  1134.7     .12       0
#XS Ineff= 2 , 0
       0   982.4    92.6  1238.2       0    92.6
Permanent Ineff=
       F       F
Bank Sta=1085.9,1134.7
XS Rating Curve= 0 ,0
Exp/Cntr(USF)=0,0
Exp/Cntr=0.5,0.3