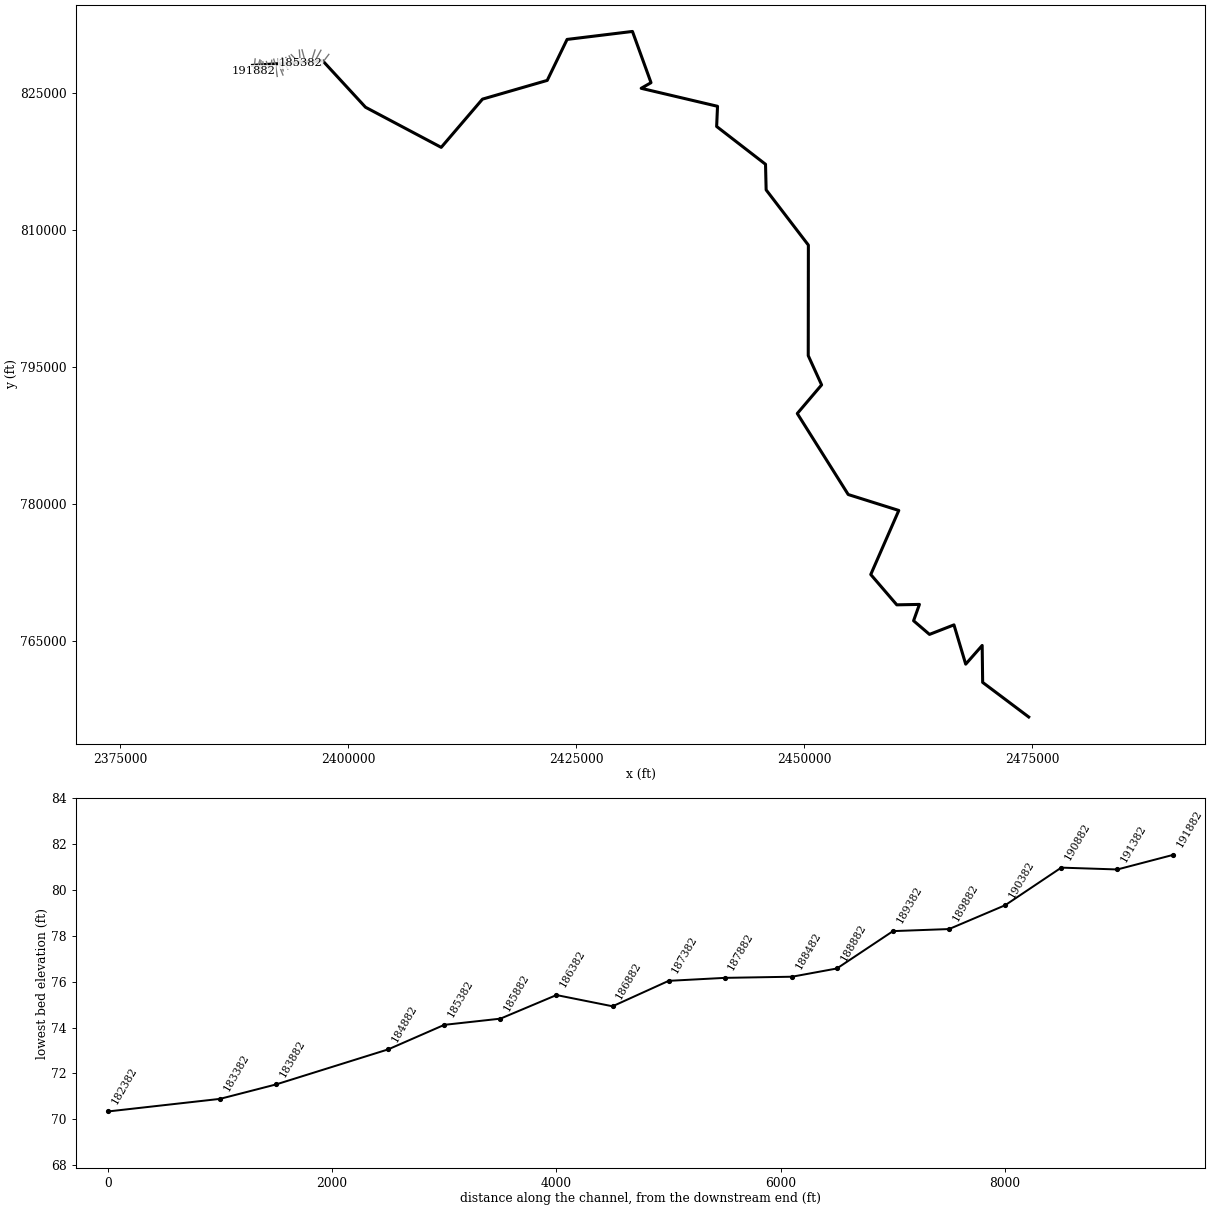
--- WillowCreek.prj (project) ---

Proj Title=S-21-57 over Willow Creek
Current Plan=p11
Default Exp/Contr=0.3,0.1
English Units
Geom File=g02
Geom File=g03
Geom File=g07
Geom File=g01
Flow File=f01
Flow File=f03
Flow File=f08
Flow File=f09
Flow File=f02
Flow File=f04
Plan File=p01
Plan File=p02
Plan File=p11
Plan File=p12
Plan File=p13
Plan File=p15
Plan File=p19
Plan File=p21
Plan File=p04
Plan File=p05
Y Axis Title=Elevation
X Axis Title(PF)=Main Channel Distance
X Axis Title(XS)=Station
BEGIN DESCRIPTION:
END DESCRIPTION:
DSS File=dss
DSS Export Rating Curves= 0
DSS Export Rating Curve Sorted= 0
DSS Export Volume Flow Curves= 0
DXF OffsetX= 0
DXF OffsetY= 0
DXF ScaleX= 1
DXF ScaleY= 10
Specific Locations Profile Table=U/S WSE Comparison                   , 13
Willow Creek    ,Reach-1         ,138482
Willow Creek    ,Reach-1         ,138082
Willow Creek    ,Reach-1         ,137482
Willow Creek    ,Reach-1         ,136882
Willow Creek    ,Reach-1         ,136382
Willow Creek    ,Reach-1         ,135882
Willow Creek    ,Reach-1         ,135282
Willow Creek    ,Reach-1         ,134882
Willow Creek    ,Reach-1         ,134382
Willow Creek    ,Reach-1         ,133982
Willow Creek    ,Reach-1         ,132982
Willow Creek    ,Reach-1         ,132481
Willow Creek    ,Reach-1         ,132132
Specific Locations Profile Table=Output                               , 37
Willow Creek    ,Reach-1         ,150082
Willow Creek    ,Reach-1         ,149482
Willow Creek    ,Reach-1         ,148882
Willow Creek    ,Reach-1         ,148382
Willow Creek    ,Reach-1         ,147982
Willow Creek    ,Reach-1         ,147482
Willow Creek    ,Reach-1         ,146982
Willow Creek    ,Reach-1         ,146482
Willow Creek    ,Reach-1         ,145882
Willow Creek    ,Reach-1         ,145382
Willow Creek    ,Reach-1         ,144882
Willow Creek    ,Reach-1         ,144382
Willow Creek    ,Reach-1         ,143882
Willow Creek    ,Reach-1         ,143382
Willow Creek    ,Reach-1         ,142882
Willow Creek    ,Reach-1         ,142282
Willow Creek    ,Reach-1         ,141382
Willow Creek    ,Reach-1         ,140882
Willow Creek    ,Reach-1         ,140382
Willow Creek    ,Reach-1         ,139582
Willow Creek    ,Reach-1         ,139082
Willow Creek    ,Reach-1         ,138482
Willow Creek    ,Reach-1         ,138082
Willow Creek    ,Reach-1         ,137482
Willow Creek    ,Reach-1         ,136882
Willow Creek    ,Reach-1         ,136382
Willow Creek    ,Reach-1         ,135882
Willow Creek    ,Reach-1         ,135282
Willow Creek    ,Reach-1         ,134882
Willow Creek    ,Reach-1         ,134382
Willow Creek    ,Reach-1         ,133982
Willow Creek    ,Reach-1         ,132982
Willow Creek    ,Reach-1         ,132481
Willow Creek    ,Reach-1         ,132132
Willow Creek    ,Reach-1         ,132026
Willow Creek    ,Reach-1         ,131974
Willow Creek    ,Reach-1         ,131455

--- WillowCreek.p11 (plan) ---

Plan Title=Existing Condition - Willow Peak
Program Version=6.60
Short Identifier=EX_WILLOW_PEAK
Geom File=g02
Flow File=f08
Subcritical Flow
K Sum by GR= 0
Std Step Tol= 0.01
Critical Tol= 0.01
Num of Std Step Trials= 20
Max Error Tol= 0.3
Flow Tol Ratio= 0.001
Split Flow NTrial= 30
Split Flow Tol= 0.02
Split Flow Ratio= 0.02
Log Output Level= 0
Friction Slope Method= 1
Unsteady Friction Slope Method= 2
Unsteady Bridges Friction Slope Method= 1
Parabolic Critical Depth
Global Vel Dist= 0 , 0 , 0
Global Log Level= 0
CheckData=True
Encroach Param=-1 ,0,0, 0
Flow Ratio Tolerance=0.1
Flow Ratio Min Ratio=0.5
Flow Ratio Max Ratio=4
Flow Ratio Max Iterations= 10
BEGIN DESCRIPTION:
PLAN USED IN HYDRAULIC ANALYSIS
Flowrates for Willow Creek and Jeffries Creek calculated using USGS Regression Equations published in SIR 2023-5006.  Flowrates for the Great Pee Dee River calculated by performing a Log-Pearson Type III analysis using USGS Streamgage 02131000.  The flow file used in this analysis consists of flowrates along Jeffries Creek and the Great Pee Dee River when Willow Creek peaks, which is approximately 32 hours after initial rainfall.
END DESCRIPTION:
Computation Interval=1MIN
Output Interval=1HOUR
Instantaneous Interval=1HOUR
Mapping Interval=1HOUR
Computation Time Step Use Courant=        0
Computation Time Step Use Time Series=    0
Computation Time Step Count To Double=0
Computation Time Step Max Doubling=0
Computation Time Step Max Halving=0
Computation Time Step Residence Courant=0
Run HTab= 0
Run UNet= 0
Run Sediment= 0
Run PostProcess= 0
Run WQNet= 0
Run RASMapper= 0
UNET Theta= 1
UNET Theta Warmup= 1
UNET ZTol= 0.02
UNET ZSATol= 0.02
UNET MxIter= 20
UNET Max Iter WO Improvement= 0
UNET MaxInSteps= 0
UNET DtIC= 0
UNET DtMin= 0
UNET MaxCRTS= 20
UNET WFStab= 2
UNET SFStab= 1
UNET WFX= 1
UNET SFX= 1
UNET Gravity=32.17405
UNET 1D Methodology=Finite Difference
UNET DSS MLevel= 4
UNET Pardiso=0
UNET DZMax Abort= 100
UNET Use Existing IB Tables=-1
UNET Froude Reduction=False
UNET Froude Limit= 0.8
UNET Froude Power= 4
UNET D1 Cores= 0
UNET WindReference=Eulerian
UNET WindDragFormulation=Hsu (1988)
UNET D2 Coriolis=0
UNET D2 Cores= 0
UNET D2 Theta= 1
UNET D2 Theta Warmup= 1
UNET D2 Z Tol= 0.01
UNET D2 Volume Tol= 0.01
UNET D2 Max Iterations= 20
UNET D2 Advanced Convergence=0
UNET D2 WS Max Tol=0.15
UNET D2 WS RMS Tol=0.002
UNET D2 WS Stall Tol=1
UNET D2 Equation= 0
UNET D2 RampUpFraction=0.1
UNET D2 TimeSlices= 1
UNET D2 Turbulence Formulation=None
UNET D2 Eddy Viscosity=0.3
UNET D2 Transverse Eddy Viscosity=0.1
UNET D2 Smagorinsky Mixing=0.05
UNET D2 BCVolumeCheck=0
UNET D2 Cores=0
UNET D2 SolverType=PARDISO (Direct)
UNET D2 Minimum Iterations= 3
UNET D2 Maximum Iterations= 30
UNET D2 Restart Number= 10
UNET D2 Relaxation Coeff=1.3
UNET D2 SOR Precondition Iterations= 10
UNET D2 ILUT Maximum Fill= 8
UNET D2 ILUT Tolerance=1E-08
UNET D2 Convergence Tolerance=0.00001
PS Theta= 1
PS WS Tol= 0.01
PS Volume Tol= 0.01
PS Max Iterations= 20
PS Equation= 0
PS Advance Time Step=-1
PS Target Courant=0.9
PS Time Slices= 1
PS Iterate With 2D=0
PS Project Initial WSE from DS=-1
PS Ramp Up Initial WSE from US=-1
PS Cores=0
UNET D1D2 MaxIter= 0
UNET D1D2 ZTol=0.01
UNET D1D2 QTol=0.1
UNET D1D2 MinQTol=1
DSS File=dss
Write IC File= 0
Write IC File at Fixed DateTime=0
Write IC File at Sim End=0
Echo Input=False
Echo Parameters=False
Echo Output=False
Write Detailed= 0
HDF Write Warmup=0
HDF Write Time Slices=0
HDF Flush=0
HDF Compression= 1
HDF Chunk Size= 1
HDF Spatial Parts= 1
HDF Use Max Rows=0
HDF Fixed Rows= 1
Calibration Method= 0
Calibration Iterations= 20
Calibration Max Change=0.05
Calibration Tolerance=0.2
Calibration Maximum=1.5
Calibration Minimum=0.5
Calibration Optimization Method= 1
WQ AD Non Conservative
WQ ULTIMATE=-1
WQ Max Comp Step=1HOUR
WQ Output Interval=15MIN
WQ Output Selected Increments= 0
WQ Create Restart=0
WQ Fixed Restart=0
WQ System Summary=0
WQ Write To DSS=0
Sorting and Armoring Iterations= 10
XS Update Threshold= 0.02
Bed Roughness Predictor= 0
Processes Affected by Predictor=Sediment Only
Hydraulics Update Threshold= 0.02
Energy Slope Method= 1
Volume Change Method= 1
Sediment Retention Method= 0
Sediment TS Multiplier= 1
Warm Up Method= 0
XS Weighting Method= 0
Number of US Weighted Cross Sections= 1
Number of DS Weighted Cross Sections= 1
Upstream XS Weight=0
Main XS Weight=1
Downstream XS Weight=0
Number of DS XS's Weighted with US Boundary= 1
Upstream Boundary Weight= 1
Weight of XSs Associated with US Boundary= 0
Number of US XS's Weighted with DS Boundary= 1
Downstream Boundary Weight= 0.5
Weight of XSs Associated with DS Boundary= 0.5
Percentile Method= 0
Sediment Output Level= 3
Mass or Volume Output= 0
Output Increment Type= 1
Profile and TS Output Increment= 1
Transport Output Increment 1
XS Output Flag= 0
XS Output Increment= 10
Read HDF5 Sediment Hotstart= 0
Sediment Hotstart Type= 0
Write Gradation File= 0
Read Gradation Hotstart= 0
Write HDF5 File= 1
Write Binary Output= 1
Write DSS Sediment File= 0
DSS Sediment Output Type= 1
SV Curve= 0
Specific Gage Flag= 0
Subcell Erosion Methods= 0
Subcell Deposition Methods= 0
Advection Scheme= 1
Matrix Solver= 0
Implicit Weighting Factor= 1
Maximum Outer Loop Convergence Iterations= 5
Convergence Maximum Absolute= 0.001
Convergence RMSE= 0.0001
Grain Fractions Max Abs Error= 0.001
Max Subgrid Regions= 1
Max Subgrid Length Scale= 3.402823E+38
Initial Layer Thickness= 3
Min Layer Thickness= 0.1
Max Layer Thickness= 6
Number of Layers= 5

--- WillowCreek.p01 (plan) ---

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Plan Title=Existing Condition
Short Identifier=EX
Geom File=g02
Flow File=f01
FOR INFORMATION ONLY:
Flowrates for Willow Creek and Jeffries Creek calculated using USGS Regression Equations published in SIR 2023-5006.  Flowrates for the Great Pee Dee River calculated by performing a Log-Pearson Type III analysis using USGS Streamgage 02131000.  This flow file assumes peak flowrates along each of these reaches occur simultaneously, which is extremely conservative as these reaches vary significantly in drainage area size.  This plan is NOT recommended for use in determining WSE's at the S-57 crossing.

--- WillowCreek.p02 (plan) ---

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Plan Title=Calibration Event
Short Identifier=CALIBRATION
Geom File=g02
Flow File=f03
FOR INFORMATION ONLY:
2018 Hurricane Florence produced a peak discharge of 139,000 at USGS Streamgage 02131010 on 9/21/2018. A USGS Highwater Mark near the confluence of the Great Pee Dee River and Jeffries Creek was recorded (SCFLO27358) by the landowner that came to the site every day by boat.  The HWM also matched lines on the window and building.  The HWM was recorded as 5.25 ft above ground, which corresponds to an elevation of 44.65 ft (NAVD 88) which was determined by taking the ground elevation per LiDAR at the HWM location (39.4 ft).  RS 94930 was used to compare resultant WSE's to the documented elevation of the HWM as this cross-section is closely located to the location of the HWM. The flow file used in this analysis assumes coincidental peaks for all three (3) reaches - Willow Creek, Jeffries Creek, and the Great Pee Dee River.

--- WillowCreek.p04 (plan) ---

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Plan Title=Calibration Event - Offset Peaks
Short Identifier=CALIB_OFFSET
Geom File=g02
Flow File=f02
FOR INFORMATION ONLY:
2018 Hurricane Florence produced a peak discharge of 139,000 at USGS Streamgage 02131010 on 9/21/2018. A USGS Highwater Mark near the confluence of the Great Pee Dee River and Jeffries Creek was recorded (SCFLO27358) by the landowner that came to the site every day by boat.  The HWM also matched lines on the window and building.  The HWM was recorded as 5.25 ft above ground, which corresponds to an elevation of 44.65 ft (NAVD 88) which was determined by taking the ground elevation per LiDAR at the HWM location (39.4 ft).  RS 94930 was used to compare resultant WSE's to the documented elevation of the HWM as this cross-section is closely located to the location of the HWM. See notes in flow file for additional information.

--- WillowCreek.p05 (plan) ---

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Plan Title=Duplicate Effective
Short Identifier=DE
Geom File=g01
Flow File=f04

--- WillowCreek.p12 (plan) ---

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Plan Title=Existing Condition - Great Pee Dee Peak
Short Identifier=EX_PEEDEE_PEAK
Geom File=g02
Flow File=f09
FOR INFORMATION ONLY:
Flowrates for Willow Creek and Jeffries Creek calculated using USGS Regression Equations published in SIR 2023-5006.  Flowrates for the Great Pee Dee River calculated by performing a Log-Pearson Type III analysis using USGS Streamgage 02131000.  The flow file used in this analysis consists of flowrates along Willow Creek and the Jeffries Creek when the Great Pee Dee River peaks, which is approximately 170 hours after initial rainfall

--- WillowCreek.p13 (plan) ---

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Plan Title=Proposed Condition - Willow Peak
Short Identifier=PROP_WILLOW_PEAK
Geom File=g07
Flow File=f08

--- WillowCreek.p15 (plan) ---

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Plan Title=Proposed Condition - Great Pee Dee Peak
Short Identifier=PROP_PEEDEE_PEAK
Geom File=g07
Flow File=f09
FOR INFORMATION ONLY:
Flowrates for Willow Creek and Jeffries Creek calculated using USGS Regression Equations published in SIR 2023-5006.  Flowrates for the Great Pee Dee River calculated by performing a Log-Pearson Type III analysis using USGS Streamgage 02131000.  The flow file used in this analysis consists of flowrates along Willow Creek and the Jeffries Creek when the Great Pee Dee River peaks, which is approximately 170 hours after initial rainfall

--- WillowCreek.p19 (plan) ---

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Plan Title=Natural Condition - Willow Peak
Short Identifier=NAT_WILLOW_PEAK
Geom File=g03
Flow File=f08

--- WillowCreek.p21 (plan) ---

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Plan Title=Natural Condition - Great Pee Dee Peak
Short Identifier=NAT_PEEDEE_PEAK
Geom File=g03
Flow File=f09
FOR INFORMATION ONLY:
Flowrates for Willow Creek and Jeffries Creek calculated using USGS Regression Equations published in SIR 2023-5006.  Flowrates for the Great Pee Dee River calculated by performing a Log-Pearson Type III analysis using USGS Streamgage 02131000.  The flow file used in this analysis consists of flowrates along Willow Creek and the Jeffries Creek when the Great Pee Dee River peaks, which is approximately 170 hours after initial rainfall

--- WillowCreek.f08 (steady flow) ---

Flow Title=USGS Regression Equation - Willow Peak
Program Version=6.60
BEGIN FILE DESCRIPTION:
Flowrates for Willow Creek and Jeffries Creek calculated using USGS Regression Equations published in SIR 2023-5006.  Flowrates for the Great Pee Dee River calculated by performing a Log-Pearson Type III analysis using USGS Streamgage 02131000.  This flow file consists of flowrates along Jeffries Creek and the Great Pee Dee River when Willow Creek peaks, which is approximately 32 hours after initial rainfall
END FILE DESCRIPTION:
Number of Profiles= 3
Profile Names=25yr,100yr,500yr
River Rch & RM=Willow Creek,Reach-1         ,191882
    2960    4520    6480
River Rch & RM=Willow Creek,Reach-1         ,122207
    3848    5759    8206
River Rch & RM=Willow Creek,Reach-1         ,94930
    6819   10179   15439
Boundary for River Rch & Prof#=Willow Creek,Reach-1         , 1
Up Type= 0
Dn Type= 1
Dn Known WS=25
Boundary for River Rch & Prof#=Willow Creek,Reach-1         , 2
Up Type= 0
Dn Type= 1
Dn Known WS=25
Boundary for River Rch & Prof#=Willow Creek,Reach-1         , 3
Up Type= 0
Dn Type= 1
Dn Known WS=25
DSS Import GetInterval= 0
DSS Import GetPeak= 0
DSS Import FillOption= 0

--- WillowCreek.f01 (steady flow) ---

Flow Title=USGS Regression - Coincidental Peaks
Program Version=6.60
BEGIN FILE DESCRIPTION:
Flowrates for Willow Creek and Jeffries Creek calculated using USGS Regression Equations published in SIR 2023-5006.  Flowrates for the Great Pee Dee River calculated by performing a Log-Pearson Type III analysis using USGS Streamgage 02131000.  This flow file assumes peak flowrates along each of these reaches occur simultaneously, which is extremely conservative as these reaches vary significantly in drainage area size
END FILE DESCRIPTION:
Number of Profiles= 6
Profile Names=2yr,10yr,25yr,50yr,100yr,500yr
River Rch & RM=Willow Creek,Reach-1         ,191882
     801    2110    2960    3740    4520    6480
River Rch & RM=Willow Creek,Reach-1         ,122207
    2140    5460    7550    9470   11300   16100
River Rch & RM=Willow Creek,Reach-1         ,94930
   38020   77380  104500  128500  156000  236600
Boundary for River Rch & Prof#=Willow Creek,Reach-1         , 1
Up Type= 0
Dn Type= 3
Dn Slope=0.0004
Boundary for River Rch & Prof#=Willow Creek,Reach-1         , 2
Up Type= 0
Dn Type= 3
Dn Slope=0.0004
Boundary for River Rch & Prof#=Willow Creek,Reach-1         , 3
Up Type= 0
Dn Type= 3
Dn Slope=0.0004
Boundary for River Rch & Prof#=Willow Creek,Reach-1         , 4
Up Type= 0
Dn Type= 3
Dn Slope=0.0004
Boundary for River Rch & Prof#=Willow Creek,Reach-1         , 5
Up Type= 0
Dn Type= 3
Dn Slope=0.0004
Boundary for River Rch & Prof#=Willow Creek,Reach-1         , 6
Up Type= 0
Dn Type= 3
Dn Slope=0.0004
DSS Import GetInterval= 0
DSS Import GetPeak= 0
DSS Import FillOption= 0

--- WillowCreek.f02 (steady flow) ---

Flow Title=Calibration Event - Offset Peaks
Program Version=6.60
BEGIN FILE DESCRIPTION:
Great Pee Dee River flowrate taken from USGS Streamgage 02131010 on 9/21/2018.  2-year flowrates for Jeffries Creek were used, and a flowrate of 200 cfs was utilized for Willow Creek to simulate baseflow as the peak of Willow Creek would occur several days before the peak of the Great Pee Dee River.
END FILE DESCRIPTION:
Number of Profiles= 1
Profile Names=2018 Florence
River Rch & RM=Willow Creek,Reach-1         ,191882
     200
River Rch & RM=Willow Creek,Reach-1         ,122207
    2140
River Rch & RM=Willow Creek,Reach-1         ,94930
  139000
Boundary for River Rch & Prof#=Willow Creek,Reach-1         , 1
Up Type= 0
Dn Type= 1
Dn Known WS=25
DSS Import GetInterval= 0
DSS Import GetPeak= 0
DSS Import FillOption= 0

--- WillowCreek.f03 (steady flow) ---

Flow Title=Calibration Event
Program Version=6.60
BEGIN FILE DESCRIPTION:
Great Pee Dee River flowrate taken from USGS Streamgage 02131010 on 9/21/2018.  100-year flowrates calculated per USGS Regression Equations (SIR 2023-5006) were used for Jeffries Creek and Willow Creek as these flowrates were not critical for the calibration run since the USGS Highwater Mark data was only available for an area adjacent to the Great Pee Dee River.
END FILE DESCRIPTION:
Number of Profiles= 1
Profile Names=2018 Florence
River Rch & RM=Willow Creek,Reach-1         ,191882
    4520
River Rch & RM=Willow Creek,Reach-1         ,122207
   11300
River Rch & RM=Willow Creek,Reach-1         ,94930
  139000
Boundary for River Rch & Prof#=Willow Creek,Reach-1         , 1
Up Type= 0
Dn Type= 3
Dn Slope=0.0004
DSS Import GetInterval= 0
DSS Import GetPeak= 0
DSS Import FillOption= 0

--- WillowCreek.f04 (steady flow) ---

Flow Title=FEMA - 100-year Single
Program Version=6.60
Number of Profiles= 1
Profile Names=100-year
River Rch & RM=Willow Creek,Reach-1         ,69000
    1230
River Rch & RM=Willow Creek,Reach-1         ,62500
    1550
River Rch & RM=Willow Creek,Reach-1         ,58500
    2201
River Rch & RM=Willow Creek,Reach-1         ,45600
    2277
River Rch & RM=Willow Creek,Reach-1         ,39000
    3020
River Rch & RM=Willow Creek,Reach-1         ,26600
    3316
River Rch & RM=Willow Creek,Reach-1         ,16700
    3597
River Rch & RM=Willow Creek,Reach-1         ,11100
    3843
Boundary for River Rch & Prof#=Willow Creek,Reach-1         , 1
Up Type= 0
Dn Type= 3
Dn Slope=0.001
DSS Import GetInterval= 0
DSS Import GetPeak= 0
DSS Import FillOption= 0

--- WillowCreek.f09 (steady flow) ---

Flow Title=USGS Regression Equation - Pee Dee Peak
Program Version=6.60
BEGIN FILE DESCRIPTION:
Flowrates for Willow Creek and Jeffries Creek calculated using USGS Regression Equations published in SIR 2023-5006.  Flowrates for the Great Pee Dee River calculated by performing a Log-Pearson Type III analysis using USGS Streamgage 02131000.  This flow file consists of flowrates along Willow Creek and the Jeffries Creek when the Great Pee Dee River peaks, which is approximately 170 hours after initial rainfall
END FILE DESCRIPTION:
Number of Profiles= 3
Profile Names=25yr,100yr,500yr
River Rch & RM=Willow Creek,Reach-1         ,191882
     200     200     200
River Rch & RM=Willow Creek,Reach-1         ,122207
    3216    4814    6858
River Rch & RM=Willow Creek,Reach-1         ,94930
  104500  156000  236600
Boundary for River Rch & Prof#=Willow Creek,Reach-1         , 1
Up Type= 0
Dn Type= 1
Dn Known WS=25
Boundary for River Rch & Prof#=Willow Creek,Reach-1         , 2
Up Type= 0
Dn Type= 1
Dn Known WS=25
Boundary for River Rch & Prof#=Willow Creek,Reach-1         , 3
Up Type= 0
Dn Type= 1
Dn Known WS=25
DSS Import GetInterval= 0
DSS Import GetPeak= 0
DSS Import FillOption= 0

--- WillowCreek.g02 (geometry) ---

Geom Title=Existing Condition
Program Version=6.60

River Reach=Willow Creek    ,Reach-1
Reach XY= 30
      2389519.64       828073.95      2397216.95       828578.38
        2401912.        823481.4      2410211.93       819081.65
      2414734.94       824370.14       2421834.5       826424.57
      2424011.02       830917.022431178.80114581831791.529071383
2433214.59345319826174.6144375672432136.36536623 825558.48410216
2440506.37427191823584.8828403762440408.61028449821372.534619528
2445768.19101836817227.8945445692445835.75994688814419.370912952
2450466.37673368808367.3306188162450451.72288308796248.596179953
 2451917.1079422793039.4029004952449250.10713461789903.478873994
2454834.75963817781019.8710830392460380.15823263779273.530089203
2457306.06656597772250.7569024322460159.95540063768925.355999434
2462642.20204871768971.9629423692462001.24262385767179.650476568
2463746.07661374765684.0784852372466428.61050295766728.604955373
2467716.07332123762420.4496785522469521.44236791764471.519838091
2469574.85565331760422.7928044182474624.60045385 756628.94786434

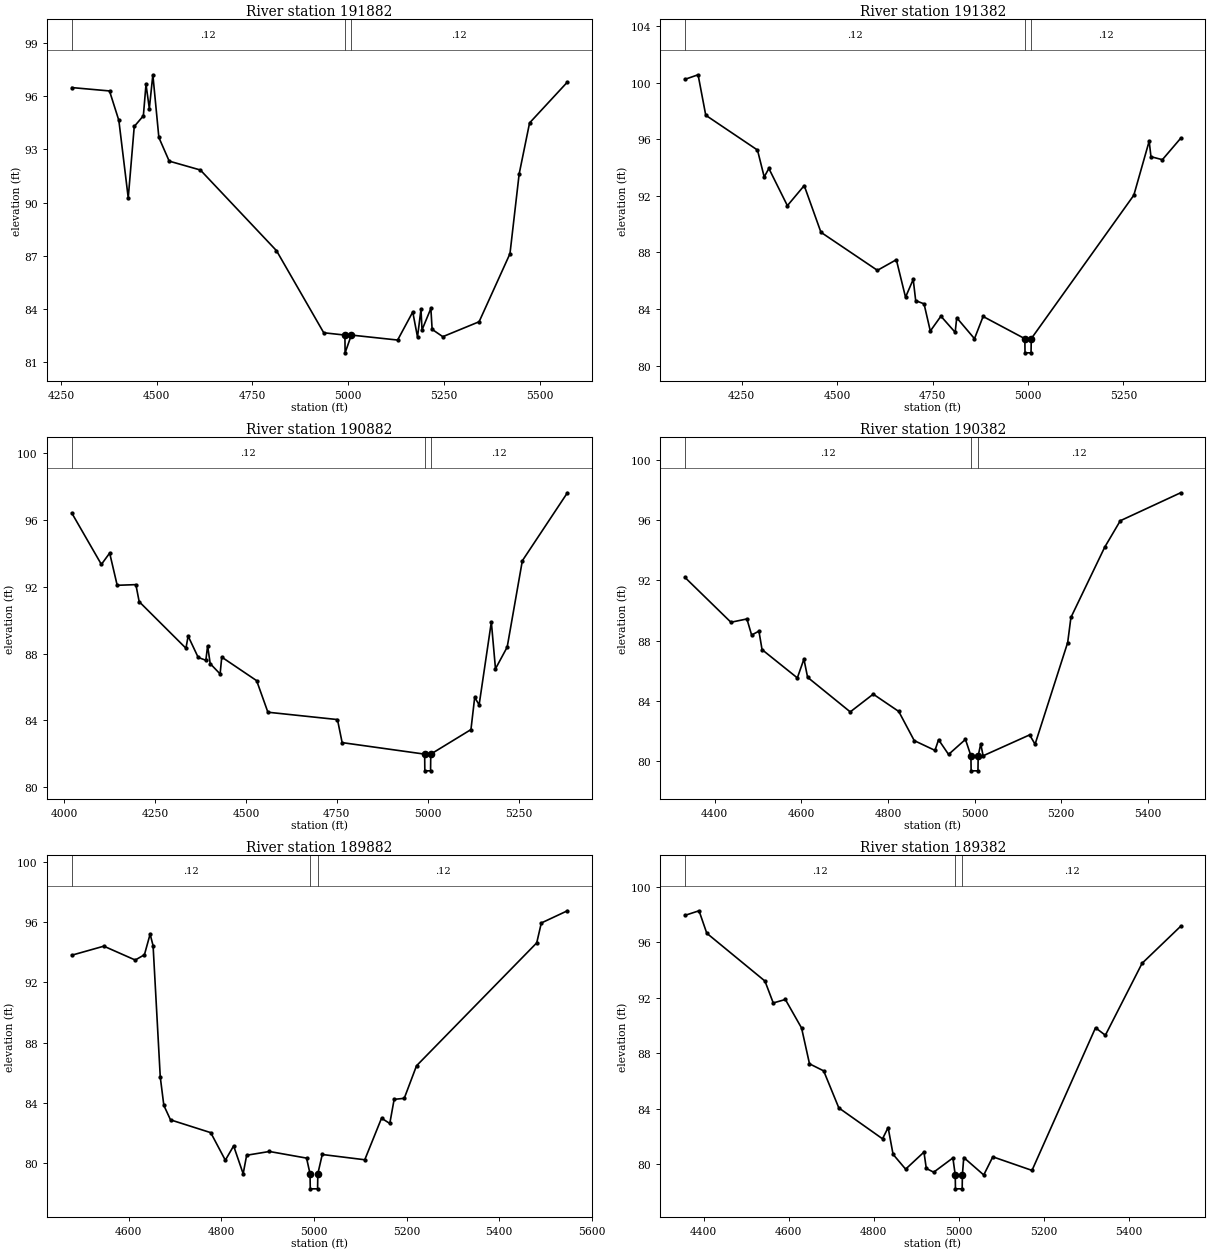
Type RM Length L Ch R = 1 ,191882  ,500,500,500
BEGIN DESCRIPTION:
Willow Creek 131.0
END DESCRIPTION:
XS GIS Cut Line= 3
      2389813.41       828778.87      2389726.32       828062.35
      2389620.07       827499.59
#Sta/Elev= 30
  4278.2   96.47  4376.8   96.28  4401.2   94.62  4425.7   90.26  4441.4   94.28
  4465.2   94.88  4472.1   96.65  4480.8   95.29    4490   97.19  4505.7   93.66
  4532.7   92.33  4614.1   91.83  4812.9   87.29  4936.3   82.67  4991.6   82.54
  4992.1   81.54  5008.4   82.54  5129.3   82.26  5168.8   83.84  5181.2   82.43
  5190.3   83.99    5193   82.83  5216.1   84.04  5219.4   82.86  5247.3   82.45
  5342.1   83.29  5422.7   87.12  5446.7   91.61  5473.9   94.48  5572.7   96.78
#Mann= 3 ,0,0
  4278.2     .12       0  4991.6     .04       0  5008.4     .12       0
Bank Sta=4991.6,5008.4
XS Rating Curve= 0 ,0
Exp/Cntr=0.3,0.1

Type RM Length L Ch R = 1 ,191382  ,500,500,500
BEGIN DESCRIPTION:
Willow Creek 130.0
END DESCRIPTION:
XS GIS Cut Line= 3
      2390329.79       828676.68      2390076.78       827814.43
      2389979.79       827426.68
#Sta/Elev= 30
  4101.4  100.23  4135.7  100.55  4155.8   97.69  4291.3   95.23  4308.9   93.33
  4321.1   93.93  4369.6    91.3  4413.7   92.72  4457.5   89.42  4605.4   86.73
    4655   87.48  4679.1   84.83  4699.2   86.09  4705.7   84.59  4727.6   84.36
    4744   82.44  4771.8   83.49  4809.1   82.35  4813.2   83.38  4859.7    81.9
  4882.3   83.47  4991.6    81.9  4992.1    80.9  5007.9    80.9  5008.4    81.9
  5277.1   92.04  5317.3   95.86    5322   94.76  5351.9   94.55  5399.7   96.06
#Mann= 3 ,0,0
  4101.4     .12       0  4991.6     .04       0  5008.4     .12       0
Bank Sta=4991.6,5008.4
XS Rating Curve= 0 ,0
Exp/Cntr=0.3,0.1

Type RM Length L Ch R = 1 ,190882  ,500,500,500
BEGIN DESCRIPTION:
Willow Creek 129.0
END DESCRIPTION:
XS GIS Cut Line= 3
      2390451.01       828585.52      2390384.74       827608.37
      2390429.79       827226.61
#Sta/Elev= 30
  4020.6   96.42  4102.1   93.34  4124.9   94.02  4145.6   92.09    4197   92.13
  4206.1   91.11  4334.8   88.32  4340.8   89.05  4368.5   87.77  4389.6    87.6
  4394.4   88.47  4401.5    87.4  4428.8   86.78  4433.3   87.79  4529.3   86.38
  4560.3   84.49  4751.7   84.05  4764.6   82.67  4991.6   81.98  4992.1   80.98
  5007.9   80.98  5008.4   81.98    5119   83.45  5129.3   85.38  5141.5   84.93
  5175.1   89.89  5186.5   87.09  5218.7   88.39  5260.4   93.56  5384.4   97.63
#Mann= 3 ,0,0
  4020.6     .12       0  4991.6     .04       0  5008.4     .12       0
Bank Sta=4991.6,5008.4
XS Rating Curve= 0 ,0
Exp/Cntr=0.3,0.1

Type RM Length L Ch R = 1 ,190382  ,500,500,500
BEGIN DESCRIPTION:
Willow Creek 128.0
END DESCRIPTION:
XS GIS Cut Line= 3
      2390656.68       828453.95      2390787.38       827798.04
      2390940.53       827347.35
#Sta/Elev= 30
  4331.2    92.2  4437.3   89.22  4474.2   89.44  4485.1   88.37    4502   88.63
  4509.2    87.4  4590.7   85.52  4605.9   86.77  4614.4   85.56  4712.9   83.26
    4766   84.44  4824.9   83.29  4860.7   81.35  4908.6    80.7  4916.9   81.41
    4940   80.43    4979   81.43  4991.6   80.34  4992.1   79.34  5007.9   79.34
  5008.4   80.34  5014.3   81.13  5019.8   80.34  5127.2   81.73  5139.8   81.11
  5215.1   87.87  5222.6   89.54  5300.6   94.21  5336.6   95.97    5476   97.83
#Mann= 3 ,0,0
  4331.2     .12       0  4991.6     .04       0  5008.4     .12       0
Bank Sta=4991.6,5008.4
XS Rating Curve= 0 ,0
Exp/Cntr=0.3,0.1

Type RM Length L Ch R = 1 ,189882  ,500,500,500
BEGIN DESCRIPTION:
Willow Creek 127.0
END DESCRIPTION:
XS GIS Cut Line= 3
      2391047.47       828490.97      2391176.79       827984.62
      2391379.77       827476.68
#Sta/Elev= 30
  4477.4   93.81  4546.6   94.41  4614.4   93.49  4634.2   93.84  4646.5   95.21
  4652.9   94.44  4668.4   85.72  4676.1   83.84  4690.5   82.88  4777.3   82.03
  4808.8    80.2  4826.7   81.15  4847.3    79.3  4854.8   80.53  4903.9   80.78
  4984.1   80.34  4991.6    79.3  4992.1    78.3  5007.9    78.3  5008.4    79.3
    5018   80.58  5109.7   80.23  5145.9   82.99  5163.7   82.64  5173.1   84.24
  5194.9   84.31  5221.4   86.47  5480.8   94.63  5490.7   95.95    5547   96.76
#Mann= 3 ,0,0
  4477.4     .12       0  4991.6     .04       0  5008.4     .12       0
Bank Sta=4991.6,5008.4
XS Rating Curve= 0 ,0
Exp/Cntr=0.3,0.1

Type RM Length L Ch R = 1 ,189382  ,500,500,500
BEGIN DESCRIPTION:
Willow Creek 126.0
END DESCRIPTION:
XS GIS Cut Line= 3
      2391627.48        828630.8      2391584.45       827988.74
      2391475.27         827479.
#Sta/Elev= 30
  4356.5   97.94  4389.5   98.27  4407.7   96.65  4544.4    93.2  4563.9   91.62
  4592.4   91.87  4630.5   89.81  4649.1   87.23  4682.4   86.72    4718   84.05
  4820.7   81.82  4833.9   82.63  4845.5    80.7    4875   79.63  4918.1   80.86
  4923.6   79.68    4941   79.41  4986.1   80.44  4991.6   79.21  4992.1   78.21
  5007.9   78.21  5008.4   79.21  5011.6   80.47  5058.6   79.21  5079.9   80.52
    5172   79.54  5321.3   89.83  5344.4   89.29  5430.7   94.48  5521.3   97.15
#Mann= 3 ,0,0
  4356.5     .12       0  4991.6     .04       0  5008.4     .12       0
Bank Sta=4991.6,5008.4
XS Rating Curve= 0 ,0
Exp/Cntr=0.3,0.1

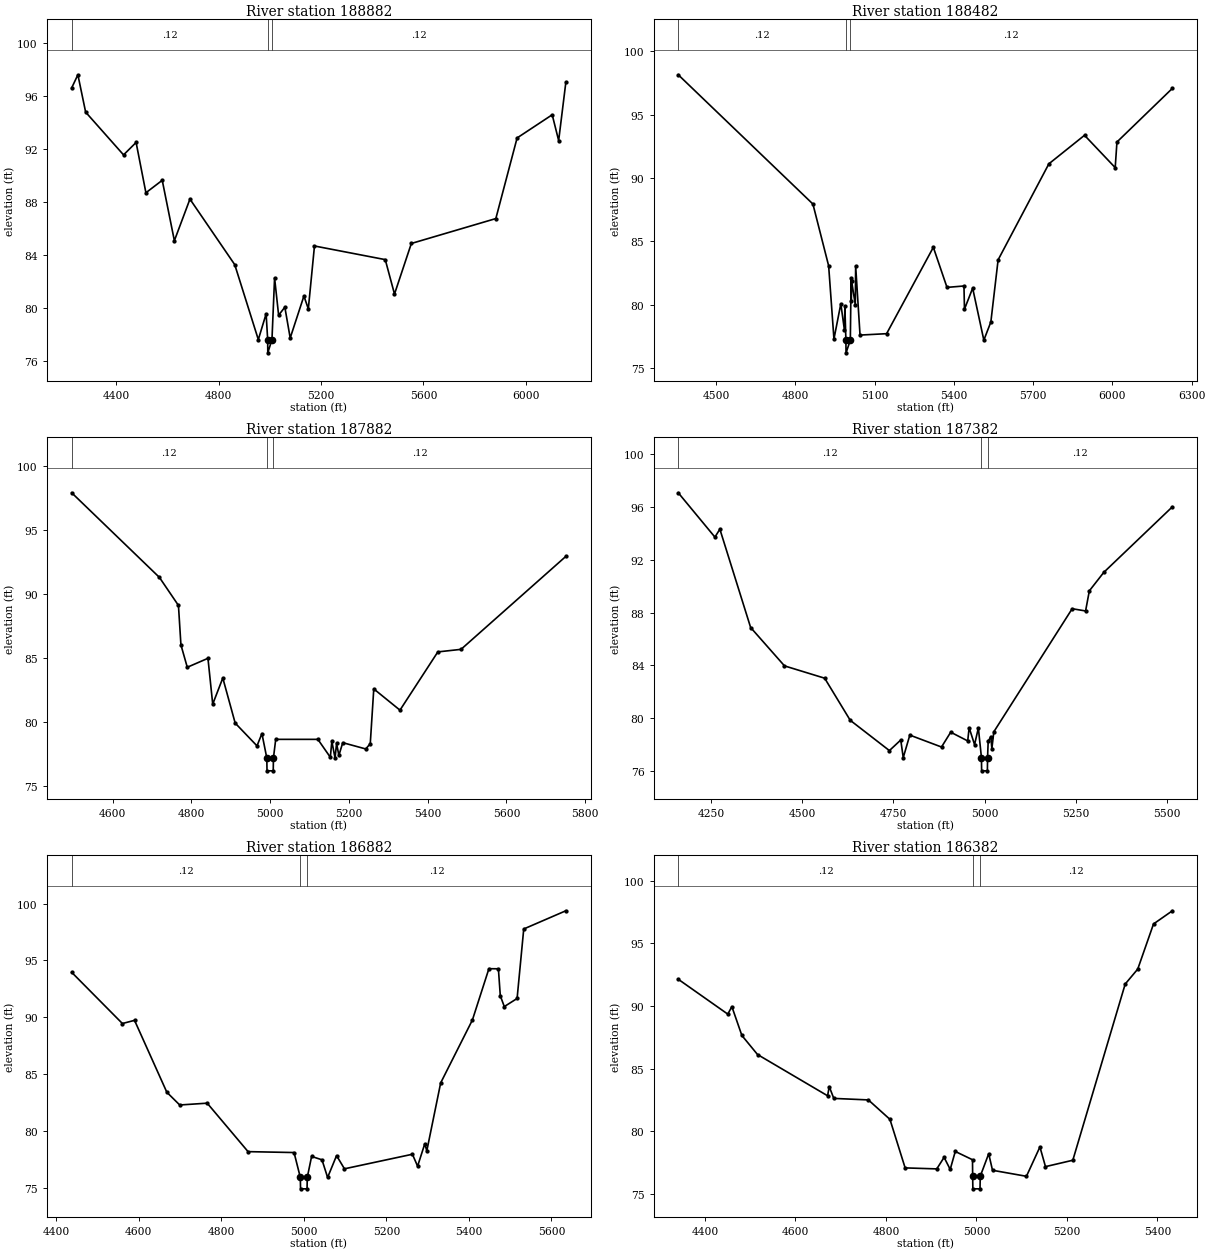
Type RM Length L Ch R = 1 ,188882  ,400,400,400
BEGIN DESCRIPTION:
Willow Creek 125.0
END DESCRIPTION:
XS GIS Cut Line= 3
      2391853.72       828750.13      2392067.92       828006.46
      2392232.17       826861.99
#Sta/Elev= 30
  4226.1   96.59  4250.3   97.58  4280.6   94.76  4428.7   91.53  4477.7   92.47
    4516   88.67  4579.8   89.61  4627.2   85.05    4688   88.19    4863   83.24
  4955.1   77.58  4985.6   79.53  4991.6   77.58  4992.1   76.58  5008.4   77.58
  5018.6   82.24  5034.4   79.42  5058.7   80.03  5079.6    77.7  5133.2   80.87
  5150.4    79.9  5174.4   84.65  5450.9   83.62    5487   81.02  5552.8   84.84
  5882.8   86.72  5965.9   92.81    6103   94.56  6128.2   92.61  6156.2      97
#Mann= 3 ,0,0
  4226.1     .12       0  4991.6     .04       0  5008.4     .12       0
Bank Sta=4991.6,5008.4
XS Rating Curve= 0 ,0
Exp/Cntr=0.3,0.1

Type RM Length L Ch R = 1 ,188482  ,600,600,600
BEGIN DESCRIPTION:
Willow Creek 124.0
END DESCRIPTION:
XS GIS Cut Line= 3
       2392316.5        828791.2      2392406.83       828154.78
      2392859.48       827014.21
#Sta/Elev= 30
  4357.2   98.14  4866.8   87.95  4926.3   83.08  4946.4   77.31  4972.4   80.09
  4986.1   78.01  4987.7   79.89  4991.6   77.22  4992.1   76.22  5008.4   77.22
  5011.3   82.13  5011.9   80.29  5013.2   81.89  5027.2      80  5028.5   83.08
  5045.1   77.62  5145.6   77.73  5322.5   84.54  5374.2   81.38  5438.4   81.49
  5440.3   79.66  5471.3   81.32  5513.6   77.22  5540.1   78.65  5567.6   83.55
  5759.7   91.12  5894.6   93.37  6010.7   90.82  6017.3   92.84  6227.1   97.07
#Mann= 3 ,0,0
  4357.2     .12       0  4991.6     .04       0  5008.4     .12       0
Bank Sta=4991.6,5008.4
XS Rating Curve= 0 ,0
Exp/Cntr=0.3,0.1

Type RM Length L Ch R = 1 ,187882  ,500,500,500
BEGIN DESCRIPTION:
Willow Creek 123.0
END DESCRIPTION:
XS GIS Cut Line= 3
      2392479.76       828647.33      2392730.85       828210.67
      2392884.07       827475.88
#Sta/Elev= 30
  4496.3   97.89    4719   91.28  4767.3   89.09  4773.6   86.01  4789.7   84.26
  4842.2   84.96  4854.3   81.38  4879.9   83.42  4911.3    79.9  4966.7   78.12
  4979.2   79.08  4991.6   77.17  4992.1   76.17  5007.9   76.17  5008.4   77.17
  5014.2   78.63  5121.2   78.63  5152.8   77.23  5156.7   78.47  5164.8   77.17
  5168.7   78.31  5174.5   77.38  5184.4   78.37  5242.7   77.88  5254.2   78.29
  5263.1   82.57  5329.6   80.91  5425.7   85.46  5484.6   85.66  5750.6   92.92
#Mann= 3 ,0,0
  4496.3     .12       0  4991.6     .04       0  5008.4     .12       0
Bank Sta=4991.6,5008.4
XS Rating Curve= 0 ,0
Exp/Cntr=0.3,0.1

Type RM Length L Ch R = 1 ,187382  ,500,500,500
BEGIN DESCRIPTION:
Willow Creek 122.0
END DESCRIPTION:
XS GIS Cut Line= 3
      2392793.66        828894.1      2393126.67       828121.73
      2393394.27       827680.54
#Sta/Elev= 30
  4158.9   97.05  4259.6    93.7  4273.2    94.3  4357.7   86.87  4450.7   83.97
    4561   83.04  4631.2   79.86  4738.8   77.57    4770   78.37  4776.8   77.04
  4794.9   78.74  4881.9   77.84  4907.2   78.96  4953.9    78.3  4957.8    79.3
  4972.7   78.02  4983.1   79.28  4991.6   77.04  4992.1   76.04  5007.9   76.04
  5008.4   77.04  5010.1   78.27  5017.4   78.63  5020.2   77.71  5025.6   78.99
  5240.8   88.29  5277.6   88.12  5287.9   89.64  5327.7   91.04    5516   95.99
#Mann= 3 ,0,0
  4158.9     .12       0  4991.6     .04       0  5008.4     .12       0
Bank Sta=4991.6,5008.4
XS Rating Curve= 0 ,0
Exp/Cntr=0.3,0.1

Type RM Length L Ch R = 1 ,186882  ,500,500,500
BEGIN DESCRIPTION:
Willow Creek 121.0
END DESCRIPTION:
XS GIS Cut Line= 3
      2393179.77        828926.7      2393394.17       828406.66
      2393745.96       827878.02
#Sta/Elev= 30
  4437.5   93.96  4560.4   89.46  4589.8   89.74  4668.1   83.42  4699.3    82.3
  4765.9   82.46  4864.9    78.2  4976.4   78.12  4991.6   75.93  4992.1   74.93
  5007.9   74.93  5008.4   75.93  5018.9   77.78  5044.1   77.48  5057.7   75.93
  5079.4   77.85  5098.5   76.69  5263.2   77.97  5275.8   76.92  5293.2   78.89
  5298.1   78.27  5331.7   84.24  5408.6   89.77  5448.6   94.28  5471.6   94.27
  5476.2    91.9  5485.9   90.95  5516.9   91.66    5533   97.77    5635   99.37
#Mann= 3 ,0,0
  4437.5     .12       0  4991.6     .04       0  5008.4     .12       0
Bank Sta=4991.6,5008.4
XS Rating Curve= 0 ,0
Exp/Cntr=0.3,0.1

Type RM Length L Ch R = 1 ,186382  ,500,500,500
BEGIN DESCRIPTION:
Willow Creek 120.0
END DESCRIPTION:
XS GIS Cut Line= 3
      2393542.33       829103.88      2393829.77       828510.76
       2394029.8       828126.63
#Sta/Elev= 30
  4340.9   92.13  4450.4   89.35  4459.4   89.95  4481.5   87.65  4516.1   86.13
    4671   82.84  4674.6   83.57  4684.7   82.63  4761.1   82.51  4808.8   80.96
  4842.4   77.09  4912.3   77.01  4928.5   77.93    4942   76.97  4953.2    78.4
  4991.3   77.74  4991.6   76.42  4992.1   75.42  5007.9   75.42  5008.4   76.42
  5027.1   78.22  5035.5    76.9  5110.5   76.42  5140.3   78.76  5152.6   77.19
    5213    77.7  5328.8   91.75  5356.5   92.94  5391.4   96.54  5433.1   97.59
#Mann= 3 ,0,0
  4340.9     .12       0  4991.6     .04       0  5008.4     .12       0
Bank Sta=4991.6,5008.4
XS Rating Curve= 0 ,0
Exp/Cntr=0.3,0.1

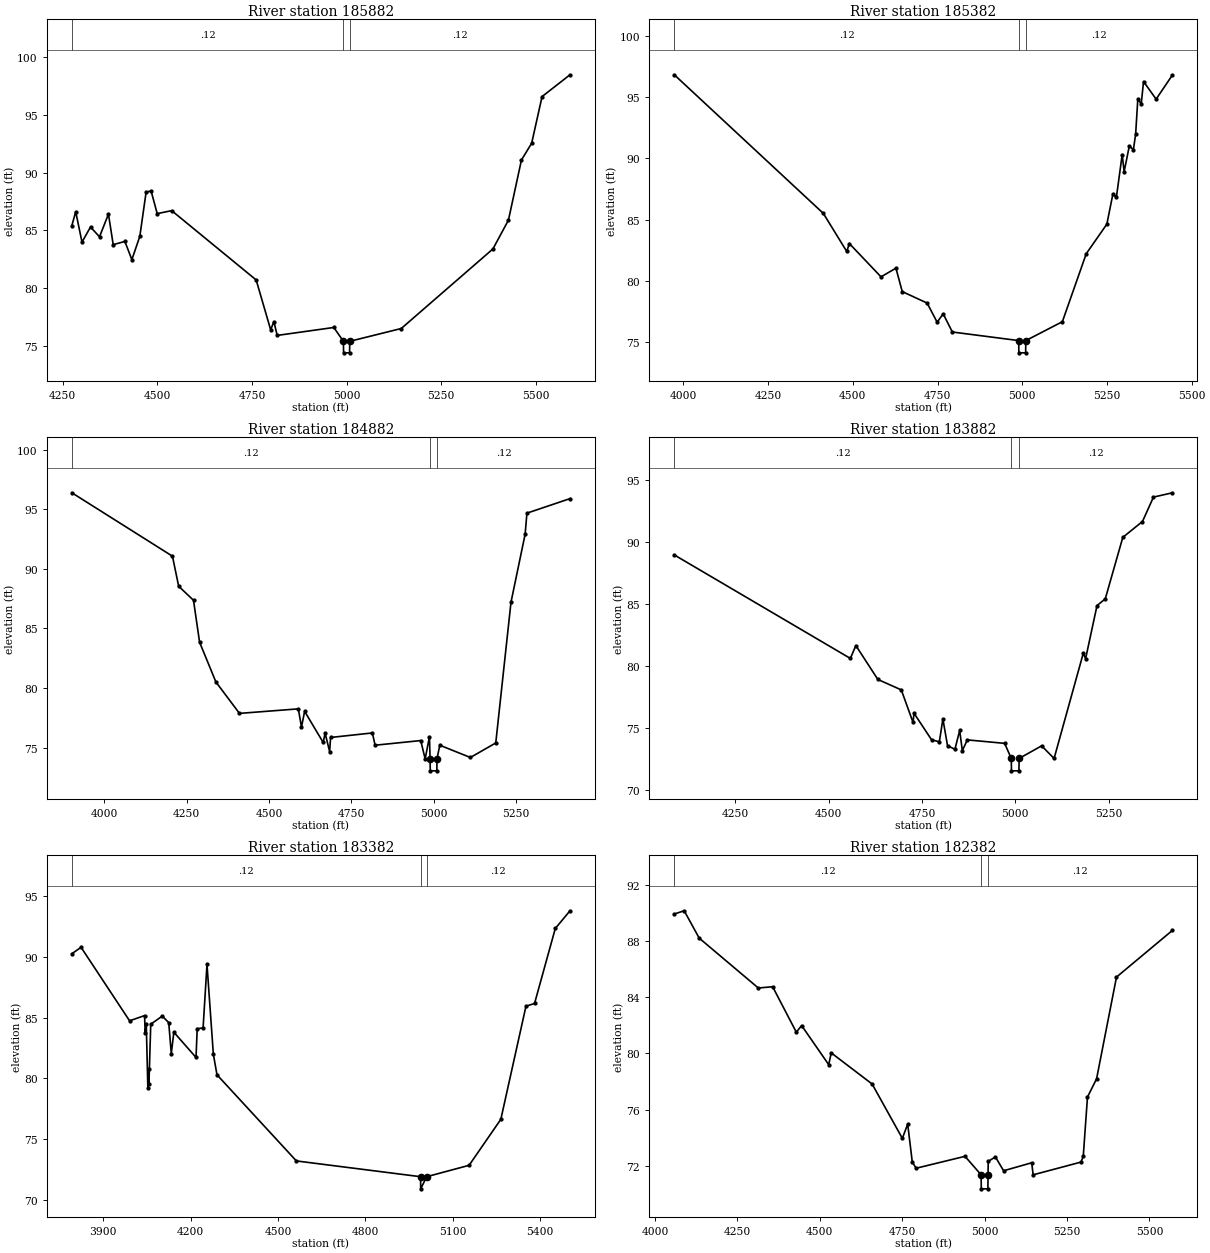
Type RM Length L Ch R = 1 ,185882  ,500,500,500
BEGIN DESCRIPTION:
Willow Creek 119.0
END DESCRIPTION:
XS GIS Cut Line= 3
      2393766.53       829247.83      2394275.64       828730.53
      2394479.79       828176.66
#Sta/Elev= 30
  4274.2   85.43  4284.3   86.63  4300.9   83.99  4323.4    85.3  4347.2   84.45
  4370.8   86.42  4383.4   83.77  4414.2   84.05  4432.7   82.47  4453.7   84.49
  4470.3   88.32  4483.5   88.43  4499.6   86.46  4537.9   86.72  4761.1   80.71
  4799.4   76.39    4808    77.1  4816.6    75.9  4966.3   76.59  4991.6   75.39
  4992.1   74.39  5007.9   74.39  5008.4   75.39  5144.5    76.5  5386.7    83.4
  5427.7    85.9    5462   91.11    5489   92.56  5516.5   96.61  5590.3    98.5
#Mann= 3 ,0,0
  4274.2     .12       0  4991.6     .04       0  5008.4     .12       0
Bank Sta=4991.6,5008.4
XS Rating Curve= 0 ,0
Exp/Cntr=0.3,0.1

Type RM Length L Ch R = 1 ,185382  ,500,500,500
BEGIN DESCRIPTION:
Willow Creek 118.0
END DESCRIPTION:
XS GIS Cut Line= 3
      2394650.93       829746.44      2394738.27       828723.26
      2394811.36       828286.13
#Sta/Elev= 30
  3973.1   96.81  4412.9    85.5  4482.1   82.39  4489.7   83.04  4583.2   80.32
  4627.2   81.03  4645.8   79.12  4719.3   78.18  4748.8   76.62  4766.7    77.3
  4793.7   75.82  4989.5   75.12    4990   74.12    5010   74.12  5010.5   75.12
  5118.4   76.66  5188.9   82.21  5249.7   84.62  5267.5   87.08  5277.9   86.82
    5295    90.3  5300.7    88.9    5316      91  5328.1    90.7  5334.7   91.98
  5341.1   94.83  5351.2   94.44    5358   96.26  5395.1   94.82  5443.2   96.79
#Mann= 3 ,0,0
  3973.1     .12       0  4989.5     .04       0  5010.5     .12       0
Bank Sta=4989.5,5010.5
XS Rating Curve= 0 ,0
Exp/Cntr=0.3,0.1

Type RM Length L Ch R = 1 ,184882  ,1000,1000,1000
BEGIN DESCRIPTION:
Willow Creek 117.0
END DESCRIPTION:
XS GIS Cut Line= 3
      2394951.21       829775.24      2395234.14       828713.18
      2395374.92       828323.11
#Sta/Elev= 30
  3900.9   96.38  4206.5   91.06  4225.4   88.54  4270.5   87.36    4289   83.84
  4338.5   80.51  4410.2   77.87    4589   78.25  4598.7   76.73  4608.3   78.04
  4664.6   75.43  4670.5   76.21  4684.2   74.67  4687.1   75.85  4814.1   76.23
  4822.4    75.2  4961.1   75.59  4974.5   74.05  4987.6   75.92  4989.5   74.05
    4990   73.05    5010   73.05  5010.5   74.05  5018.9    75.2    5112   74.17
  5189.1   75.39  5235.4    87.2  5278.4   92.91  5283.8   94.67  5414.7   95.89
#Mann= 3 ,0,0
  3900.9     .12       0  4989.5     .04       0  5010.5     .12       0
Bank Sta=4989.5,5010.5
XS Rating Curve= 0 ,0
Exp/Cntr=0.3,0.1

Type RM Length L Ch R = 1 ,183882  ,500,500,500
BEGIN DESCRIPTION:
Willow Creek 115.0
END DESCRIPTION:
XS GIS Cut Line= 3
      2396376.58        829762.9      2396103.54       828891.36
      2396029.79       828476.67
#Sta/Elev= 30
  4086.7   88.96  4558.4    80.6  4573.1   81.64  4632.1    78.9  4694.8   78.06
  4726.2   75.44    4729   76.17  4776.1   74.02  4796.8   73.87  4806.3   75.71
  4818.7   73.55  4838.5   73.26  4851.2   74.78  4858.4   73.15  4871.7   74.02
  4971.7   73.74  4989.5   72.52    4990   71.52    5010   71.52  5010.5   72.52
  5070.8   73.54  5104.2   72.52  5182.4   81.02  5188.6   80.58  5219.2   84.87
  5241.3   85.41  5288.3   90.38    5341   91.66  5370.4   93.63  5421.2   93.98
#Mann= 3 ,0,0
  4086.7     .12       0  4989.5     .04       0  5010.5     .12       0
Bank Sta=4989.5,5010.5
XS Rating Curve= 0 ,0
Exp/Cntr=0.3,0.1

Type RM Length L Ch R = 1 ,183382  ,1000,1000,1000
BEGIN DESCRIPTION:
Willow Creek 114.0
END DESCRIPTION:
XS GIS Cut Line= 3
      2397022.38       829729.94      2396439.73       828672.08
      2396257.25       828203.78
#Sta/Elev= 30
  3792.3   90.27  3823.8    90.8  3990.4   84.74  4041.8   85.17  4044.1   83.74
  4047.7   84.48  4053.1   79.23    4056   80.76  4056.8   79.51  4063.1   84.46
  4102.7   85.13  4124.8   84.59  4133.6   82.04  4142.4    83.8  4218.5   81.72
  4222.6   84.09  4242.8   84.15  4256.2   89.39    4278   81.99  4290.5   80.29
  4563.1   73.19  4989.5   71.89    4990   70.89  5010.5   71.89  5156.2   72.83
  5265.1   76.62  5351.4   85.94  5380.9   86.17  5452.1   92.35  5502.6   93.81
#Mann= 3 ,0,0
  3792.3     .12       0  4989.5     .04       0  5010.5     .12       0
Bank Sta=4989.5,5010.5
XS Rating Curve= 0 ,0
Exp/Cntr=0.3,0.1

Type RM Length L Ch R = 1 ,182382  ,500,500,500
BEGIN DESCRIPTION:
Willow Creek 112.0
END DESCRIPTION:
XS GIS Cut Line= 3
       2397888.3       829277.47      2397317.59       828529.16
      2397082.02       828010.45
#Sta/Elev= 30
  4058.9   89.95  4088.9   90.18  4134.4   88.23  4313.7   84.67  4357.2   84.76
  4428.9   81.52  4445.1   81.99  4527.2    79.2  4534.9   80.04  4658.9   77.82
  4750.6   73.94  4766.8   74.96  4780.7   72.25  4792.4   71.81  4940.6   72.66
  4989.5   71.34    4990   70.34    5010   70.34  5010.5   71.34  5011.1    72.3
  5032.8   72.62  5057.7   71.63  5142.9    72.2  5147.3   71.34  5292.6   72.25
  5299.3   72.67  5312.1   76.89  5339.7   78.19  5400.1   85.45  5569.7   88.78
#Mann= 3 ,0,0
  4058.9     .12       0  4989.5     .04       0  5010.5     .12       0
Bank Sta=4989.5,5010.5
XS Rating Curve= 0 ,0
Exp/Cntr=0.3,0.1