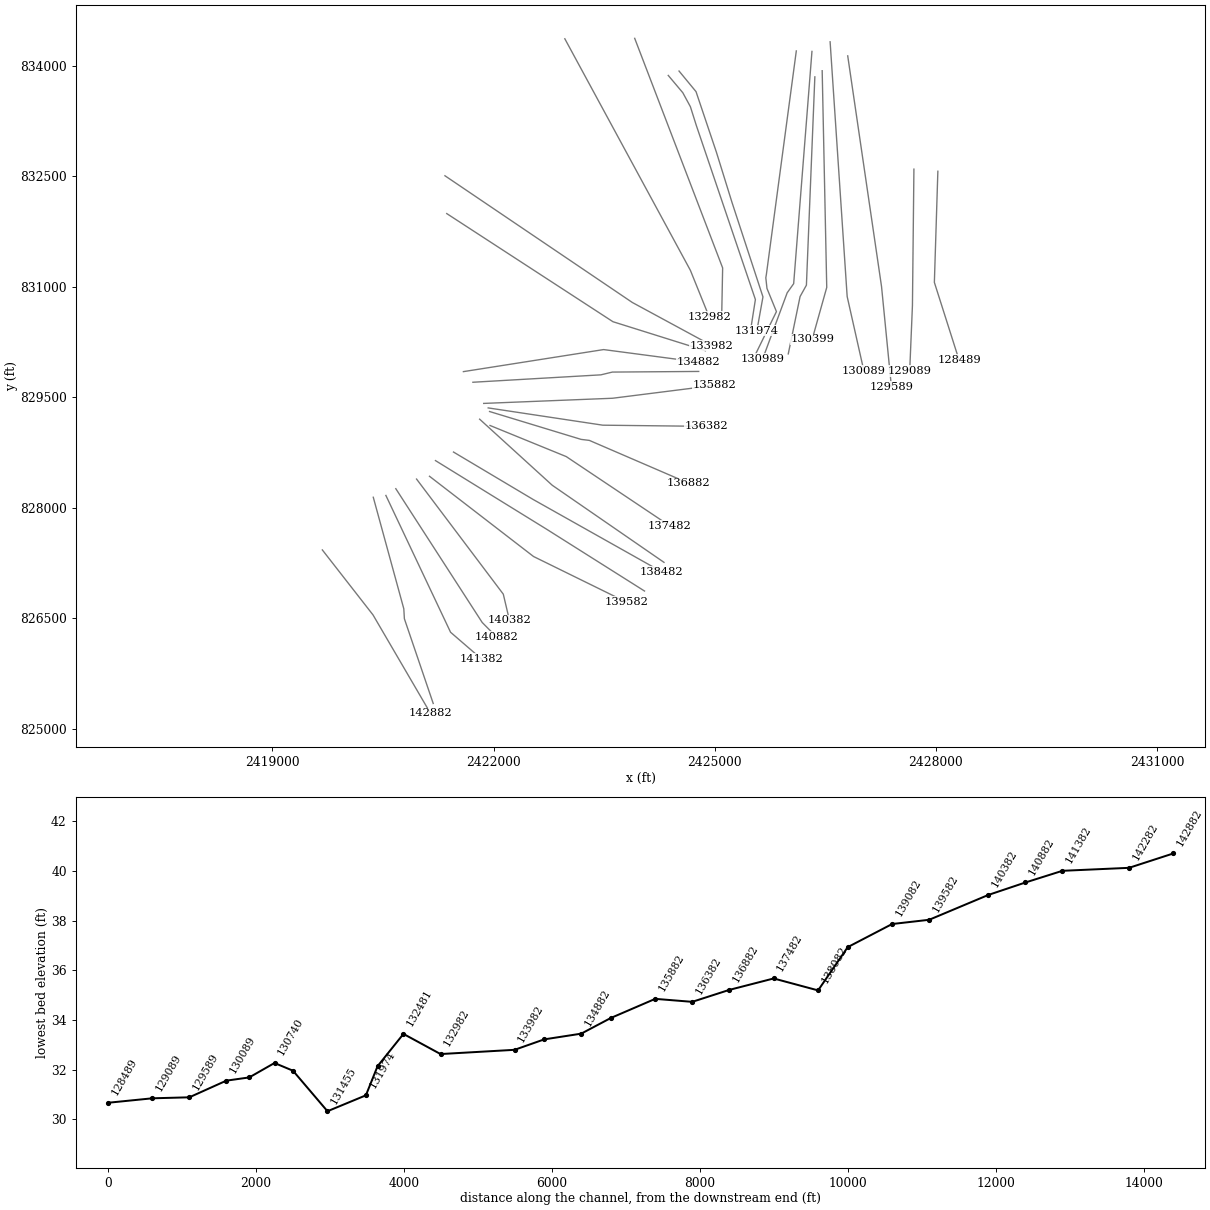
HEC-RAS study WillowCreek.prj: S-21-57 over Willow Creek

--- WillowCreek.g02 (geometry) --- (continued)

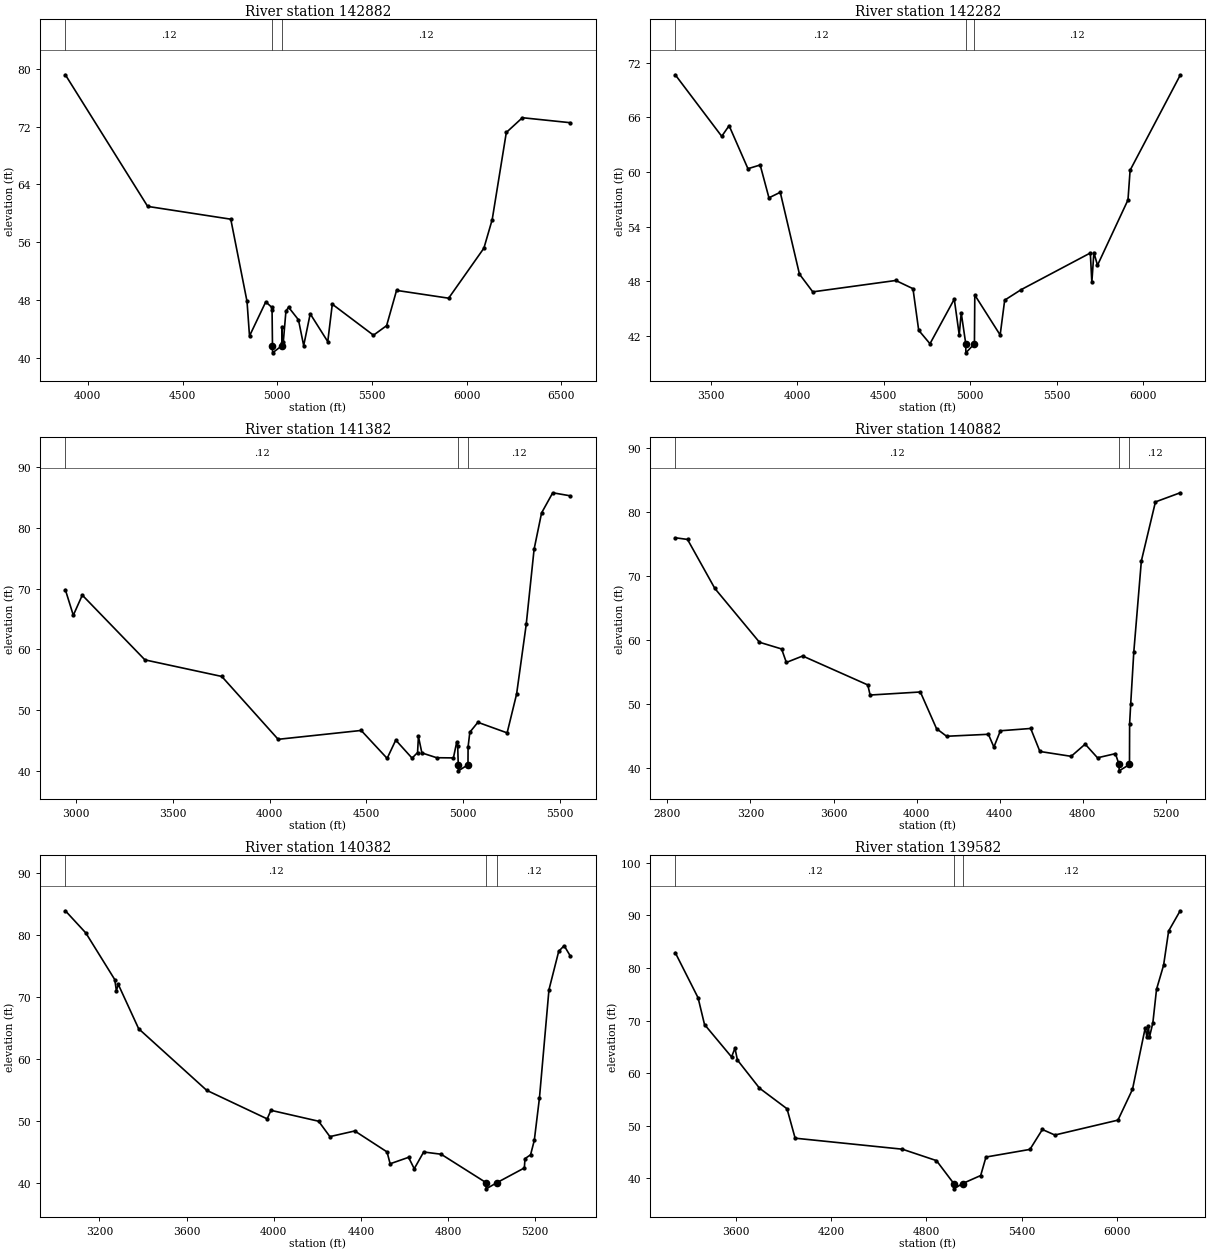
Type RM Length L Ch R = 1 ,142882  ,600,600,600
BEGIN DESCRIPTION:
Willow Creek 35.0
END DESCRIPTION:
XS GIS Cut Line= 3
      2419676.32       827426.47      2420363.93       826543.79
      2421143.68        825207.1
#Sta/Elev= 30
  3881.1   79.17  4315.8   60.96  4754.7   59.19  4840.5   47.81  4853.6   43.03
  4939.4   47.75  4971.1      47  4972.7   46.64  4974.9    41.7  4975.4    40.7
  5025.1    41.7  5025.3   44.33    5026   42.06  5032.2   42.24    5046   46.48
    5060   47.01  5112.1   45.27  5139.7    41.7  5174.2    46.1  5266.9   42.25
  5290.8   47.43  5508.3   43.14  5577.6   44.46  5630.2   49.34  5905.2   48.26
  6091.4   55.18  6135.3   59.14  6209.8   71.19  6294.7   73.23  6547.5   72.54
#Mann= 3 ,0,0
  3881.1     .12       0  4974.9     .04       0  5025.1     .12       0
Bank Sta=4974.9,5025.1
XS Rating Curve= 0 ,0
Exp/Cntr=0.3,0.1

Type RM Length L Ch R = 1 ,142282  ,900,900,900
BEGIN DESCRIPTION:
Willow Creek 34.0
END DESCRIPTION:
XS GIS Cut Line= 4
      2420367.23       828141.77      2420781.44       826626.71
      2420789.18       826492.09      2421180.38       825341.58
#Sta/Elev= 30
  3294.5   70.67  3563.3   63.91    3606   65.08    3715   60.35  3785.7   60.76
  3836.5   57.15  3901.9   57.76  4012.9   48.77    4090   46.82    4570   48.07
  4669.6   47.17  4702.7    42.6    4768   41.12  4908.5   46.02  4937.2   42.09
  4948.7   44.51  4974.9   41.12  4975.4   40.12  5025.1   41.12  5027.2   46.47
  5173.9   42.08  5200.1   45.91  5296.1   47.07  5695.5   51.09  5704.3   47.87
  5716.1   51.14  5736.9   49.74  5913.3   56.92  5925.6   60.18  6215.2   70.62
#Mann= 3 ,0,0
  3294.5     .12       0  4974.9     .04       0  5025.1     .12       0
Bank Sta=4974.9,5025.1
XS Rating Curve= 0 ,0
Exp/Cntr=0.3,0.1

Type RM Length L Ch R = 1 ,141382  ,500,500,500
BEGIN DESCRIPTION:
Willow Creek 32.0
END DESCRIPTION:
XS GIS Cut Line= 3
      2420538.39        828166.3      2421415.78       826308.57
       2421834.6       825946.85
#Sta/Elev= 30
  2945.5   69.82  2986.6   65.61    3033   68.93  3356.5   58.27  3753.5   55.54
  4044.6   45.19  4473.5   46.65  4607.5   42.05  4652.1   45.06  4736.3   42.09
  4764.7   43.01  4769.1   45.66    4787   42.95  4863.5   42.16  4949.9   42.13
  4966.6   44.69    4972   44.09  4974.9      41  4975.4      40  5025.1      41
  5025.6   43.93  5034.7   46.36  5076.2   47.99  5227.3   46.25  5276.2   52.64
  5325.9    64.1  5366.6   76.49  5405.3   82.47  5462.9   85.78  5553.4   85.28
#Mann= 3 ,0,0
  2945.5     .12       0  4974.9     .04       0  5025.1     .12       0
Bank Sta=4974.9,5025.1
XS Rating Curve= 0 ,0
Exp/Cntr=0.3,0.1

Type RM Length L Ch R = 1 ,140882  ,500,500,500
BEGIN DESCRIPTION:
Willow Creek 31.0
END DESCRIPTION:
XS GIS Cut Line= 3
      2420672.91       828257.98      2421844.89       826441.31
      2422034.15       826250.01
#Sta/Elev= 30
  2838.1      76  2897.1   75.74  3028.7   68.07  3243.6   59.65  3350.2    58.6
    3373   56.49  3451.6    57.5  3765.2   52.97  3776.2   51.39  4018.2   51.87
  4096.1   46.13  4144.6   44.94  4345.8   45.25  4372.2   43.25  4403.6    45.8
  4549.4   46.16  4593.8   42.56  4744.3    41.8  4811.7   43.71  4871.1   41.57
  4957.2   42.22  4974.9   40.53  4975.4   39.53  5025.1   40.53  5025.7    46.9
  5030.9   49.98  5045.8   58.11  5082.2   72.37    5150   81.61  5269.1   83.04
#Mann= 3 ,0,0
  2838.1     .12       0  4974.9     .04       0  5025.1     .12       0
Bank Sta=4974.9,5025.1
XS Rating Curve= 0 ,0
Exp/Cntr=0.3,0.1

Type RM Length L Ch R = 1 ,140382  ,800,800,800
BEGIN DESCRIPTION:
Willow Creek 30.0
END DESCRIPTION:
XS GIS Cut Line= 3
      2420954.17       828388.81      2422130.99        826825.8
      2422213.82       826473.92
#Sta/Elev= 30
  3043.5   83.86  3137.6   80.28  3270.4   72.76  3277.7   70.98  3286.6   71.98
  3380.1   64.84  3692.1   54.92    3970   50.31  3987.4   51.69  4206.2   49.93
    4258   47.45  4372.1   48.36  4520.4   44.98  4534.5   43.07  4619.2   44.11
  4645.2   42.27  4688.5   44.97  4768.7   44.61  4974.9   40.03  4975.4   39.03
  5025.1   40.03  5150.8    42.4  5153.6    43.9  5179.3   44.52  5196.4   46.85
    5220   53.67  5263.7   71.13  5308.5   77.33  5333.5   78.23  5361.5   76.58
#Mann= 3 ,0,0
  3043.5     .12       0  4974.9     .04       0  5025.1     .12       0
Bank Sta=4974.9,5025.1
XS Rating Curve= 0 ,0
Exp/Cntr=0.3,0.1

Type RM Length L Ch R = 1 ,139582  ,500,500,500
BEGIN DESCRIPTION:
Willow Creek 29.0
END DESCRIPTION:
XS GIS Cut Line= 3
      2421129.85       828426.65      2422541.39         827337.
      2423797.17       826719.69
#Sta/Elev= 30
  3216.8   82.89  3360.7   74.31  3401.2   69.24  3571.6   63.08  3593.1   64.73
  3608.7   62.49  3747.8   57.15  3921.2   53.24  3972.4   47.65    4648   45.56
  4863.2   43.39  4972.5   39.03    4973   38.03  5027.5   39.03  5141.9   40.56
  5175.3   44.07  5452.4   45.52  5530.7    49.3  5609.5   48.25  6007.2   51.08
  6098.8   56.93  6179.4   68.66  6190.1    66.8  6198.8   68.92  6205.6   66.82
  6227.2   69.57  6250.3   75.93  6294.8    80.5  6326.6      87  6399.3   90.84
#Mann= 3 ,0,0
  3216.8     .12       0  4972.5     .04       0  5027.5     .12       0
Bank Sta=4972.5,5027.5
XS Rating Curve= 0 ,0
Exp/Cntr=0.3,0.1

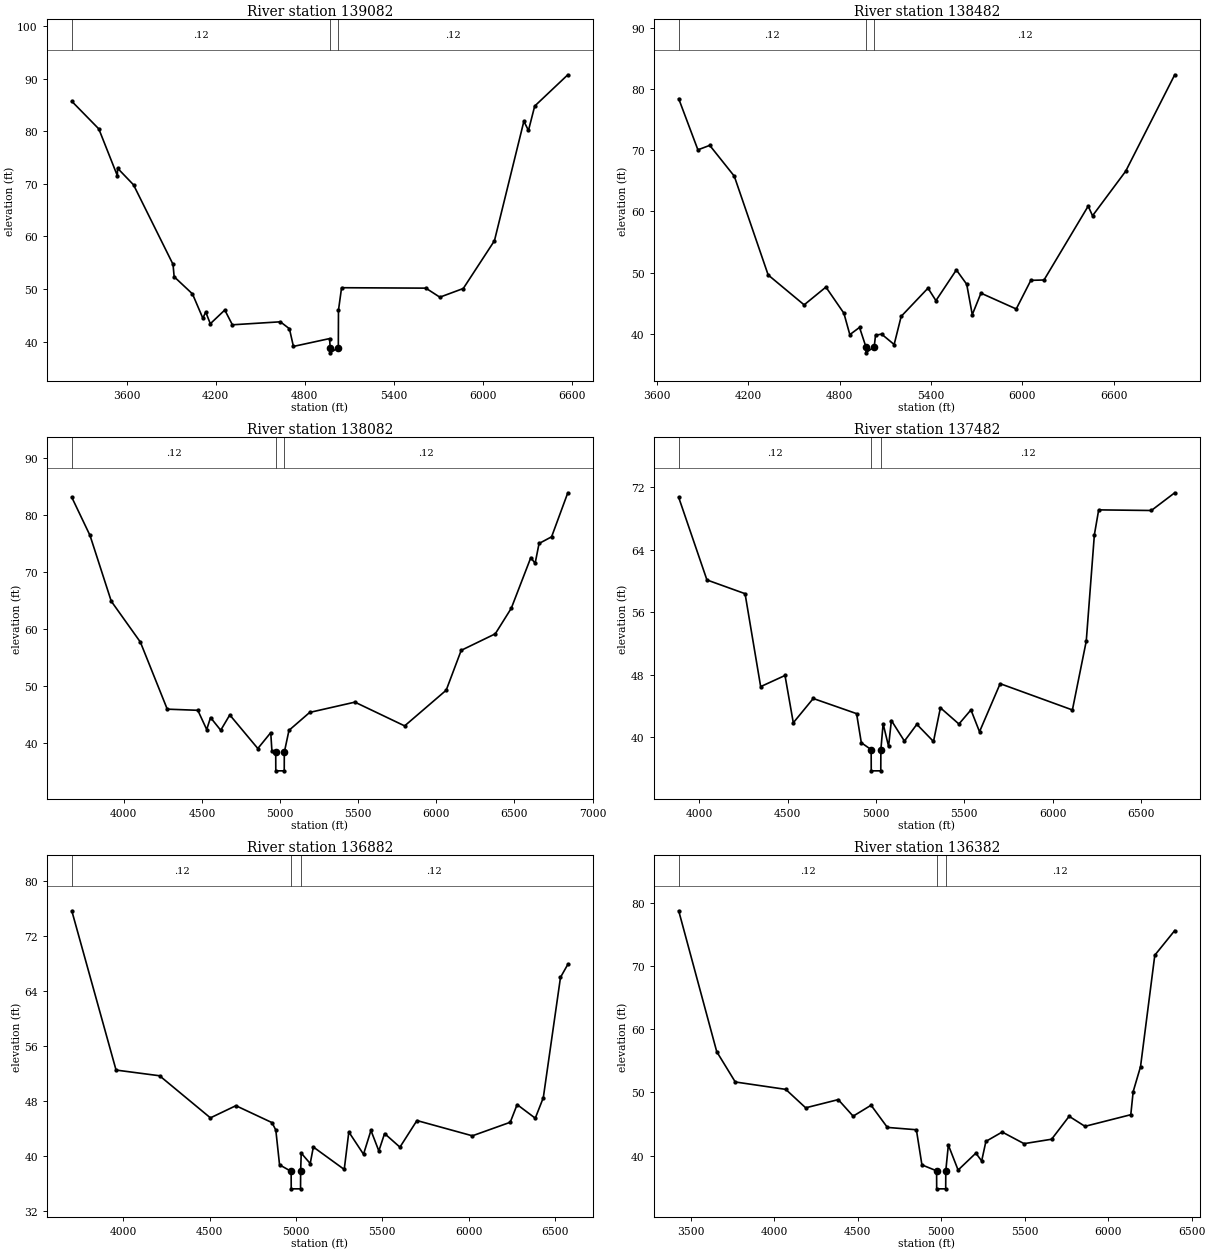
Type RM Length L Ch R = 1 ,139082  ,600,600,600
BEGIN DESCRIPTION:
Willow Creek 28.0
END DESCRIPTION:
XS GIS Cut Line= 3
      2421210.98       828639.47      2422715.75       827709.41
      2424046.46       826868.39
#Sta/Elev= 30
    3231   85.68  3413.2   80.43  3538.4   71.51  3539.5   72.96  3647.1    69.8
  3913.4   54.68  3920.9   52.33  4044.5   49.06  4114.4   44.44  4133.7   45.62
  4164.7   43.39  4262.3      46  4313.4   43.19  4636.6   43.76  4697.9   42.44
  4724.8   39.08  4968.6   40.57  4972.5   38.86    4973   37.86  5027.5   38.86
  5028.5   45.96  5049.4   50.24  5617.3   50.16  5711.7   48.44  5869.6   50.09
  6079.7   59.17    6278   81.88    6309   80.13    6351   84.77  6574.2   90.72
#Mann= 3 ,0,0
    3231     .12       0  4972.5     .04       0  5027.5     .12       0
Bank Sta=4972.5,5027.5
XS Rating Curve= 0 ,0
Exp/Cntr=0.3,0.1

Type RM Length L Ch R = 1 ,138482  ,400,400,400
BEGIN DESCRIPTION:
Willow Creek 27.0
END DESCRIPTION:
XS GIS Cut Line= 3
      2421455.49       828755.67      2422535.62       828111.75
      2424280.21       827129.31
#Sta/Elev= 30
  3742.5   78.41  3868.8   70.06  3946.5   70.79  4107.7   65.77  4330.5   49.64
  4566.9   44.76    4710   47.66  4828.1    43.4  4867.1    39.9  4930.9   41.08
  4972.5   37.93    4973   36.93  5027.5   37.93    5036    39.8  5075.8   39.99
  5158.4   38.29  5204.6   42.88  5380.9   47.49  5432.9   45.45  5567.3   50.46
  5635.3   48.12  5671.8   43.16  5728.9   46.67  5960.7   44.09  6056.6   48.76
  6143.3   48.82  6433.6   60.88  6462.1    59.3  6679.9   66.57  7002.2   82.31
#Mann= 3 ,0,0
  3742.5     .12       0  4972.5     .04       0  5027.5     .12       0
Bank Sta=4972.5,5027.5
XS Rating Curve= 0 ,0
Exp/Cntr=0.3,0.1

Type RM Length L Ch R = 1 ,138082  ,600,600,600
BEGIN DESCRIPTION:
Willow Creek 26.0
END DESCRIPTION:
XS GIS Cut Line= 3
      2421810.12       829201.99      2422795.24       828304.43
      2424310.81       827257.69
#Sta/Elev= 30
  3667.3   83.09  3783.9   76.41    3920   64.89  4106.2   57.74  4278.3   45.99
    4474   45.79  4530.8   42.42  4555.3   44.52  4620.5    42.3  4678.5   44.98
    4858    39.1  4940.7   41.88  4948.2   38.64  4972.5   38.44    4973   35.19
    5027   35.19  5027.5   38.44  5057.3   42.28    5190   45.42  5479.2   47.22
  5797.7   43.06  6063.6   49.31  6159.6   56.29  6377.6   59.18  6480.1   63.66
  6605.1   72.53  6632.6   71.52  6657.9      75  6738.1   76.17  6841.9   83.88
#Mann= 3 ,0,0
  3667.3     .12       0  4972.5     .04       0  5027.5     .12       0
Bank Sta=4972.5,5027.5
XS Rating Curve= 0 ,0
Exp/Cntr=0.3,0.1

Type RM Length L Ch R = 1 ,137482  ,600,600,600
BEGIN DESCRIPTION:
Willow Creek 25.0
END DESCRIPTION:
XS GIS Cut Line= 3
      2421950.79       829116.37      2422985.01       828693.84
      2424390.29       827752.93
#Sta/Elev= 30
  3882.8   70.71  4042.7   60.13  4258.6   58.37  4346.9   46.46  4484.7   47.89
  4531.7   41.83  4644.6   44.94    4890      43  4916.8   39.27  4972.5   38.39
    4973   35.67    5027   35.67  5027.5   38.39  5040.2    41.7  5071.1   38.81
    5087   42.12  5160.8   39.48  5231.2   41.63  5325.4   39.43  5364.6   43.75
  5469.4   41.67  5537.5   43.48    5586   40.68  5702.8   46.84  6111.9   43.47
  6190.3   52.29  6236.3   65.92  6260.7   69.11  6558.9   69.03  6691.2    71.3
#Mann= 3 ,0,0
  3882.8     .12       0  4972.5     .04       0  5027.5     .12       0
Bank Sta=4972.5,5027.5
XS Rating Curve= 0 ,0
Exp/Cntr=0.3,0.1

Type RM Length L Ch R = 1 ,136882  ,500,500,500
BEGIN DESCRIPTION:
Willow Creek 24.0
END DESCRIPTION:
XS GIS Cut Line= 4
      2421944.66       829305.91      2423186.48       828927.49
      2423297.84       828913.94      2424640.92       828333.79
#Sta/Elev= 30
  3701.8   75.64  3958.3   52.48  4210.5   51.65  4504.9   45.53  4652.5    47.3
  4861.5   44.84  4883.7   43.76  4905.4    38.7  4972.5   37.75    4973   35.21
    5027   35.21  5027.5   37.75  5030.9   40.41    5083   38.89  5101.1   41.29
  5280.1   38.03  5306.6   43.48  5391.7   40.24  5434.8    43.7  5480.5   40.72
  5513.8   43.25  5602.7   41.27  5701.2   45.14  6022.3   42.92  6241.7   44.89
  6281.6   47.46  6386.7   45.48  6433.2   48.46  6532.8   65.96  6575.2   67.84
#Mann= 3 ,0,0
  3701.8     .12       0  4972.5     .04       0  5027.5     .12       0
Bank Sta=4972.5,5027.5
XS Rating Curve= 0 ,0
Exp/Cntr=0.3,0.1

Type RM Length L Ch R = 1 ,136382  ,500,500,500
BEGIN DESCRIPTION:
Willow Creek 23.0
END DESCRIPTION:
XS GIS Cut Line= 3
      2421926.31       829354.83      2423480.83       829120.35
      2424879.34       829104.15
#Sta/Elev= 30
  3427.9   78.73  3655.8   56.43  3766.7   51.64  4069.1   50.47  4188.5   47.55
  4383.5   48.85  4472.7   46.23  4580.1   47.96  4677.7   44.45  4851.4   44.08
  4884.6   38.52  4972.5   37.58    4973   34.73    5027   34.73  5027.5   37.58
  5042.9   41.66  5101.3    37.7  5207.7   40.38  5242.4   39.14  5267.8   42.24
  5365.3   43.72  5496.3   41.88  5661.3   42.58  5766.3   46.21  5861.1   44.62
  6135.5   46.46  6149.7   50.11  6193.8   54.06  6279.3    71.7  6398.6    75.6
#Mann= 3 ,0,0
  3427.9     .12       0  4972.5     .04       0  5027.5     .12       0
Bank Sta=4972.5,5027.5
XS Rating Curve= 0 ,0
Exp/Cntr=0.3,0.1

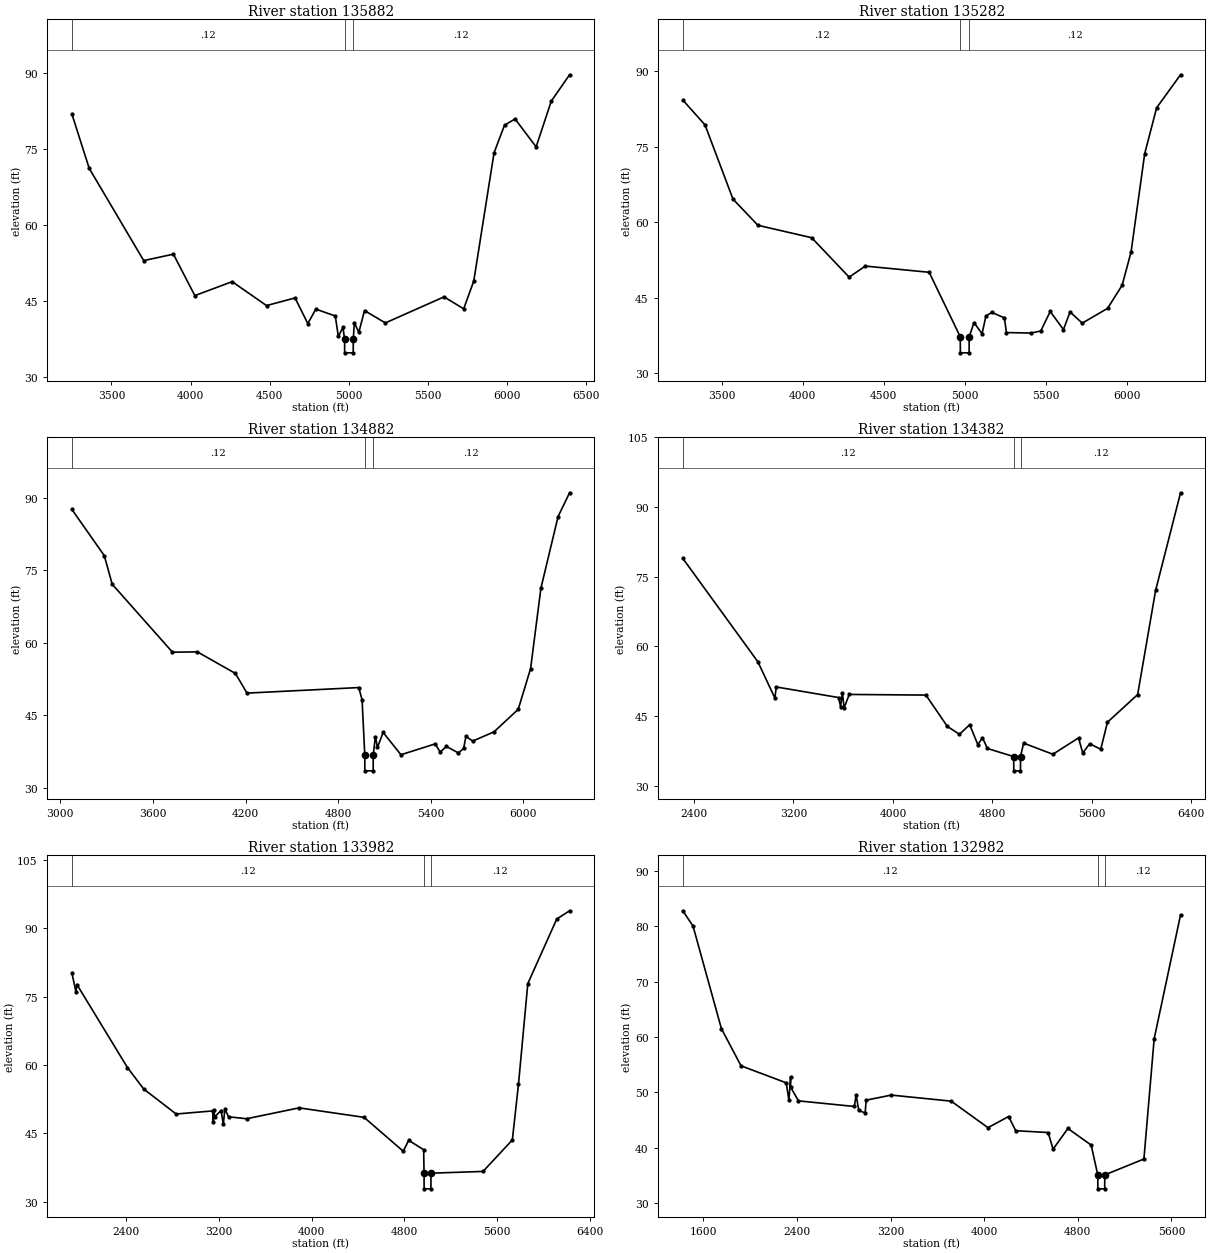
Type RM Length L Ch R = 1 ,135882  ,600,600,600
BEGIN DESCRIPTION:
Willow Creek 22.0
END DESCRIPTION:
XS GIS Cut Line= 3
      2421865.19       829415.97      2423613.29       829486.06
      2424995.52       829660.53
#Sta/Elev= 30
  3250.5   81.97  3359.9   71.24  3704.2   53.04  3891.6   54.31  4026.9   46.14
  4262.7   48.89  4479.6   44.17  4659.8   45.68  4740.4   40.62  4790.9   43.47
  4913.8   42.12  4933.1   38.08  4962.4   39.88  4972.5    37.5    4973   34.85
    5027   34.85  5027.5    37.5    5034    40.8  5062.5   38.89  5098.3   43.19
    5230   40.75  5600.6   45.89  5724.5   43.53  5788.2   49.01  5916.3    74.3
  5982.4   79.75  6048.9   80.98    6182   75.47  6277.5   84.49  6393.2   89.69
#Mann= 3 ,0,0
  3250.5     .12       0  4972.5     .04       0  5027.5     .12       0
Bank Sta=4972.5,5027.5
XS Rating Curve= 0 ,0
Exp/Cntr=0.3,0.1

Type RM Length L Ch R = 1 ,135282  ,400,400,400
BEGIN DESCRIPTION:
Willow Creek 21.0
END DESCRIPTION:
XS GIS Cut Line= 4
      2421718.46       829703.33      2423454.75       829803.89
      2423610.47       829841.47      2424781.55       829850.06
#Sta/Elev= 30
  3260.8   84.23  3397.9   79.29  3570.2   64.58  3724.1   59.38  4055.7   56.92
  4286.8    49.1  4386.8   51.29  4780.5   50.06  4972.5   37.26    4973   34.08
    5027   34.08  5027.5   37.26  5057.3   40.08  5106.8   37.86  5130.9   41.41
    5167   42.09  5244.7   41.02  5257.2    38.1  5410.7   38.01  5469.2   38.42
  5527.5   42.29    5609   38.69  5649.7   42.19  5725.1   39.97  5881.1    42.9
  5971.1   47.49  6026.1   54.07  6110.2   73.58  6183.8   82.69  6331.3   89.24
#Mann= 3 ,0,0
  3260.8     .12       0  4972.5     .04       0  5027.5     .12       0
Bank Sta=4972.5,5027.5
XS Rating Curve= 0 ,0
Exp/Cntr=0.3,0.1

Type RM Length L Ch R = 1 ,134882  ,500,500,500
BEGIN DESCRIPTION:
Willow Creek 20.0
END DESCRIPTION:
XS GIS Cut Line= 3
      2421589.99       829847.61      2423491.67         830147.
      2424779.86       829976.66
#Sta/Elev= 30
  3074.9   87.54  3285.1   77.97  3336.2   72.06  3726.7      58  3888.3   58.06
  4134.1   53.61  4209.6   49.53  4933.6   50.68  4955.1   48.15  4972.5   36.78
    4973   33.45    5027   33.45  5027.5   36.78  5041.3   40.54  5054.8    38.3
  5091.4    41.4  5206.9   36.78  5429.1   39.03    5461   37.33  5501.4   38.49
  5578.8   37.16  5612.7   38.08  5628.2   40.57    5672   39.61  5809.4   41.51
  5966.8   46.18  6046.9   54.62  6113.6   71.23  6224.9   86.06  6299.4   90.98
#Mann= 3 ,0,0
  3074.9     .12       0  4972.5     .04       0  5027.5     .12       0
Bank Sta=4972.5,5027.5
XS Rating Curve= 0 ,0
Exp/Cntr=0.3,0.1

Type RM Length L Ch R = 1 ,134382  ,400,400,400
BEGIN DESCRIPTION:
Willow Creek 19.0
END DESCRIPTION:
XS GIS Cut Line= 3
       2421363.8       831993.65       2423618.5       830525.26
      2424873.31        830131.3
#Sta/Elev= 30
  2309.3   78.96    2914   56.68  3050.4   48.89  3061.4   51.28  3563.2      49
    3579   47.03  3593.8   50.02  3607.5   46.77    3649   49.67  4265.9   49.53
  4438.5   42.78  4535.7   41.09  4618.4   43.15  4683.7   38.86  4721.2   40.35
    4761   38.03  4972.5   36.29    4973   33.22    5027   33.22  5027.5   36.29
    5052   39.19  5287.6   36.79  5494.4   40.31  5528.2   37.06    5584   39.05
    5673   37.87  5727.1   43.69  5970.1   49.64  6114.6   72.06  6315.2   93.09
#Mann= 3 ,0,0
  2309.3     .12       0  4972.5     .04       0  5027.5     .12       0
Bank Sta=4972.5,5027.5
XS Rating Curve= 0 ,0
Exp/Cntr=0.3,0.1

Type RM Length L Ch R = 1 ,133982  ,1000,1000,1000
BEGIN DESCRIPTION:
Willow Creek 18.0
END DESCRIPTION:
XS GIS Cut Line= 3
      2421339.33       832507.24      2423881.01       830786.63
      2424958.87       830202.23
#Sta/Elev= 30
  1930.7   80.26  1965.9   76.04  1974.3   77.66  2410.5   59.43  2550.8   54.72
  2830.6   49.23  3145.3   49.91  3151.7   47.58  3153.4   50.15  3163.6   48.66
    3219      50  3237.6   46.94  3251.4   50.29  3283.5   48.62  3438.4   48.19
  3891.5   50.58  4452.5    48.5  4790.4   41.06  4837.8   43.45  4966.6   41.39
  4970.2   36.24  4970.7    32.8  5029.3    32.8  5029.8   36.24  5479.1   36.62
  5732.2   43.53    5785   55.74  5865.6   77.87  6115.3   92.04  6226.1   93.86
#Mann= 3 ,0,0
  1930.7     .12       0  4970.2     .04       0  5029.8     .12       0
Bank Sta=4970.2,5029.8
XS Rating Curve= 0 ,0
Exp/Cntr=0.3,0.1

Type RM Length L Ch R = 1 ,132982  ,500.9,500.9,500.9
BEGIN DESCRIPTION:
Willow Creek 16.0
END DESCRIPTION:
XS GIS Cut Line= 3
      2422965.66       834367.16      2424668.89       831222.94
      2424922.17       830594.78
#Sta/Elev= 30
  1424.1   82.76  1511.4      80    1754    61.5  1921.6   54.81  2307.9   51.74
  2330.9   48.57  2345.4   52.83  2345.9   50.95  2412.3   48.49  2889.8   47.48
  2905.2   49.54  2927.7   46.76  2982.2   46.31  2990.8   48.62  3205.3   49.53
  3717.4   48.44  4031.8   43.66  4208.1   45.67  4269.2   43.11    4546   42.78
  4588.1   39.78    4715   43.51  4913.6   40.52  4970.2   35.14  4970.7   32.63
  5029.3   32.63  5029.8   35.14  5364.4   38.01    5452   59.68  5677.3   82.01
#Mann= 3 ,0,0
  1424.1     .12       0  4970.2     .04       0  5029.8     .12       0
Bank Sta=4970.2,5029.8
XS Rating Curve= 0 ,0
Exp/Cntr=0.3,0.1

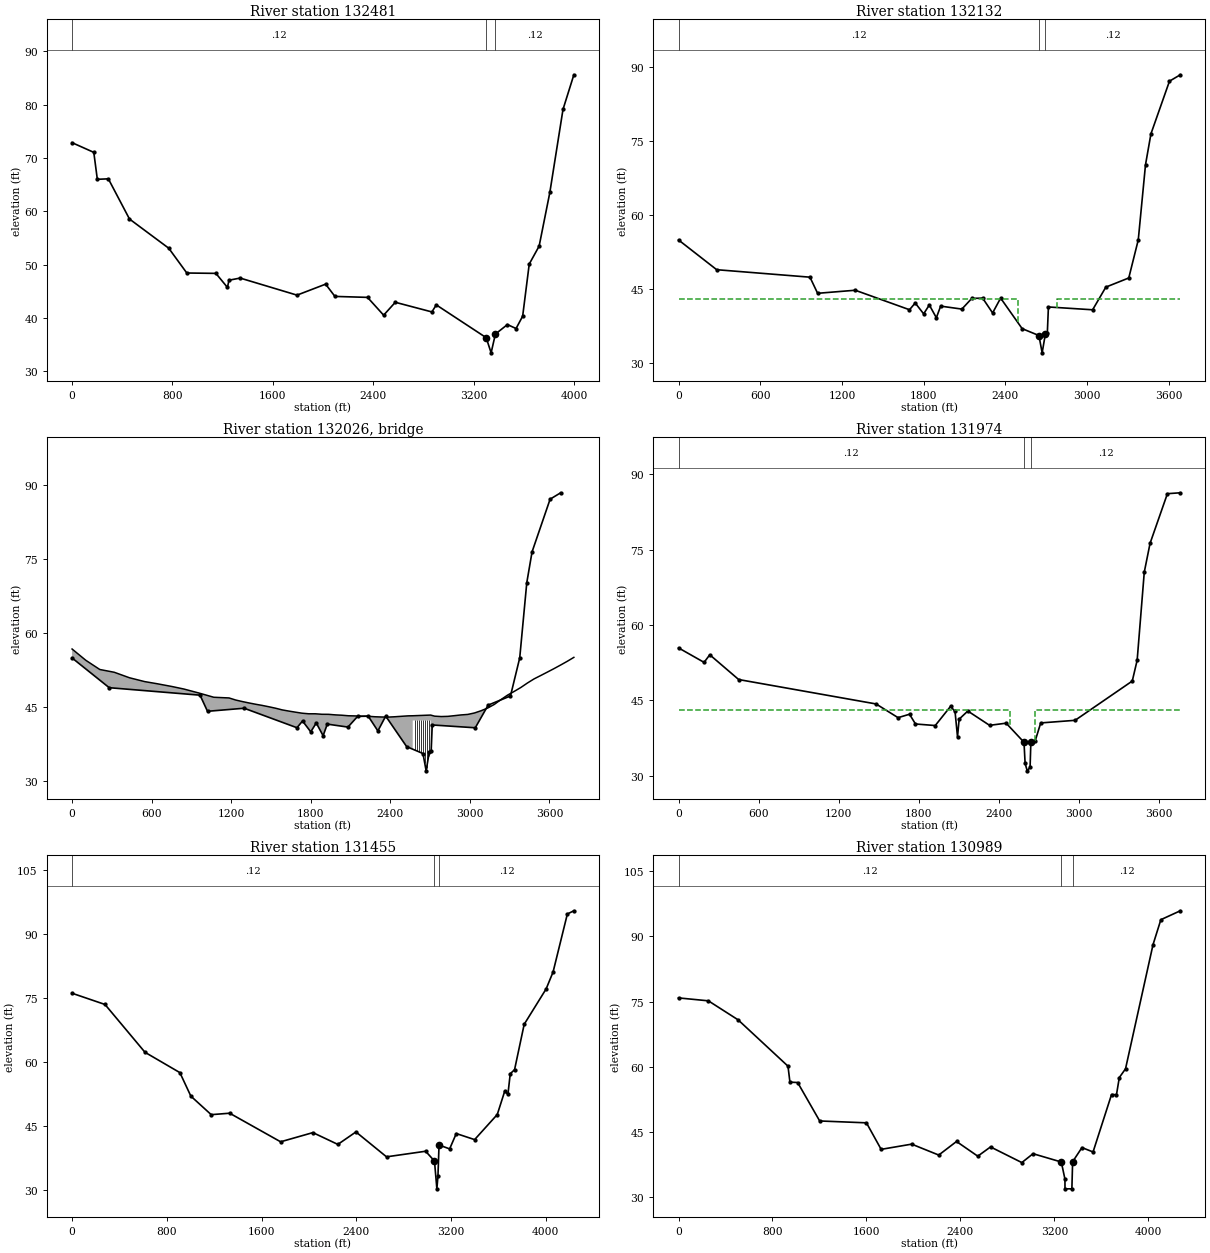
Type RM Length L Ch R = 1 ,132481  ,349.9,349.9,349.9
BEGIN DESCRIPTION:
Willow Creek 15.0
END DESCRIPTION:
XS GIS Cut Line= 3
      2423913.37       834373.21      2425106.34       831255.78
      2425093.37       830594.71
#Sta/Elev= 30
2.31E-11   72.85   173.2   71.03   201.3   65.98   289.1   66.07   457.7   58.53
   770.4   53.06   914.4   48.41  1146.3   48.34  1238.1   45.71  1250.8   47.06
  1339.5   47.46  1792.6   44.26  2020.7   46.32  2094.8   44.02  2354.7   43.84
  2483.1    40.5    2576   42.92  2867.6   41.11  2902.7   42.43  3300.3  36.285
  3339.7   33.44  3373.736.95745  3469.6   38.74  3538.5      38    3591   40.31
  3643.5   50.09  3722.3   53.45  3807.6   63.51  3912.6   79.09  3999.1   85.58
#Mann= 3 ,0,0
2.31E-11     .12       0  3300.3     .04       0  3373.7     .12       0
Bank Sta=3300.3,3373.7
XS Rating Curve= 0 ,0
Exp/Cntr=0.5,0.3

Type RM Length L Ch R = 1 ,132132  ,157.4,157.4,157.4
XS GIS Cut Line= 6
2424368.72477113 833869.458369092424565.91144344833634.789289292
 2424668.7174029 833445.409890292424749.88000247833188.394991645
2425550.68431825830826.5633440922425488.85582631830432.388653409
#Sta/Elev= 30
       0   54.95  280.12   48.94   964.9   47.43 1021.25   44.17 1297.47   44.79
 1695.86   40.85 1737.88   42.21 1799.79   40.02 1841.36   41.81 1893.11   39.23
 1924.51   41.58  2080.4   40.98 2153.15   43.14 2232.83    43.2 2306.06    40.2
 2364.96    43.2 2522.98   37.03 2646.15   35.64 2669.87   32.14 2692.96   35.86
 2708.05   36.23 2715.84   41.41 3040.46   40.84 3137.52   45.42 3305.88   47.27
 3375.62   54.97 3428.75   70.15  3468.6   76.39 3604.76   87.04 3684.42   88.33
#Mann= 3 ,0,0
       0     .12       0 2646.15     .04       0 2692.96     .12       0
#XS Ineff= 2 , 0
       0  2493.8      43  2778.8       0   43.11
Permanent Ineff=
       F       F
Bank Sta=2646.15,2692.96
XS Rating Curve= 0 ,0
Exp/Cntr(USF)=0,0
Exp/Cntr=0.5,0.3

Type RM Length L Ch R = 3 ,132026  ,,,
Node Name=N River Rd Bridg
Bridge Culvert-0,0,0,0, 0
Deck Dist Width WeirC Skew NumUp NumDn MinLoCord MaxHiCord MaxSubmerge Is_Ogee
75,27.5,2.6,0, 65, 65, , , 0.98, 0, 2,2,,
       0   103.6     209   318.1     433   546.4   641.8   753.6   843.5   954.3
  1068.6  1183.8  1233.8  1283.8  1333.8  1383.8  1433.8  1483.8  1533.8  1583.8
  1633.8  1683.8  1733.8  1783.8  1833.8  1883.8  1933.8  1983.8  2033.8  2083.8
  2133.8  2183.8  2233.8  2283.8  2333.8  2383.8  2433.8  2483.8  2533.8  2568.8
  2568.8  2703.8  2703.8  2733.8  2783.8  2833.8  2883.8  2933.8  2983.8  3033.8
  3083.8  3133.8  3183.8  3233.8  3283.8  3333.8  3383.8  3433.8  3483.8  3533.8
  3583.8  3633.8  3683.8  3733.8  3783.8
   56.76   54.48   52.62   52.06   50.95   50.18   49.74   49.18   48.67   47.88
   47.01   46.87   46.45   46.14   45.86    45.6   45.36   45.09    44.8   44.46
   44.22      44   43.79   43.67   43.67   43.57   43.56   43.45   43.38   43.27
   43.24   43.17   43.16   43.07   43.02      43   43.07   43.16   43.25   43.27
   43.27   43.41   43.41   43.19   43.11   43.15   43.29   43.44   43.54   43.83
   44.28   44.83   45.56   46.53   47.44   48.19   48.98   49.89   50.72    51.4
   52.09   52.79   53.52   54.27   55.07
                                                                                
                                                                                
                                                                                
                                                                                
   42.32   42.32
                                                                                
                                        
   -58.1    45.5   150.9     260   374.9   488.3   583.7   695.5   785.4   896.2
  1010.5  1125.7  1175.7  1225.7  1275.7  1325.7  1375.7  1425.7  1475.7  1525.7
  1575.7  1625.7  1675.7  1725.7  1775.7  1825.7  1875.7  1925.7  1975.7  2025.7
  2075.7  2125.7  2175.7  2225.7  2275.7  2325.7  2375.7  2425.7  2475.7  2510.7
  2510.7  2645.7  2645.7  2675.7  2725.7  2775.7  2825.7  2875.7  2925.7  2975.7
  3025.7  3075.7  3125.7  3175.7  3225.7  3275.7  3325.7  3375.7  3425.7  3475.7
  3525.7  3575.7  3625.7  3675.7  3725.7
   56.76   54.48   52.62   52.06   50.95   50.18   49.74   49.18   48.67   47.88
   47.01   46.87   46.45   46.14   45.86    45.6   45.36   45.09    44.8   44.46
   44.22      44   43.79   43.67   43.67   43.57   43.56   43.45   43.38   43.27
   43.24   43.17   43.16   43.07   43.02      43   43.07   43.16   43.25   43.27
   43.27   43.41   43.41   43.19   43.11   43.15   43.29   43.44   43.54   43.83
   44.28   44.83   45.56   46.53   47.44   48.19   48.98   49.89   50.72    51.4
   52.09   52.79   53.52   54.27   55.07
                                                                                
                                                                                
                                                                                
                                                                                
   42.32   42.32
                                                                                
                                        
Pier Skew, UpSta & Num, DnSta & Num=  ,2583.8, 2 ,2525.7, 2 , 0 , 0 , 0 ,,
       1       1
       0      43
       1       1
       0      43
Pier Skew, UpSta & Num, DnSta & Num=  ,2598.8, 2 ,2540.7, 2 , 0 , 0 , 0 ,,
       1       1
       0      43
       1       1
       0      43
Pier Skew, UpSta & Num, DnSta & Num=  ,2613.8, 2 ,2555.7, 2 , 0 , 0 , 0 ,,
       1       1
       0      43
       1       1
       0      43
Pier Skew, UpSta & Num, DnSta & Num=  ,2628.8, 2 ,2570.7, 2 , 0 , 0 , 0 ,,
       1       1
       0      43
       1       1
       0      43
Pier Skew, UpSta & Num, DnSta & Num=  ,2643.8, 2 ,2585.7, 2 , 0 , 0 , 0 ,,
       1       1
       0      43
       1       1
       0      43
Pier Skew, UpSta & Num, DnSta & Num=  ,2658.8, 2 ,2600.7, 2 , 0 , 0 , 0 ,,
       1       1
       0      43
       1       1
       0      43
Pier Skew, UpSta & Num, DnSta & Num=  ,2673.8, 2 ,2615.7, 2 , 0 , 0 , 0 ,,
       1       1
       0      43
       1       1
       0      43
Pier Skew, UpSta & Num, DnSta & Num=  ,2688.8, 2 ,2630.7, 2 , 0 , 0 , 0 ,,
       1       1
       0      43
       1       1
       0      43
Abutment Skew #Up #Dn= , 2 , 2
  2568.8  2588.8
   42.32   32.32
  2510.7  2530.7
   42.32   32.32
BR Coef=-1 , 1 , 1 ,0.9, 0 ,,,0.8,0,1.2,0,
WSPro=,,,, 1 ,,,, 0 ,,,, 0 ,,,,-1 ,-1 ,-1 , 0 , 0 , 0 , 0 , 0
BC Design=,, 0 ,, 0 ,,,,,,
BC Use User HTab Curves=0
BC User HTab FreeFlow(D)= 0

Type RM Length L Ch R = 1 ,131974  ,518.9,518.9,518.9
XS GIS Cut Line= 6
2424514.94662153833929.0353752692424745.31457716833649.314219956
2425022.04600041832826.335992493 2425233.3983525 832144.83248984
2425653.22751447830862.3406662832425570.65001851830402.641947818
#Sta/Elev= 30
       0   55.45  191.47   52.57  234.09   54.08  450.75   49.15 1480.32   44.29
  1645.2   41.56 1731.07   42.24 1775.73    40.3  1923.9   39.99 2038.69   43.81
 2072.15    42.8 2090.81   37.75 2103.07   41.26 2168.06   42.88 2331.16   40.03
 2455.44   40.46 2589.01   36.66 2597.42   32.46  2613.2   30.97 2634.73   31.68
 2640.51   36.69 2672.12   36.87 2714.39   40.51 2971.89   41.03 3400.49   48.85
 3437.16      53 3490.49   70.54 3533.83   76.27 3663.83   86.16 3760.67   86.34
#Mann= 3 ,0,0
       0     .12       0 2589.01     .04       0 2640.51     .12       0
#XS Ineff= 2 , 0
       0 2483.25      43 2673.15       0   43.11
Permanent Ineff=
       F       F
Bank Sta=2589.01,2640.51
XS Rating Curve= 0 ,0
Exp/Cntr(USF)=0,0
Exp/Cntr=0.5,0.3

Type RM Length L Ch R = 1 ,131455  ,466.1,466.1,466.1
BEGIN DESCRIPTION:
Willow Creek 13.0
END DESCRIPTION:
XS GIS Cut Line= 6
      2426105.63       834202.082425700.13048348831171.133791298
2425692.07772532831122.0969287092425707.68311684830977.293063577
2425836.14085427830662.5621628142425552.78964724830084.451245311
#Sta/Elev= 30
       0   76.11   278.1   73.48  615.73   62.29  910.32   57.53    1003   52.03
 1174.76   47.69  1330.7   48.03 1761.01   41.34 2033.41   43.49 2244.28   40.73
    2397   43.65  2655.2   37.82 2985.45   39.13  3060.1  36.831 3080.39   30.33
  3089.5   33.31  3098.6  40.586  3188.1   39.68  3244.2   43.27 3399.03   41.85
 3590.29   47.72 3653.33   53.19  3680.3   52.44 3699.81   57.26 3736.34   58.22
 3817.61   68.84 4003.07   77.13 4061.53   81.08  4182.1   94.66 4237.04   95.41
#Mann= 3 ,0,0
       0     .12       0  3060.1     .04       0  3098.6     .12       0
Bank Sta=3060.1,3098.6
XS Rating Curve= 0 ,0
Exp/Cntr=0.3,0.1

Type RM Length L Ch R = 1 ,130989  ,249.4,249.4,249.4
BEGIN DESCRIPTION:
Willow Creek 12.0
END DESCRIPTION:
XS GIS Cut Line= 4
      2426317.86       834195.75      2426069.81       831041.98
      2425981.62       830917.46      2425649.36       830020.42
#Sta/Elev= 30
       0   75.87   254.1    75.2   507.5   70.82     932   60.17   948.5    56.5
  1014.3   56.41  1201.9   47.57  1600.1   47.14  1725.2   41.04  1985.2   42.24
  2215.6   39.73    2367   42.85    2548   39.47  2656.6    41.6  2923.1      38
  3018.6   40.04 3259.31   38.13  3290.2    34.2  3290.7   31.96  3349.3   31.96
 3355.56   38.19  3435.1   41.45  3529.6   40.44    3687   53.65    3729   53.61
  3753.2   57.56    3806   59.56  4040.4   88.14  4106.9   93.86  4272.7   95.91
#Mann= 3 ,0,0
       0     .12       0 3259.31     .04       0 3355.56     .12       0
Bank Sta=3259.31,3355.56
XS Rating Curve= 0 ,0
Exp/Cntr(USF)=0,0
Exp/Cntr=0.3,0.1

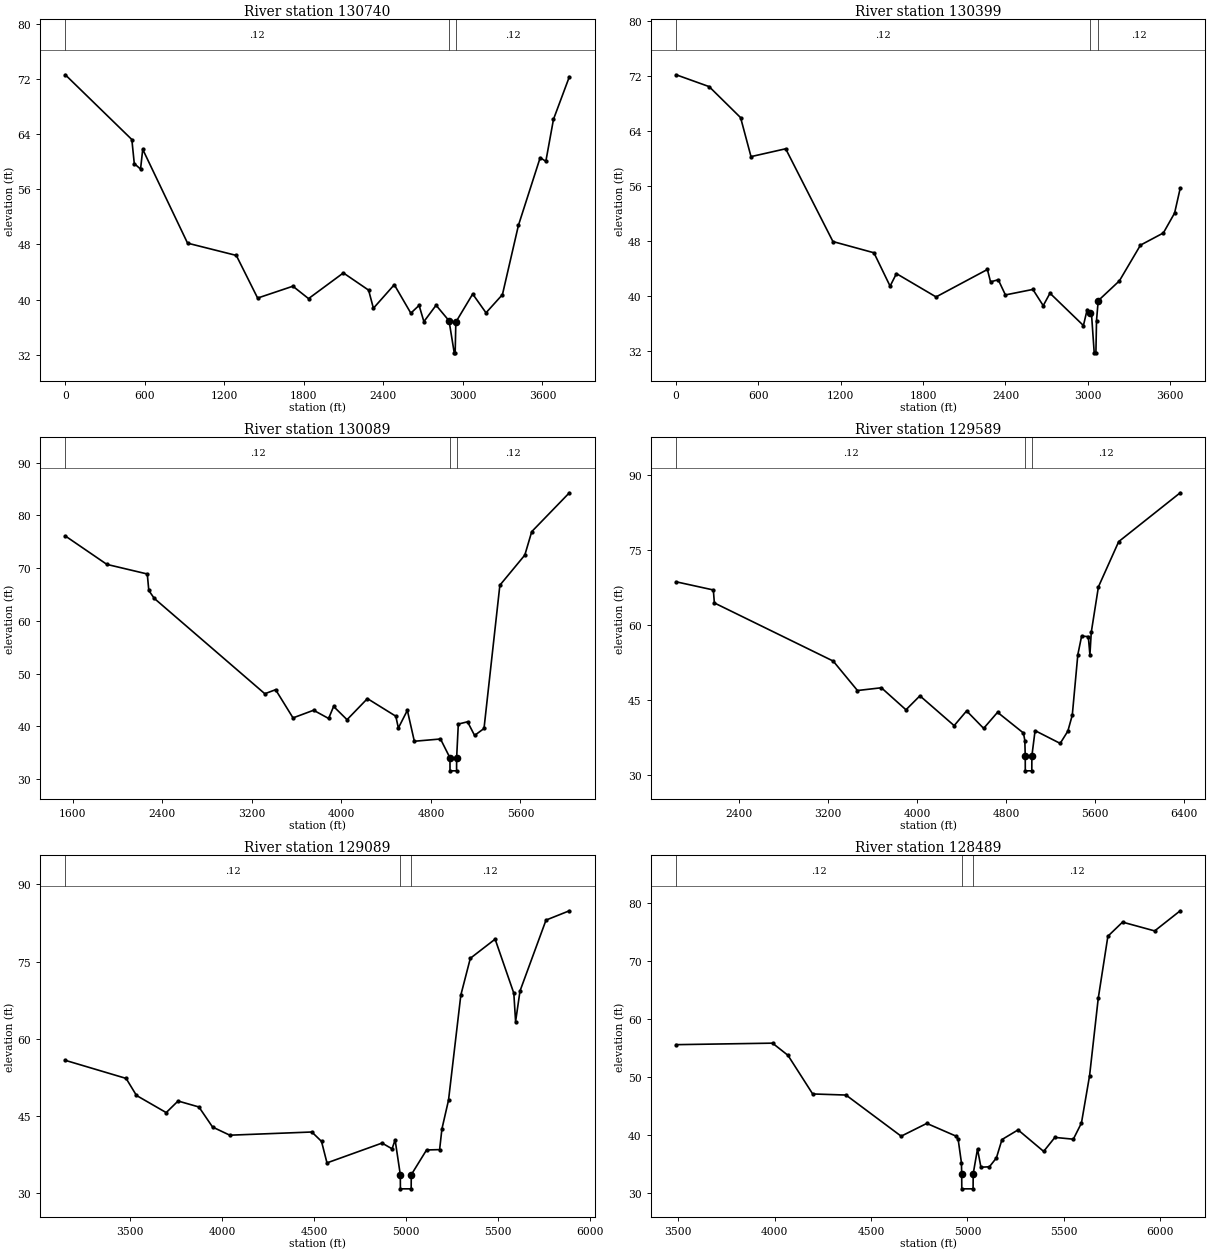
Type RM Length L Ch R = 1 ,130740  ,341.3,341.3,341.3
XS GIS Cut Line= 4
 2426357.1582415833850.2360481852426242.63630005831021.544094523
2426156.74484397830866.9394735742425996.41412595830088.190271756
#Sta/Elev= 30
       0   72.63     502   63.23   520.4   59.74   567.7   58.94   584.1   61.81
   922.4   48.19  1290.1   46.41    1451   40.22    1717   41.94  1835.2   40.14
  2097.9   43.87  2288.3   41.37  2324.5   38.74  2482.1   42.16  2606.9   38.03
  2669.2   39.16  2705.4    36.8  2797.3   39.18  2895.236.92095 2934.37   32.27
  2941.4   32.27  2946.4   36.73  3073.6   40.81  3174.1   38.08    3298   40.72
  3418.6   50.77  3582.7    60.6  3625.5   60.07  3683.2   66.17    3803   72.35
#Mann= 3 ,0,0
       0     .12       0  2895.2     .04       0  2946.4     .12       0
Bank Sta=2895.2,2946.4
XS Rating Curve= 0 ,0
Exp/Cntr(USF)=0,0
Exp/Cntr=0.3,0.1

Type RM Length L Ch R = 1 ,130399  ,309.4,309.4,309.4
XS GIS Cut Line= 3
2426456.58681934833933.4137396882426518.42866772 830990.77245429
2426321.26840336830287.385229145
#Sta/Elev= 30
       0   72.12   240.4    70.4   469.7   65.89   545.6   60.22   798.3   61.36
  1142.8   47.87  1441.5   46.24  1559.3   41.39  1605.5   43.21  1894.3   39.82
  2268.4   43.81  2291.4   42.01  2347.7   42.32  2399.7   40.11  2599.9   40.91
  2675.4   38.55  2724.6   40.36  2968.4   35.66  2995.6   37.98    301637.54132
  3026.7   37.51 3046.96   31.69 3059.31   31.69  3063.8   36.38    307639.26942
  3230.7   42.16  3384.1   47.35    3551   49.12  3632.8   52.01  3673.8   55.62
#Mann= 3 ,0,0
       0     .12       0    3016     .04       0    3076     .12       0
Bank Sta=3016,3076
XS Rating Curve= 0 ,0
Exp/Cntr(USF)=0,0
Exp/Cntr=0.3,0.1

Type RM Length L Ch R = 1 ,130089  ,500,500,500
BEGIN DESCRIPTION:
Willow Creek 10.0
END DESCRIPTION:
XS GIS Cut Line= 3
      2426564.18       834326.21      2426795.53       830867.24
      2427022.73       829855.33
#Sta/Elev= 30
  1533.3    76.1  1904.7   70.71  2265.7   68.89  2279.4   65.76  2327.9   64.27
  3316.1   46.18  3412.3   46.95  3567.9    41.6  3751.7   43.05    3886   41.49
  3930.6   43.77  4050.6   41.26  4232.7   45.26  4486.3   41.92  4509.1   39.68
  4589.5   43.03  4651.9   37.17  4885.6    37.6  4970.2   34.03  4970.7   31.56
  5029.3   31.56  5029.8   34.03  5044.8   40.43  5127.4   40.86  5190.2   38.27
  5274.4   39.59  5416.1   66.76  5639.1   72.48  5700.8   76.92  6037.1   84.29
#Mann= 3 ,0,0
  1533.3     .12       0  4970.2     .04       0  5029.8     .12       0
Bank Sta=4970.2,5029.8
XS Rating Curve= 0 ,0
Exp/Cntr=0.3,0.1

Type RM Length L Ch R = 1 ,129589  ,500,500,500
BEGIN DESCRIPTION:
Willow Creek 9.0
END DESCRIPTION:
XS GIS Cut Line= 3
        2426803.       834135.21      2427261.87       831001.63
      2427395.31       829645.18
#Sta/Elev= 30
    1833   68.64  2167.3   67.01  2176.4   64.42  3244.4   52.81  3462.5   46.93
  3677.4   47.48  3898.4   43.08  4023.7   45.87  4331.5   39.92  4443.4   42.86
  4596.5   39.37  4721.4   42.58  4954.3   38.44  4966.6   36.94  4970.2   33.85
  4970.7   30.89  5029.3   30.89  5029.8   33.85  5058.7   38.92  5284.3   36.37
  5353.2   38.82  5393.1   42.02  5442.9    54.1  5476.9   57.79    5537    57.7
  5551.5   54.05  5563.6   58.55  5627.9   67.63  5810.3   76.67    6363   86.42
#Mann= 3 ,0,0
    1833     .12       0  4970.2     .04       0  5029.8     .12       0
Bank Sta=4970.2,5029.8
XS Rating Curve= 0 ,0
Exp/Cntr=0.3,0.1

Type RM Length L Ch R = 1 ,129089  ,600,600,600
BEGIN DESCRIPTION:
Willow Creek 8.0
END DESCRIPTION:
XS GIS Cut Line= 3
      2427701.01       832597.13      2427680.88       830744.64
      2427643.69       829855.32
#Sta/Elev= 30
  3147.4   55.81  3478.2    52.3  3534.6   48.99  3696.4   45.66  3760.9   47.91
  3874.4   46.75  3948.8   42.85  4042.4   41.27  4488.8   41.89  4541.4   40.07
  4571.2   35.89  4870.8   39.74  4925.5   38.62  4941.9   40.37  4970.2   33.59
  4970.7   30.85  5029.3   30.85  5029.8   33.59    5113    38.4  5184.1   38.47
  5196.6   42.48  5232.5   48.07  5299.5   68.48  5351.2   75.63  5486.1   79.35
  5587.8   68.85  5597.5   63.35  5621.5   69.28    5763   83.05  5890.1   84.86
#Mann= 3 ,0,0
  3147.4     .12       0  4970.2     .04       0  5029.8     .12       0
Bank Sta=4970.2,5029.8
XS Rating Curve= 0 ,0
Exp/Cntr=0.3,0.1

Type RM Length L Ch R = 1 ,128489  ,500,500,500
BEGIN DESCRIPTION:
Willow Creek 7.0
END DESCRIPTION:
XS GIS Cut Line= 3
      2428025.82       832568.46      2427978.38       831059.31
      2428312.41        830008.2
#Sta/Elev= 30
  3490.1   55.59  3989.6   55.85  4069.6   53.75  4197.8   47.07  4370.5   46.88
  4656.5   39.77  4789.3   41.98  4940.9   39.78  4951.8   39.25  4968.8   35.19
  4970.2   33.27  4970.7   30.67  5029.3   30.67  5029.8   33.27  5052.2   37.56
  5069.9   34.41  5113.7   34.48  5150.1   36.01    5179   39.19  5262.4   40.86
  5395.1   37.14  5453.2   39.56  5548.8   39.25  5590.9   42.04  5633.1   50.23
    5678   63.59    5728   74.33    5804   76.77  5970.5   75.25  6102.9   78.73
#Mann= 3 ,0,0
  3490.1     .12       0  4970.2     .04       0  5029.8     .12       0
Bank Sta=4970.2,5029.8
XS Rating Curve= 0 ,0
Exp/Cntr=0.3,0.1