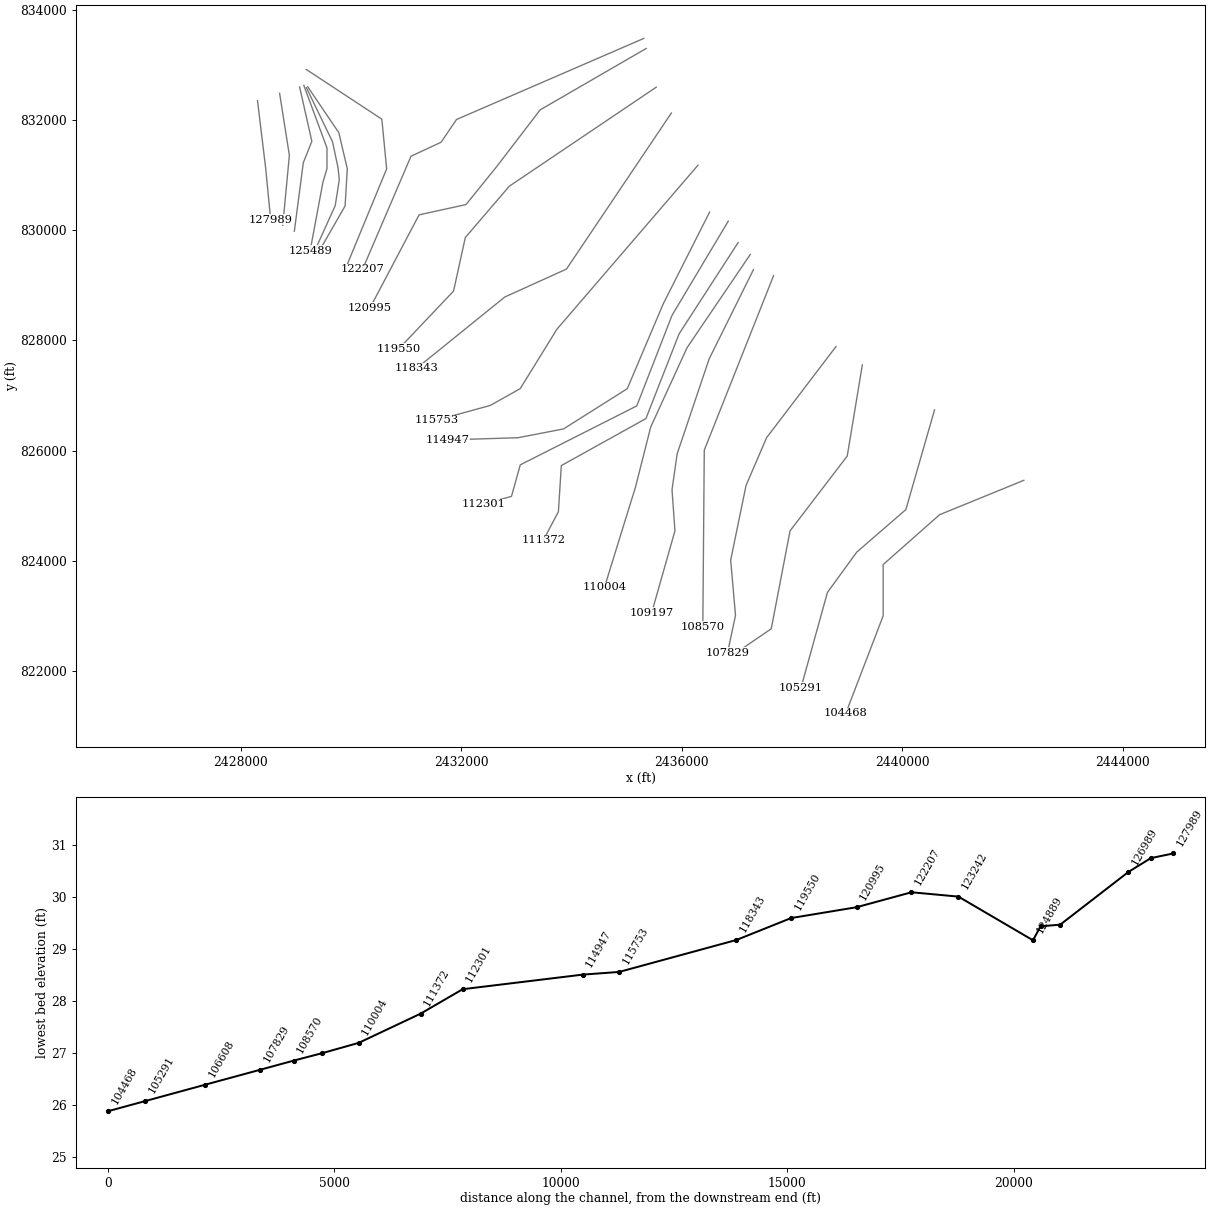
HEC-RAS study WillowCreek.prj: S-21-57 over Willow Creek

--- WillowCreek.g02 (geometry) --- (continued)

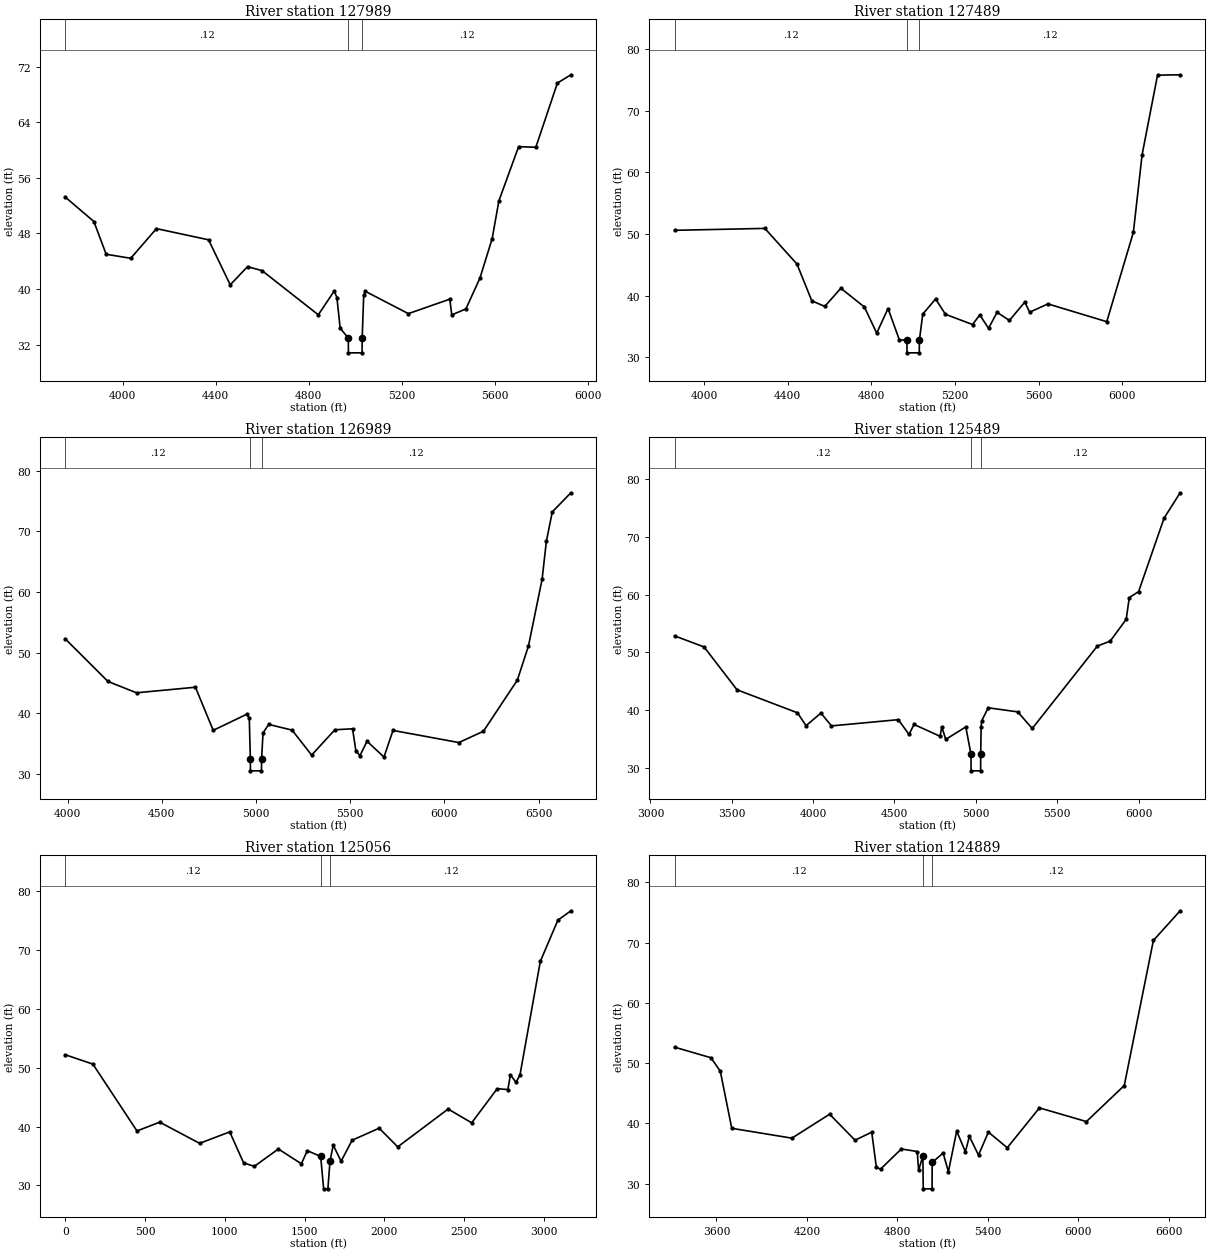
Type RM Length L Ch R = 1 ,127989  ,500,500,500
BEGIN DESCRIPTION:
Willow Creek 6.0
END DESCRIPTION:
XS GIS Cut Line= 3
      2428302.87       832348.67      2428452.55        831112.1
      2428541.69        830189.7
#Sta/Elev= 30
  3754.4   53.22  3876.9   49.72  3929.6   45.01  4035.3   44.43  4145.7    48.7
  4369.7   47.09  4462.8   40.61    4537   43.23  4599.4   42.66  4841.2    36.3
  4909.6   39.72  4921.1   38.79  4935.3   34.37  4970.2   32.95  4970.7   30.83
  5029.3   30.83  5029.8   32.95  5036.3   39.08  5042.7   39.69  5228.2   36.47
  5406.3   38.55  5414.7   36.29  5475.4   37.15  5535.6   41.56  5588.4   47.26
  5617.2   52.69    5702   60.49    5776    60.4  5868.7   69.64  5926.7   70.83
#Mann= 3 ,0,0
  3754.4     .12       0  4970.2     .04       0  5029.8     .12       0
Bank Sta=4970.2,5029.8
XS Rating Curve= 0 ,0
Exp/Cntr=0.3,0.1

Type RM Length L Ch R = 1 ,127489  ,500,500,500
BEGIN DESCRIPTION:
Willow Creek 5.0
END DESCRIPTION:
XS GIS Cut Line= 3
      2428704.09       832482.48      2428881.46       831355.66
      2428761.41       830084.62
#Sta/Elev= 30
  3859.3    50.6  4290.7   50.91  4444.6   45.12  4515.4   39.16  4577.6   38.27
  4654.2   41.21  4766.7   38.17  4825.7   33.94  4879.9   37.92  4933.9   32.85
  4970.2   32.79  4970.7   30.74  5029.3   30.74  5029.8   32.79  5045.8   37.01
  5107.3   39.48  5154.3   36.99  5283.8   35.33  5318.6   36.88  5360.5   34.72
  5401.3    37.3  5460.4   35.99  5533.8   38.97    5557   37.33  5644.5   38.67
  5925.8   35.79    6053   50.27  6094.9   62.87  6168.6   75.75  6276.7   75.81
#Mann= 3 ,0,0
  3859.3     .12       0  4970.2     .04       0  5029.8     .12       0
Bank Sta=4970.2,5029.8
XS Rating Curve= 0 ,0
Exp/Cntr=0.3,0.1

Type RM Length L Ch R = 1 ,126989  ,1500,1500,1500
BEGIN DESCRIPTION:
Willow Creek 4.0
END DESCRIPTION:
XS GIS Cut Line= 4
      2429067.12       832597.09      2429289.27       831610.39
      2429133.99       831221.44      2428971.58       829979.52
#Sta/Elev= 30
  3988.6   52.23  4214.6   45.22  4366.1   43.35  4678.7   44.27  4773.2   37.15
  4951.7   39.82  4964.6   39.14  4970.2   32.47  4970.7   30.47  5029.3   30.47
  5029.8   32.47  5037.6   36.74  5067.6   38.13  5191.7   37.19  5295.4   33.07
  5418.8   37.25  5512.5   37.41  5530.2   33.79  5551.7   32.97  5589.3   35.35
  5679.4   32.75  5727.3   37.14  6076.6   35.14  6207.1      37  6387.2   45.45
  6446.2   51.09  6518.5    62.1  6541.2   68.37  6572.6   73.21  6671.3   76.36
#Mann= 3 ,0,0
  3988.6     .12       0  4970.2     .04       0  5029.8     .12       0
Bank Sta=4970.2,5029.8
XS Rating Curve= 0 ,0
Exp/Cntr=0.3,0.1

Type RM Length L Ch R = 1 ,125489  ,433.1,433.1,433.1
BEGIN DESCRIPTION:
Willow Creek 3.0
END DESCRIPTION:
XS GIS Cut Line= 5
      2429143.55       832625.73      2429563.88       831488.93
      2429563.88       831116.36       2429488.9        830860.3
      2429258.18       829626.08
#Sta/Elev= 30
  3148.6   52.85  3329.4   50.94  3532.1   43.51  3903.6   39.52  3956.5   37.29
  4047.7   39.47  4112.6   37.25  4523.4   38.33  4589.2   35.77  4620.1    37.5
  4780.1   35.45  4790.7    37.1  4814.9   34.91  4938.2   37.07  4970.2   32.33
  4970.7   29.46  5029.3   29.46  5029.8   32.33  5032.5   37.11  5036.3   38.15
  5076.1   40.39  5257.4   39.68  5346.6    36.8  5747.1    51.1  5825.5   51.94
  5924.1   55.72    5943   59.49  6000.3   60.53  6156.8   73.26  6255.6   77.66
#Mann= 3 ,0,0
  3148.6     .12       0  4970.2     .04       0  5029.8     .12       0
Bank Sta=4970.2,5029.8
XS Rating Curve= 0 ,0
Exp/Cntr=0.3,0.1

Type RM Length L Ch R = 1 ,125056  ,166.9,166.9,166.9
XS GIS Cut Line= 6
2429190.79031156832583.4218665282429664.05054148831602.392848248
2429765.11131975831129.1326183242429787.29539302 830914.68657664
 2429713.3484821830443.8912437462429341.14903044829620.615635441
#Sta/Elev= 30
       0   52.17   172.4   50.59   448.8   39.25   591.3   40.74   841.4   37.15
  1030.2   39.09  1117.1   33.84  1184.2   33.24  1335.1   36.19  1479.4   33.68
  1516.3   35.91  1600.334.92726 1618.83   29.43 1645.42   29.43  1658.934.15485
  1678.9   36.84  1728.3   34.12  1797.7   37.68    1967   39.72  2083.3   36.55
  2399.3   42.97  2546.8   40.63  2706.7   46.41  2773.7   46.28  2789.7   48.78
  2824.1    47.5  2849.3   48.71    2977   68.01  3086.9   74.99  3168.8    76.6
#Mann= 3 ,0,0
       0     .12       0  1600.3     .04       0  1658.9     .12       0
Bank Sta=1600.3,1658.9
XS Rating Curve= 0 ,0
Exp/Cntr(USF)=0,0
Exp/Cntr=0.3,0.1

Type RM Length L Ch R = 1 ,124889  ,1646.8,1646.8,1646.8
BEGIN DESCRIPTION:
Willow Creek 2.0
END DESCRIPTION:
XS GIS Cut Line= 5
      2429214.73       832599.32      2429778.59       831766.97
      2429932.49       831112.58      2429892.69       830437.94
      2429395.96       829572.01
#Sta/Elev= 30
  3322.4   52.66  3563.2   50.91  3625.4   48.66  3701.3    39.2  4099.9   37.57
    4350   41.54  4518.6   37.23  4629.2   38.56  4659.9   32.76  4687.5   32.42
  4825.4   35.78  4930.9   35.35  4940.2   32.23  4968.4   34.62  4970.7   29.16
  5029.3   29.16  5030.2   33.54  5102.6    35.1  5137.7   32.01  5192.6   38.74
  5250.4    35.3  5276.5   37.86  5337.3   34.76  5402.9   38.57  5527.9   35.98
  5741.3   42.59  6052.7   40.32  6303.7    46.3  6496.8   70.37  6674.1   75.29
#Mann= 3 ,0,0
  3322.4     .12       0  4968.4     .04       0  5030.2     .12       0
Bank Sta=4968.4,5030.2
XS Rating Curve= 0 ,0
Exp/Cntr=0.3,0.1

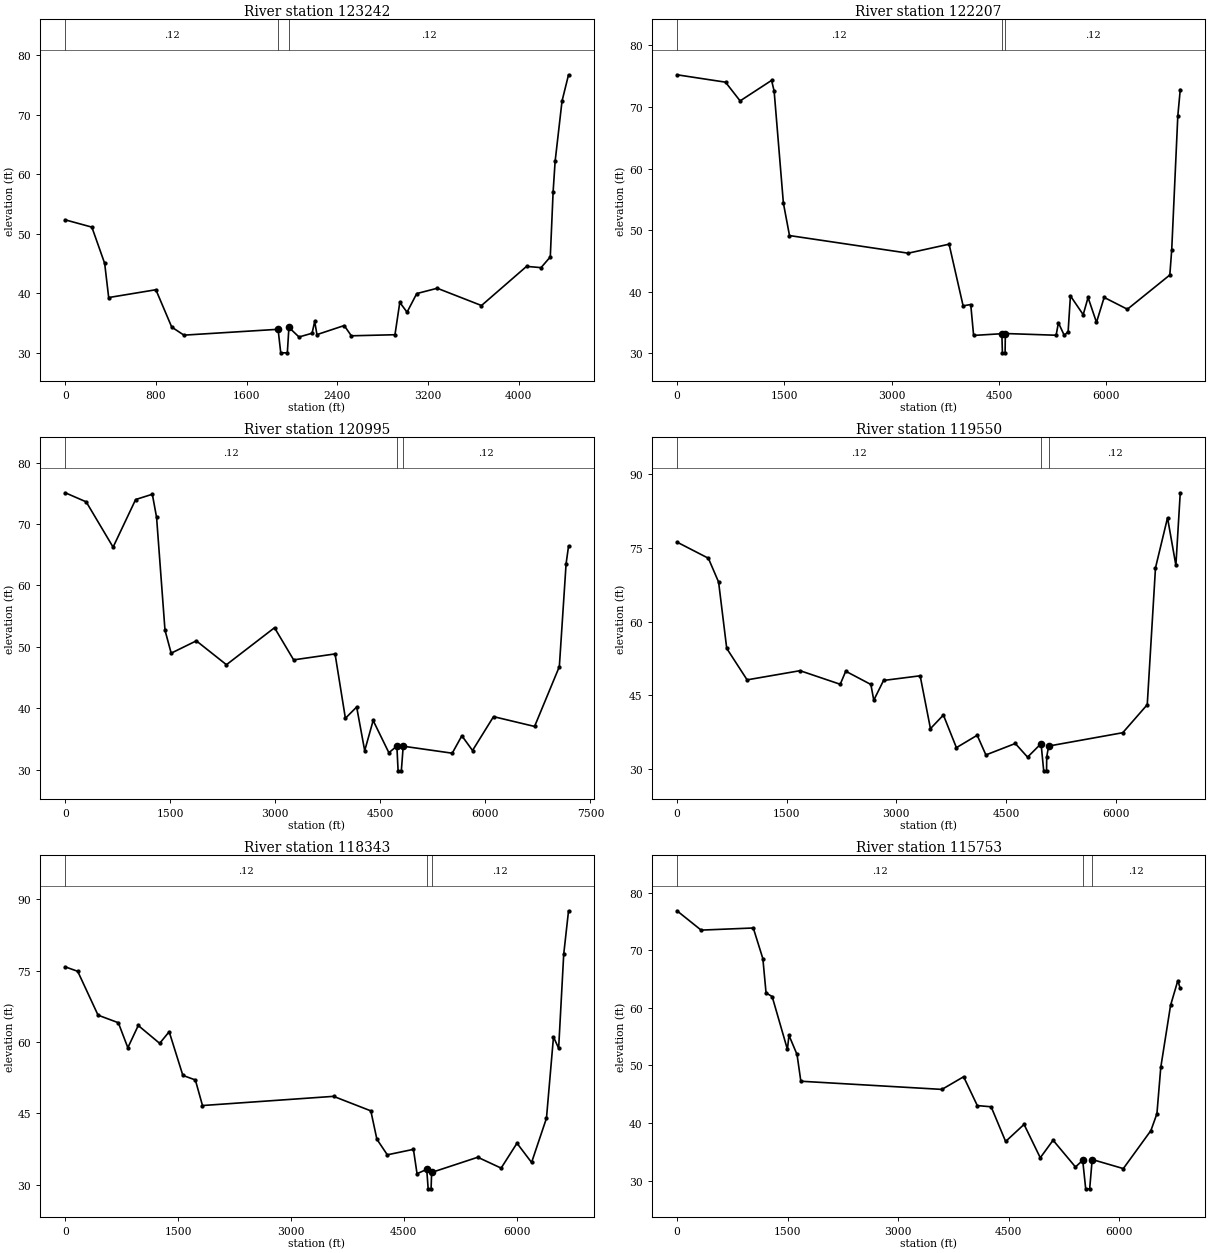
Type RM Length L Ch R = 1 ,123242  ,1035.6,1035.6,1035.6
XS GIS Cut Line= 4
2429187.26835221832914.6639122492430559.31162766832012.238860159
 2430646.5863887831110.3996626892429925.56276898829362.770477731
#Sta/Elev= 30
       0   52.32  234.52    51.1  347.57   45.01  382.91   39.28  799.16   40.59
  939.03   34.32 1046.53   32.971877.012   33.95 1900.56      30 1958.61      30
1972.512  34.269 2061.56   32.66 2176.92   33.29 2199.99   35.28 2219.77   33.06
 2460.39   34.58 2523.02   32.86 2907.93   33.04 2950.52   38.47  3014.4   36.82
 3100.09   39.95 3280.99   40.84 3670.99   37.94 4068.48   44.51 4196.25    44.3
 4277.88    46.1 4302.72   57.01 4320.47   62.14 4381.47   72.27 4438.79   76.67
#Mann= 3 ,0,0
       0     .12       01877.012     .04       01972.512     .12       0
Bank Sta=1877.012,1972.512
XS Rating Curve= 0 ,0
Exp/Cntr(USF)=0,0
Exp/Cntr=0.3,0.1

Type RM Length L Ch R = 1 ,122207  ,1211.7,1211.7,1211.7
XS GIS Cut Line= 5
2435312.36128393833477.2585842372431913.68662314832005.760760993
2431634.34353795 831593.397159042431088.95941924831340.658177198
2430211.02400863829292.142219111
#Sta/Elev= 30
       0   75.22  678.08   74.02  881.96   70.98 1321.77   74.31 1357.46   72.57
 1486.44   54.41 1571.97   49.12  3230.4   46.26 3801.69   47.723997.749   37.71
4104.249   37.934144.349   32.914539.249   33.194546.439 30.08344584.329 30.0834
4587.679   33.225297.149   32.945329.049   34.965411.349   32.915464.949   33.54
5497.049   39.335675.549   36.285743.349   39.075861.249   35.035968.249   39.08
6293.049   37.166885.649   42.72 6912.19    46.8 6997.42   68.56 7031.44   72.81
#Mann= 3 ,0,0
       0     .12       04539.249     .04       04587.679     .12       0
Bank Sta=4539.249,4587.679
XS Rating Curve= 0 ,0
Exp/Cntr(USF)=0,0
Exp/Cntr=0.3,0.1

Type RM Length L Ch R = 1 ,120995  ,1445,1445,1445
XS GIS Cut Line= 6
 2435355.9972737833294.8036266032433431.92857639832181.005265482
2432645.29946532831154.4294537362432086.61329493 830462.72276659
2431235.28198767830276.4940431272430344.04452539828587.133480289
#Sta/Elev= 30
       0   75.11  298.86   73.63  683.02   66.25 1005.08   74.01 1243.39   74.87
 1304.04    71.1  1424.2   52.71 1512.54   48.97 1871.52   50.98 2301.69   47.09
 2988.17   53.12 3261.11   47.88  3852.9   48.85  4000.5   38.36  4161.3    40.2
  4276.2   33.08  4396.9      38  4621.3   32.75  4735.5   33.83 4753.18 29.7959
  4799.3 29.7959  4826.2   33.81  5526.3   32.67  5663.5   35.51  5815.9   33.11
    6116   38.63  6702.1   37.03 7055.85   46.78 7152.21   63.54 7187.15   66.41
#Mann= 3 ,0,0
       0     .12       0  4735.5     .04       0  4826.2     .12       0
Bank Sta=4735.5,4826.2
XS Rating Curve= 0 ,0
Exp/Cntr(USF)=0,0
Exp/Cntr=0.3,0.1

Type RM Length L Ch R = 1 ,119550  ,1206.7,1206.7,1206.7
XS GIS Cut Line= 5
2435538.14796616832592.5061144892432871.43434381830795.274058487
2432073.31124325829864.1304411752431860.47841644828893.080668835
2430862.82454075827842.218586439
#Sta/Elev= 30
       0   76.21  429.32   72.92  569.44   68.06  680.52   54.54  959.33   48.13
 1683.49      50 2233.43   47.23  2308.6   49.89 2652.81   47.19 2692.37   43.98
 2826.13   48.013326.803   48.963467.703   38.193644.803   40.963822.903   34.31
4107.203   36.844226.203   32.834628.503   35.164796.503   32.384981.203   35.13
5017.103 29.58765056.353 29.58765058.343   32.455085.303   34.646099.003   37.36
6433.803   43.07 6546.49   70.96 6711.27   81.16 6825.62   71.47  6885.3   86.26
#Mann= 3 ,0,0
       0     .12       04981.203     .04       05085.303     .12       0
Bank Sta=4981.203,5085.303
XS Rating Curve= 0 ,0
Exp/Cntr(USF)=0,0
Exp/Cntr=0.3,0.1

Type RM Length L Ch R = 1 ,118343  ,2589.9,2589.9,2589.9
XS GIS Cut Line= 4
2435812.38400235832123.4404415352433908.99437453829292.142219111
2432791.62203375828786.6642554282431195.37583264827496.365242866
#Sta/Elev= 30
       0   75.78  165.24   74.85  435.75   65.64  705.45   64.05  831.96    58.8
  970.32   63.47 1254.96   59.72 1381.47   62.16 1563.32   52.99 1729.47   52.03
 1824.24   46.66 3566.27   48.594062.223   45.544142.523   39.594281.423   36.31
4628.523   37.464676.423   32.354805.303   33.254824.503 29.16664863.233 29.1666
4870.423   32.615483.823    35.85794.323   33.526005.223   38.756199.323    34.7
6397.123      446490.423   61.06 6559.06   58.69 6626.56   78.45 6690.54   87.56
#Mann= 3 ,0,0
       0     .12       04805.303     .04       04870.423     .12       0
Bank Sta=4805.303,4870.423
XS Rating Curve= 0 ,0
Exp/Cntr(USF)=0,0
Exp/Cntr=0.3,0.1

Type RM Length L Ch R = 1 ,115753  ,806.6,806.6,806.6
XS GIS Cut Line= 5
 2436296.1571335831177.3789987612433736.06770274828201.373981688
2433070.96511895827123.9077959412432525.58100023826817.960607396
2431554.53122789826551.919573878
#Sta/Elev= 30
       0   76.87  327.19   73.51 1034.71   73.88 1164.54   68.55 1207.82   62.59
 1290.34   61.97 1497.39   52.79 1518.33   55.23 1627.75    51.9 1679.54   47.25
 3592.41   45.83  3886.6   48.03 4072.16   43.024259.745   42.814456.345   36.78
4706.145   39.754926.045   33.955099.645      375403.445   32.355501.245   33.51
5542.115 28.55195595.945 28.55195629.635   33.656051.945   32.076426.145   38.68
6507.745   41.61 6559.73   49.64  6692.4   60.42 6791.05   64.73 6824.03   63.37
#Mann= 3 ,0,0
       0     .12       05501.245     .04       05629.635     .12       0
Bank Sta=5501.245,5629.635
XS Rating Curve= 0 ,0
Exp/Cntr(USF)=0,0
Exp/Cntr=0.3,0.1

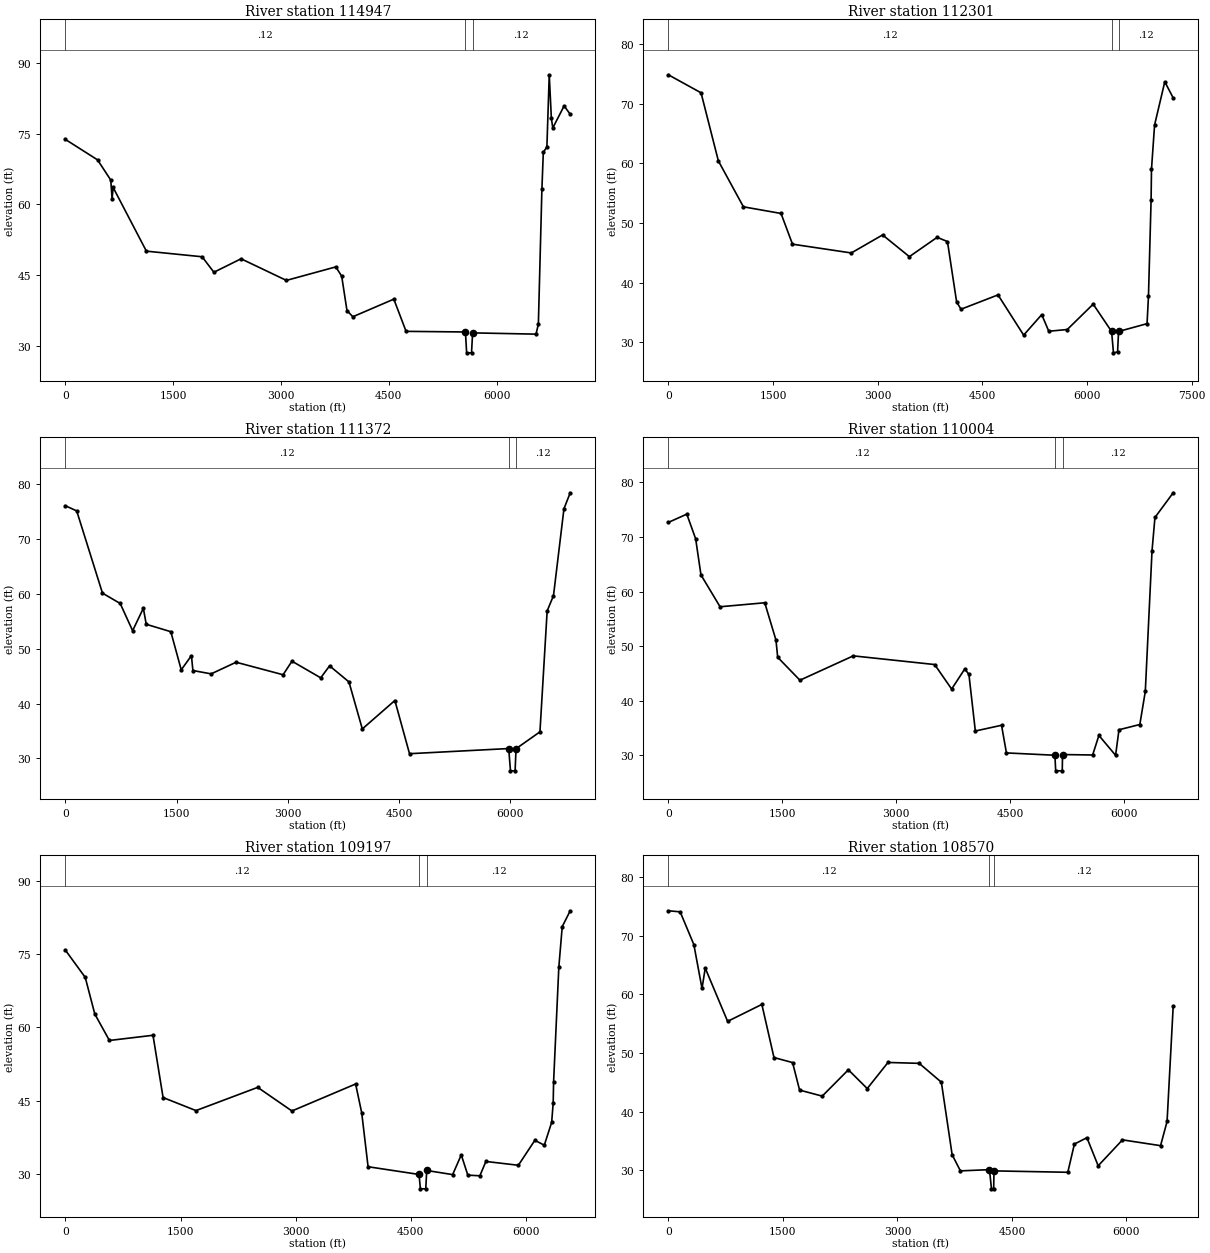
Type RM Length L Ch R = 1 ,114947  ,2646.4,2646.4,2646.4
XS GIS Cut Line= 6
2436506.86475571830327.0078165012435665.68101097828662.947260791
2435012.16395629827121.7016839362433855.78616782826392.294953767
2433031.05896392826232.6703336572431754.06200303826192.764178629
#Sta/Elev= 30
       0   73.82  448.11   69.47  631.92   65.18   650.3   61.22     665   63.61
 1127.33   50.09 1902.68    48.9  2066.6   45.61 2444.34   48.47  3075.1   43.88
 3762.64   46.75 3844.48   44.77  3917.8   37.48 3999.26   36.16 4569.47    39.9
 4740.14   33.06 5565.97   32.93 5582.58    28.5 5650.54    28.5 5665.72  32.739
 6547.57   32.47 6580.39   34.57 6629.63    63.3 6649.32   71.09 6698.96    72.2
 6731.79   87.54 6761.33   78.27 6781.02   76.25 6938.58   80.93 7023.52   79.16
#Mann= 3 ,0,0
       0     .12       0 5565.97     .04       0 5665.72     .12       0
Bank Sta=5565.97,5665.72
XS Rating Curve= 0 ,0
Exp/Cntr(USF)=0,0
Exp/Cntr=0.3,0.1

Type RM Length L Ch R = 1 ,112301  ,928.9,928.9,928.9
XS GIS Cut Line= 6
2436845.25404783830162.3137287622435824.70917647828453.030082329
2435185.09062807826810.0825230542433070.96511895825740.494421649
2432911.34049883825168.506199586 2432412.0305175825028.867346813
#Sta/Elev= 30
       0   74.82  468.83    71.8  717.21   60.38 1076.39   52.69 1615.17   51.58
 1779.48   46.43 2622.51   44.96 3070.59   47.98  3454.5   44.34 3852.74   47.58
 4000.32   46.87 4131.93   36.73 4195.19   35.53 4724.66   37.93 5092.34   31.19
 5351.37   34.62 5452.67   31.84  5717.4   32.13 6088.75   36.38 6352.69    31.8
 6379.44   28.22 6438.28   28.37 6452.69    31.8  6860.7   33.11 6881.14   37.72
 6918.61   53.82 6924.31   58.99 6968.59    66.4 7115.08   73.65 7235.44   70.94
#Mann= 3 ,0,0
       0     .12       0 6352.69     .04       0 6452.69     .12       0
Bank Sta=6352.69,6452.69
XS Rating Curve= 0 ,0
Exp/Cntr(USF)=0,0
Exp/Cntr=0.3,0.1

Type RM Length L Ch R = 1 ,111372  ,1367.5,1367.5,1367.5
XS GIS Cut Line= 6
2437023.97630107829773.2855632612435951.93170887828115.890371467
2435351.49027653826580.2337792272433815.88001279825727.192369973
2433762.67180609824889.1631143922433487.74094491824370.135094029
#Sta/Elev= 30
       0   76.03  153.07   75.09  500.61   60.11  739.35   58.23  906.97   53.27
 1051.54   57.36 1090.62   54.44 1421.97   53.09 1562.42   46.14 1699.84   48.73
  1719.7   46.02 1965.77   45.41 2302.05   47.53  2935.4   45.25 3055.17   47.72
 3442.67   44.69 3562.44   46.87  3823.3   43.95 4003.44   35.38 4442.55   40.56
 4639.92   30.87 5976.97   31.81 6001.29   27.75 6063.36   27.75 6076.03   31.78
 6398.37   34.85 6495.48   56.87 6580.87   59.65 6721.96   75.48 6806.46   78.39
#Mann= 3 ,0,0
       0     .12       0 5976.97     .04       0 6076.03     .12       0
Bank Sta=5976.97,6076.03
XS Rating Curve= 0 ,0
Exp/Cntr(USF)=0,0
Exp/Cntr=0.3,0.1

Type RM Length L Ch R = 1 ,110004  ,806.9,806.9,806.9
XS GIS Cut Line= 6
2437244.55996009829557.6742970612436098.23762113827867.806433285
2435438.27996358826428.2392384542435159.38723206825328.130819696
 2434973.1585086824729.5384942812434599.89166701823522.315303443
#Sta/Elev= 30
       0   72.67  243.37   74.19  360.17   69.66  429.97   63.06   681.6   57.23
 1270.22   57.96 1417.98   51.13 1440.69   47.98 1733.57   43.78 2436.57   48.24
  3508.5   46.65  3732.4   42.16 3905.02   45.84 3959.84   44.86 4044.46   34.48
 4389.69   35.53    4454   30.47 5092.81  30.042 5102.83    27.2 5189.36  27.188
 5193.31   30.17  5589.9   30.09 5672.31   33.67  5892.1   30.03 5936.74   34.71
 6211.47   35.67 6283.58   41.73 6372.27   67.51 6410.65   73.58 6651.03    78.1
#Mann= 3 ,0,0
       0     .12       0 5092.81     .04       0 5193.31     .12       0
Bank Sta=5092.81,5193.31
XS Rating Curve= 0 ,0
Exp/Cntr(USF)=0,0
Exp/Cntr=0.3,0.1

Type RM Length L Ch R = 1 ,109197  ,627.6,627.6,627.6
XS GIS Cut Line= 6
2437302.31201948829283.1254347552436496.23123741827657.880528999
2435917.60417759825940.0251967872435824.48981585825288.224664669
2435877.69802256824543.3097708192435455.99423927823058.701601788
#Sta/Elev= 30
       0   75.81  258.99   70.23   383.5   62.74  573.94   57.33 1141.58   58.39
 1272.85   45.66 1701.26   42.99  2505.3   47.74 2950.87   42.91 3780.33   48.43
 3859.87   42.54 3942.73   31.51 4606.48  29.932 4624.06      27 4693.98   26.99
 4706.48  30.744 5044.05    29.9  5156.6   33.93 5241.87   29.79 5398.76   29.66
  5477.2   32.59 5900.12   31.81 6114.99   36.92 6237.77   35.91 6333.72   40.59
 6353.73   44.56 6358.89   48.87 6427.11   72.34 6471.44   80.61 6575.42   83.85
#Mann= 3 ,0,0
       0     .12       0 4606.48     .04       0 4706.48     .12       0
Bank Sta=4606.48,4706.48
XS Rating Curve= 0 ,0
Exp/Cntr(USF)=0,0
Exp/Cntr=0.3,0.1

Type RM Length L Ch R = 1 ,108570  ,740.5,740.5,740.5
XS GIS Cut Line= 3
2437667.08948707829172.4274730882436409.78008959826006.535455167
2436383.17598624822800.741001277
#Sta/Elev= 30
       0   74.27  155.12   74.09  334.51   68.49  441.18   61.02  483.46   64.49
  776.54   55.41 1224.87    58.3 1383.72   49.24  1627.3   48.38 1719.08   43.69
 2015.61   42.66 2358.03   47.15 2605.14   43.95 2876.95    48.4 3285.65   48.25
3576.025   45.033717.025   32.673825.325   29.914205.925   30.124232.555 26.8471
4261.225 26.84714265.025   29.915231.925   29.675318.125   34.485482.225   35.57
5629.825   30.785948.125    35.26446.825   34.216532.125   38.34 6612.33      58
#Mann= 3 ,0,0
       0     .12       04205.925     .04       04265.025     .12       0
Bank Sta=4205.925,4265.025
XS Rating Curve= 0 ,0
Exp/Cntr(USF)=0,0
Exp/Cntr=0.3,0.1

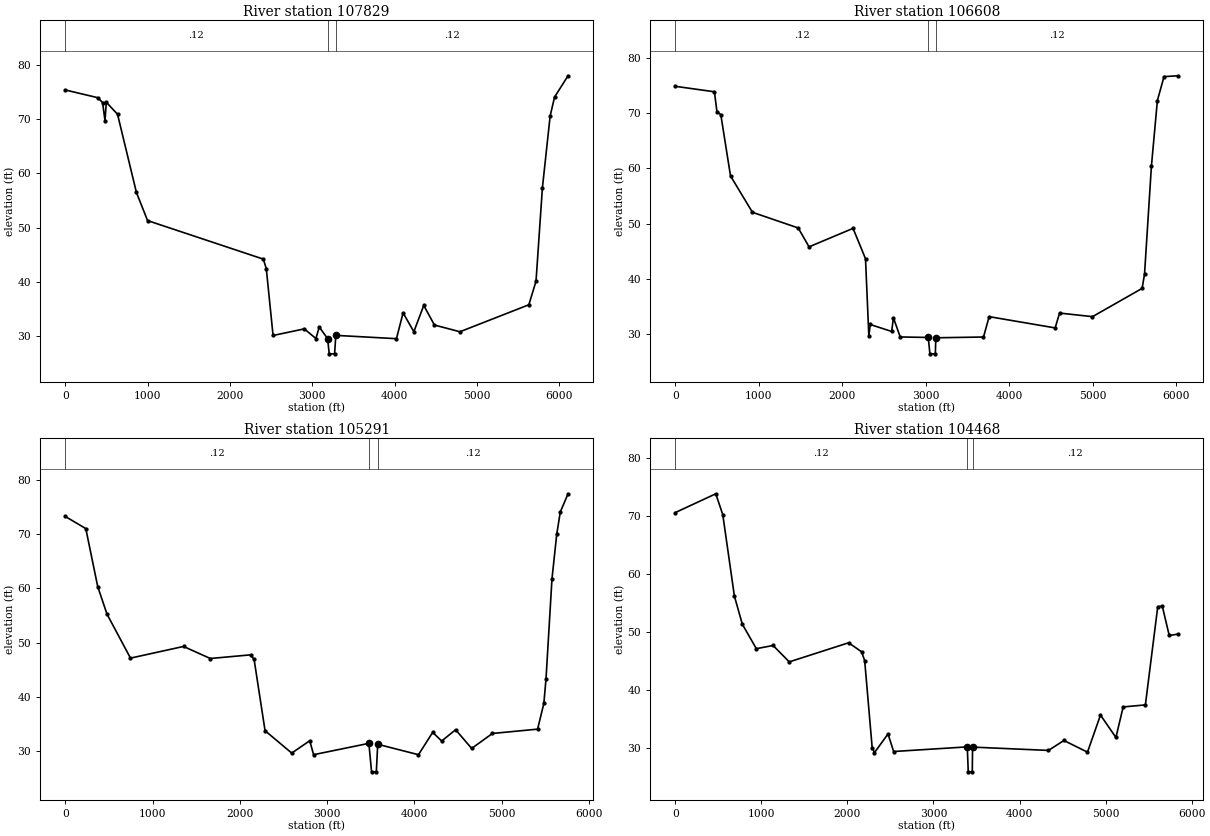
Type RM Length L Ch R = 1 ,107829  ,1220.7,1220.7,1220.7
XS GIS Cut Line= 6
2438799.50307077827886.5290338732437540.45448204826232.670333657
2437167.99703512825368.0369747242436888.65394993824011.227703783
2436976.38923923823010.8500332872436831.97988289822329.092522954
#Sta/Elev= 30
       0    75.4  393.09   73.98  453.72   73.08  482.58   69.75  499.07   73.13
  635.15   70.91  864.31   56.48  999.72   51.28 2405.93   44.16 2441.79   42.39
 2523.95   30.06 2902.79   31.28 3044.38    29.5 3084.57   31.63 3185.97  29.489
 3205.97  26.671 3271.14  26.671 3285.97  30.081 4022.47   29.47 4102.86   34.24
  4233.5   30.76 4354.09   35.61 4483.51   31.99  4793.1   30.75 5630.16   35.73
 5717.36   40.09 5794.93   57.34 5888.83   70.59 5942.49   74.09 6106.38   78.02
#Mann= 3 ,0,0
       0     .12       0 3185.97     .04       0 3285.97     .12       0
Bank Sta=3185.97,3285.97
XS Rating Curve= 0 ,0
Exp/Cntr(USF)=0,0
Exp/Cntr=0.3,0.1

Type RM Length L Ch R = 1 ,106608  ,1317.6,1317.6,1317.6
XS GIS Cut Line= 5
2439277.80066999827554.5290338732439003.68016639 825900.11904176
2437966.12013567824543.3097708192437625.28530067822766.641838121
2436938.44195263822297.469149598
#Sta/Elev= 30
       0   74.86  468.45   73.87  498.31   70.28  544.87   69.72  661.26   58.61
  923.98   52.03  1472.7   49.19  1602.4   45.77 2129.54   49.12 2278.91   43.62
 2318.94   29.61 2335.46    31.7 2592.16   30.44 2613.77    32.9 2694.78   29.44
 3030.89   29.35 3050.89  26.382 3115.87  26.382 3121.49   29.29  3692.9   29.43
 3760.68   33.12 4551.45   31.08  4604.9   33.77  4999.1   33.12 5593.96   38.24
 5622.89   40.83 5705.33   60.39 5776.85   72.28 5856.31   76.62 6025.88   76.77
#Mann= 3 ,0,0
       0     .12       0 3030.89     .04       0 3121.49     .12       0
Bank Sta=3030.89,3121.49
XS Rating Curve= 0 ,0
Exp/Cntr(USF)=0,0
Exp/Cntr=0.3,0.1

Type RM Length L Ch R = 1 ,105291  ,822.4,822.4,822.4
XS GIS Cut Line= 5
2440587.97627018 826738.104410742440067.84430046 824929.06926942
2439176.60683818824157.5502722182438644.52477114823425.937430044
 2438164.2985646821695.083468513
#Sta/Elev= 30
       0   73.33  235.54   71.08  372.09   60.35  477.91   55.27   747.6   47.11
 1355.25   49.27 1662.49   47.04 2126.04   47.72 2164.37   46.86 2289.77   33.68
 2595.46   29.54 2801.82   31.82  2846.1   29.24 3479.42   31.34 3510.35 26.0689
 3564.96 26.0689 3580.78   31.17 4047.84   29.24 4210.98   33.38 4313.41   31.77
 4473.44   33.86 4657.29    30.4 4895.63   33.17 5413.15   33.97 5484.65   38.74
 5509.64   43.33 5577.73   61.77 5632.21   70.02 5673.07   74.15 5761.99   77.52
#Mann= 3 ,0,0
       0     .12       0 3479.42     .04       0 3580.78     .12       0
Bank Sta=3479.42,3580.78
XS Rating Curve= 0 ,0
Exp/Cntr(USF)=0,0
Exp/Cntr=0.3,0.1

Type RM Length L Ch R = 1 ,104468  ,1462.6,1462.6,1462.6
XS GIS Cut Line= 5
2442208.31740435825459.9814291142440679.73867755824835.954907688
2439655.48069851823931.4153937282439655.48069851823000.271776416
2438977.07606304821231.098903522
#Sta/Elev= 30
       0    70.6  469.83   73.84  551.33   70.23  685.99   56.21  778.13   51.35
  941.14   47.12 1136.04   47.67 1323.86   44.84 2013.96   48.14 2164.48   46.58
2200.252   45.062287.452   30.042314.152   29.192471.352   32.412536.952   29.38
3392.852   30.183403.982 25.87383450.592 25.87383454.452   30.144336.252   29.57
4515.652   31.284789.752   29.274940.852   35.675120.052    31.85204.352   37.07
5462.552   37.42 5606.15   54.35 5658.86   54.47 5739.67    49.4 5843.47   49.63
#Mann= 3 ,0,0
       0     .12       03392.852     .04       03454.452     .12       0
Bank Sta=3392.852,3454.452
XS Rating Curve= 0 ,0
Exp/Cntr(USF)=0,0
Exp/Cntr=0.3,0.1