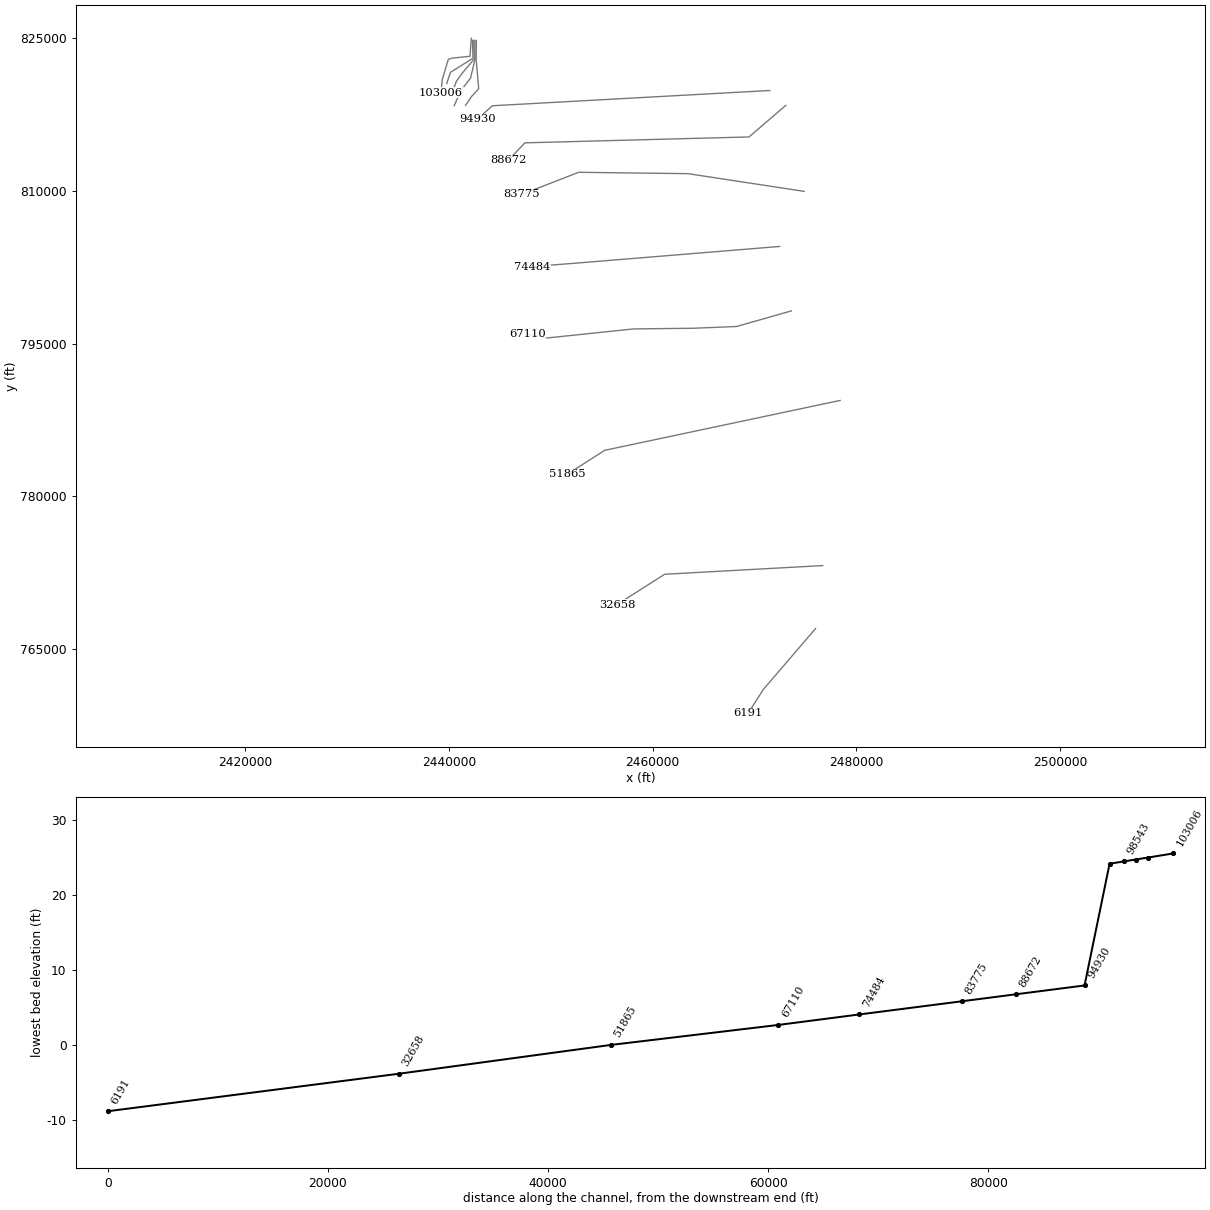
HEC-RAS study WillowCreek.prj: S-21-57 over Willow Creek

--- WillowCreek.g02 (geometry) --- (continued)

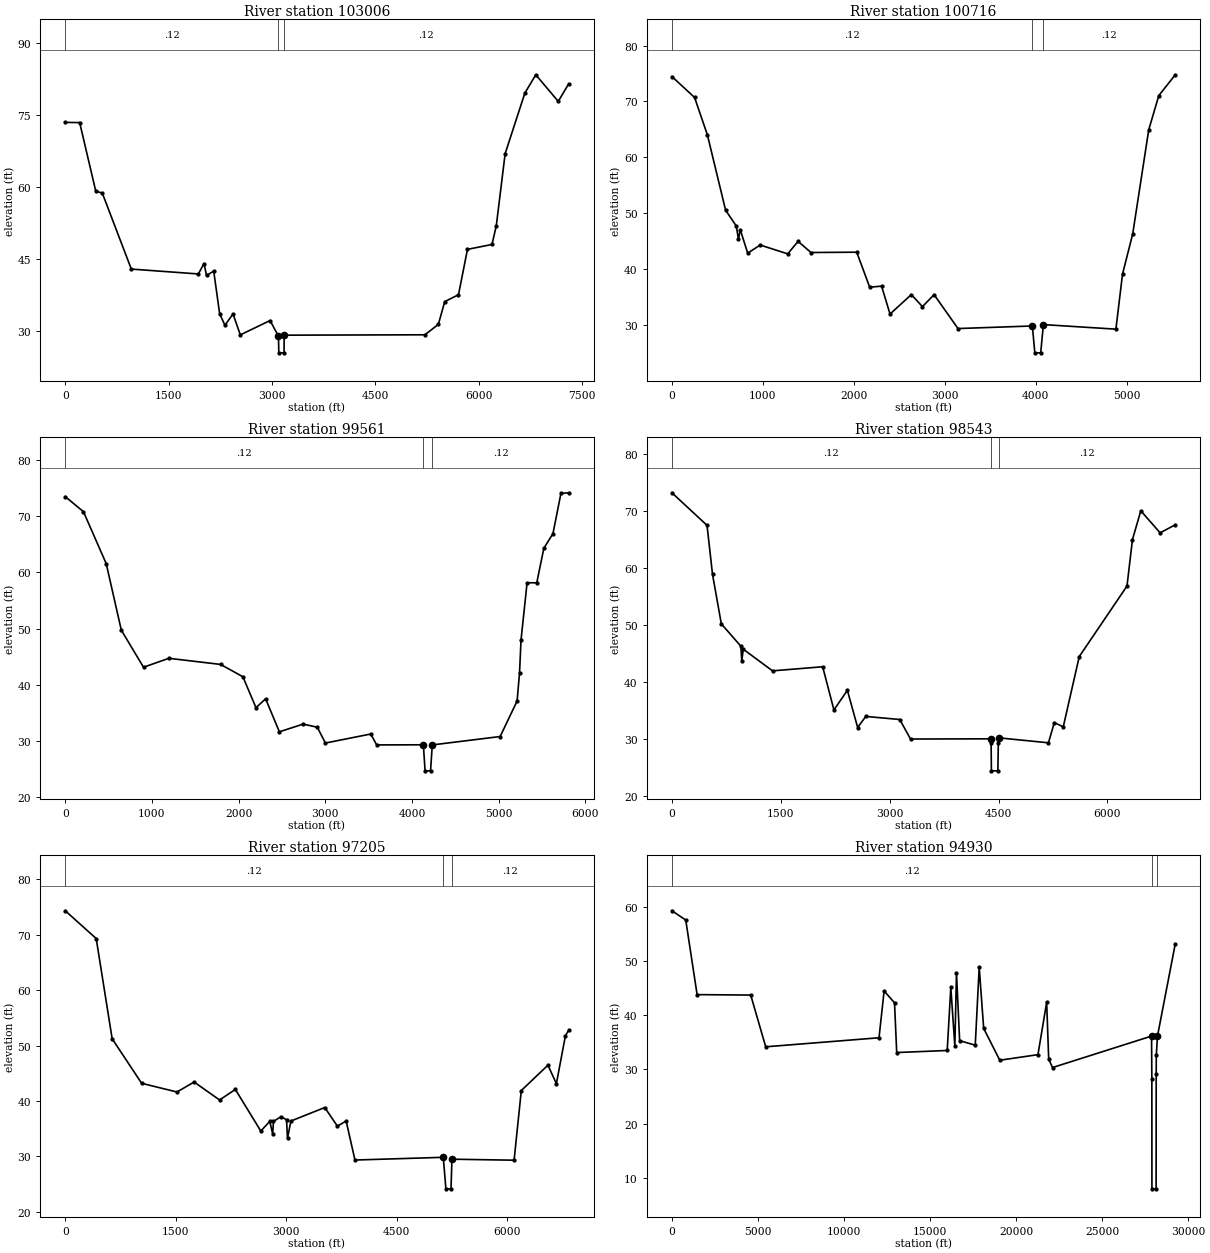
Type RM Length L Ch R = 1 ,103006  ,2289.9,2289.9,2289.9
XS GIS Cut Line= 6
2442198.99862352825004.2765817442442076.45410352823239.708706582
 2440267.3750756823053.4799831192439948.12583538822947.063569712
2439349.53350996820925.1517149772439234.68456848 819655.60278416
#Sta/Elev= 30
       0   73.44  208.92    73.4  442.42   59.16  537.79   58.73  958.75   42.94
 1931.71   41.93 2014.16   44.09 2050.44   41.632155.114   42.512240.814   33.69
2317.414   31.262435.414   33.612541.014   29.262973.014   32.243095.154   28.99
3099.934 25.52673176.364 25.5267  3177.7    29.25221.314   29.285416.314   31.45
5508.714   36.18 5708.29    37.6 5838.74   47.04 6194.74   48.06 6257.33   51.95
  6385.8   66.95  6672.4   79.55 6830.52   83.34 7156.65   77.81 7307.37   81.43
#Mann= 3 ,0,0
       0     .12       03095.154     .04       0  3177.7     .12       0
Bank Sta=3095.154,3177.7
XS Rating Curve= 0 ,0
Exp/Cntr(USF)=0,0
Exp/Cntr=0.3,0.1

Type RM Length L Ch R = 1 ,100716  ,1154.6,1154.6,1154.6
XS GIS Cut Line= 5
2442315.11098704824818.3932003712442366.98985812  823050.5669594
2440719.64483258  822015.91995242440160.95866219821670.066608827
2439788.50121527820565.996319728
#Sta/Elev= 30
       0   74.44  249.02    70.7  390.16   63.99  590.37   50.51  708.53   47.67
  731.51   45.29   751.2   47.05  833.26   42.83  971.11   44.28 1273.08    42.7
 1387.96   44.94  1529.1   42.94 2032.68      43 2175.17   36.73 2305.85   36.92
 2398.83   31.92 2633.29   35.41 2755.27   33.25 2883.12    35.4 3146.57   29.33
  3964.4   29.79 3991.14   24.98  4055.9   24.98 4085.58  30.036 4883.14   29.22
 4955.85   39.08 5067.83   46.26 5244.42   64.93 5355.22   71.04 5536.17   74.76
#Mann= 3 ,0,0
       0     .12       0  3964.4     .04       0 4085.58     .12       0
Bank Sta=3964.4,4085.58
XS Rating Curve= 0 ,0
Exp/Cntr(USF)=0,0
Exp/Cntr=0.3,0.1

Type RM Length L Ch R = 1 ,99561   ,1018.3,1018.3,1018.3
XS GIS Cut Line= 5
2442442.74986042824789.1988334722442500.70109379822989.091763759
2441344.84126135821616.8584021232440746.24893593820805.433249894
2440333.88533398819674.758857443
#Sta/Elev= 30
       0   73.47  209.98   70.78  472.59   61.54  646.56   49.72   902.6   43.13
 1194.74   44.72 1792.17   43.63 2049.05   41.44 2200.11   35.94 2311.33   37.52
 2470.05   31.65 2744.59   33.02 2907.93   32.46 3001.07   29.65 3524.55   31.26
 3592.48   29.32 4131.04   29.34 4151.04   24.71 4214.04   24.71 4234.04  29.317
 5016.94   30.81 5212.51   37.12 5240.44   42.05  5257.9   47.98 5327.75   58.15
 5439.44   58.14    5521   64.28 5626.25   66.89 5718.37   74.04 5807.06   74.15
#Mann= 3 ,0,0
       0     .12       0 4131.04     .04       0 4234.04     .12       0
Bank Sta=4131.04,4234.04
XS Rating Curve= 0 ,0
Exp/Cntr(USF)=0,0
Exp/Cntr=0.3,0.1

Type RM Length L Ch R = 1 ,98543   ,1338.1,1338.1,1338.1
XS GIS Cut Line= 5
2442557.27774676824803.7267198122442570.06519045822959.246213205
2442129.66231023821098.0783867632441185.21664124819874.289632581
2440520.11405744818384.459844882
#Sta/Elev= 30
       0   73.28   483.6   67.56  559.06   58.97  680.46   50.27  949.49   46.35
  962.61   43.73   982.3   45.82 1385.85   42.02 2076.69   42.74 2231.77   35.16
  2417.2    38.6  2558.8   32.07 2670.06   34.02 3138.69   33.48 3287.03   30.05
 4393.02   30.09 4397.22   29.42 4401.32 24.4676 4490.32 24.4676 4496.62   29.39
 4503.62   30.26 5187.32   29.39 5267.87   32.94 5391.19   32.19 5611.59   44.53
 6269.09    56.9 6344.54   65.07  6459.6   70.12 6725.39   66.25 6934.48   67.66
#Mann= 3 ,0,0
       0     .12       0 4393.02     .04       0 4503.62     .12       0
Bank Sta=4393.02,4503.62
XS Rating Curve= 0 ,0
Exp/Cntr(USF)=0,0
Exp/Cntr=0.3,0.1

Type RM Length L Ch R = 1 ,97205   ,2275.3,2275.3,2275.3
XS GIS Cut Line= 5
2442701.55978774824789.1036558162442678.10311139822975.647621227
2442927.78541078820047.2163043682442249.38077531819315.603462194
2441637.48639822818424.365999909
#Sta/Elev= 30
       0   74.34  419.79   69.33  636.34   51.24 1036.64    43.2 1515.68   41.63
 1748.64   43.43 2094.15   40.19 2308.18   42.09 2653.91   34.58 2775.74   36.33
 2815.26   34.04 2825.14   36.32 2927.21   37.17 3002.94   36.63 3016.12   33.28
 3062.21   36.39 3522.09   38.83 3693.31   35.46 3811.85    36.4 3931.52   29.35
 5130.41   29.84 5165.88   24.15 5235.16   24.15 5247.81    29.5 6091.41   29.32
 6189.28    41.9 6550.88   46.47 6665.27   43.13 6787.58   51.76 6831.48   52.75
#Mann= 3 ,0,0
       0     .12       0 5130.41     .04       0 5247.81     .12       0
Bank Sta=5130.41,5247.81
XS Rating Curve= 0 ,0
Exp/Cntr(USF)=0,0
Exp/Cntr=0.3,0.1

Type RM Length L Ch R = 1 ,94930   ,6258.5,6258.5,6258.5
XS GIS Cut Line= 3
 2471502.6864173819879.3249982832444269.29859918818381.488668286
2442805.50400396817053.861012153
#Sta/Elev= 30
       0    59.3   803.4   57.59  1463.8   43.81  4578.8   43.73  5449.5   34.17
 12034.2   35.84   12330   44.49 12934.8    42.3 13062.7   33.11 15996.9   33.49
 16206.7   45.13 16440.5   34.32 16535.8    47.8 16719.8   35.31 17626.7   34.47
 17856.7   48.85 18116.3   37.57 19052.7   31.69 21270.6   32.72 21776.6    42.4
 21894.9   31.86   22119   30.34 27871.5   36.15 27889.2    28.2 27893.6    7.93
 28137.2    7.93 28141.7   29.13 28148.2    32.6 28212.1   36.0829250.73    53.2
#Mann= 3 ,0,0
       0     .12       0 27871.5     .04       0 28212.1     .12       0
Bank Sta=27871.5,28212.1
XS Rating Curve= 0 ,0
Exp/Cntr(USF)=0,0
Exp/Cntr=0.3,0.1

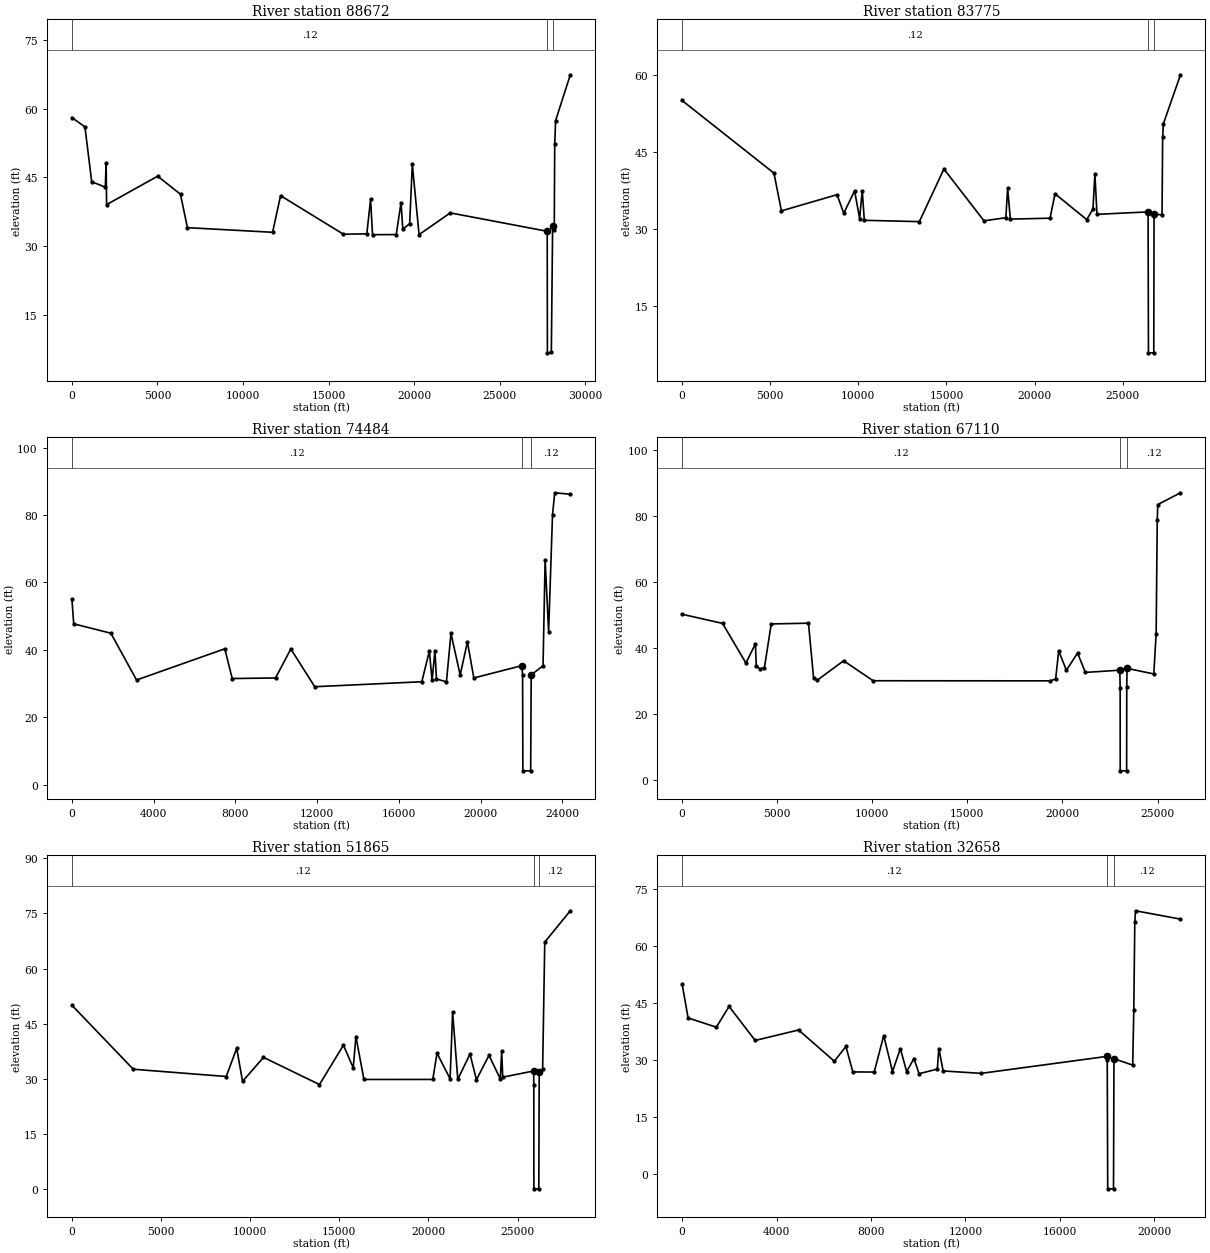
Type RM Length L Ch R = 1 ,88672   ,4896.6,4896.6,4896.6
XS GIS Cut Line= 4
2473068.60621684818415.5304030592469460.18233094815317.732538748
2447469.22166781814739.0230476132445835.21839872813036.936308981
#Sta/Elev= 30
       0   58.06   761.9   56.02  1156.5   44.07  1949.9   42.88    2001   48.18
  2026.2   39.07  5011.5   45.28    6344   41.32  6747.7   34.05 11723.2   33.04
 12189.2   41.03 15858.5   32.62 17227.1    32.7   17447   40.21 17561.8   32.52
 18946.8   32.54 19225.7   39.52 19330.2   33.68 19729.9   34.94 19885.5   47.84
 20279.3   32.54 22104.1   37.27 27765.5   33.26 27776.1    6.7528005.63    6.84
 28081.3   34.42   28176   33.51 28203.6   52.29 28255.1   57.3929113.78   67.39
#Mann= 3 ,0,0
       0     .12       0 27765.5     .04       0 28081.3     .12       0
Bank Sta=27765.5,28081.3
XS Rating Curve= 0 ,0
Exp/Cntr(USF)=0,0
Exp/Cntr=0.3,0.1

Type RM Length L Ch R = 1 ,83775   ,9290.6,9290.6,9290.6
XS GIS Cut Line= 4
2474872.81815979809973.1801794432463468.83701095811709.308652848
2452745.69055757811845.4755919382447128.80432008809666.804566489
#Sta/Elev= 30
       0      55  5212.7   40.84  5637.4   33.49  8791.3   36.64  9175.1   33.03
  9789.1    37.4 10073.9      32 10223.8   37.43   10340   31.65   13464   31.39
 14858.4   41.65 17132.2   31.55 18372.5   32.15 18474.2   37.89 18628.4   31.88
 20879.3   32.06 21164.7   36.81 22964.5   31.78 23316.4   33.86   23426    40.7
 23545.1   32.81 26444.8   33.29 26465.9    5.82 26767.8    5.82   26783   32.51
 26807.2   32.79 27236.6   32.75 27271.7   47.86 27317.5   50.5128284.01   60.01
#Mann= 3 ,0,0
       0     .12       0 26444.8     .04       0 26807.2     .12       0
Bank Sta=26444.8,26807.2
XS Rating Curve= 0 ,0
Exp/Cntr(USF)=0,0
Exp/Cntr=0.3,0.1

Type RM Length L Ch R = 1 ,74484   ,7374,7374,7374
XS GIS Cut Line= 3
2472455.85499093804560.5443505922452132.93933166802892.499346732
2448150.05636326802586.123733779
#Sta/Elev= 30
       0      55    89.2   47.69  1906.1   44.91  3163.6   31.02  7479.2   40.28
  7844.6   31.46  9964.6   31.63 10711.9   40.23 11880.5   29.03 17121.1   30.51
 17489.8   39.65 17621.5   30.93 17764.2   39.64 17837.2   31.33   18326   30.48
 18546.5   44.87 18997.5   32.51   19353   42.33 19665.6   31.63 22012.2   35.28
 22051.7   32.43 22064.8    4.07 22446.5    4.07 22472.9   32.55   23052   35.24
   23154    66.7 23325.1   45.41   23516   80.12 23624.5   86.58 24385.9   86.15
#Mann= 3 ,0,0
       0     .12       0 22012.2     .04       0 22472.9     .12       0
Bank Sta=22012.2,22472.9
XS Rating Curve= 0 ,0
Exp/Cntr(USF)=0,0
Exp/Cntr=0.3,0.1

Type RM Length L Ch R = 1 ,67110   ,15245,15245,15245
XS GIS Cut Line= 6
 2473613.2739732 798228.781682882468234.67987912796696.903618111
2464047.54650209796526.6949442482458124.28465165796458.611474702
2449681.93442803795573.5263706132447707.51381122795947.985453113
#Sta/Elev= 30
       0   50.23    2128   47.45  3356.1   35.41  3854.1   41.23  3901.9   34.39
  4099.9   33.63  4328.3      34  4687.4   47.29  6644.6   47.51  6913.8   30.82
    7101   30.17  8493.2    36.1 10046.1   30.03 19362.3      30 19641.5   30.58
 19799.8   39.09 20205.6   33.23 20792.7   38.44 21204.9   32.56 23012.9   33.24
 23032.6   27.75 23035.6    2.67   23373    2.67   23379   28.21 23395.5   33.79
 24800.3    32.1 24925.1   44.37 24982.7   78.97 25011.9   83.5426204.97   87.12
#Mann= 3 ,0,0
       0     .12       0 23012.9     .04       0 23395.5     .12       0
Bank Sta=23012.9,23395.5
XS Rating Curve= 0 ,0
Exp/Cntr(USF)=0,0
Exp/Cntr=0.3,0.1

Type RM Length L Ch R = 1 ,51865   ,19207.4,19207.4,19207.4
XS GIS Cut Line= 3
2478404.70139929789435.8600941832455289.94322033784532.729571373
 2451647.6176891782197.905512892
#Sta/Elev= 30
       0      50  3441.8   32.57  8657.1   30.59    9244   38.28  9572.2   29.26
 10746.5    35.8 13885.8    28.4 15230.3   39.12 15780.6   32.96 15930.6   41.45
 16380.9   29.78 20241.4   29.79 20479.3   36.94 21213.8   29.96 21354.7   48.12
 21644.2   29.82 22330.4   36.71 22689.5   29.72 23395.7   36.35 24029.9   29.91
 24107.9   37.55 24164.9   30.41 25900.9    32.1 25908.3   28.16 25912.2       0
 26188.9       0   26212   31.89 26403.2   32.57 26523.1   67.1927955.49   75.72
#Mann= 3 ,0,0
       0     .12       0 25900.9     .04       0   26212     .12       0
Bank Sta=25900.9,26212
XS Rating Curve= 0 ,0
Exp/Cntr(USF)=0,0
Exp/Cntr=0.3,0.1

Type RM Length L Ch R = 1 ,32658   ,26466.9,26466.9,26466.9
XS GIS Cut Line= 3
2476699.16662266 773212.654582992461183.49386702772358.580853321
2456486.08835384769369.322799482
#Sta/Elev= 30
       0      50   254.3   41.06  1450.3   38.62  1989.2   44.09  3093.2   35.14
  4933.3   37.89    6448   29.68  6938.3   33.56  7230.1   26.88  8136.9   26.84
  8537.8   36.44  8909.1   26.98  9244.3   32.97  9510.4   26.95  9819.3    30.4
 10036.1   26.41 10808.3   27.62   10874   33.01 11054.7   27.13 12668.1    26.5
 17974.4   30.94 18004.4   29.93 18024.9   -3.83 18269.9   -3.83 18289.4   30.35
 19082.7   28.66 19129.4   43.07 19172.1   66.28 19203.3    69.221107.04   67.01
#Mann= 3 ,0,0
       0     .12       0 17974.4     .04       0 18289.4     .12       0
Bank Sta=17974.4,18289.4
XS Rating Curve= 0 ,0
Exp/Cntr(USF)=0,0
Exp/Cntr=0.3,0.1

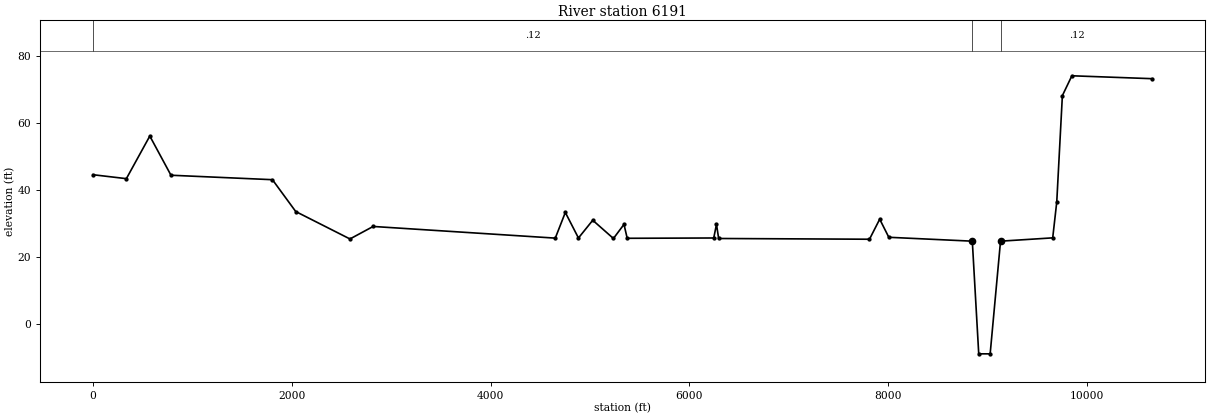
Type RM Length L Ch R = 1 ,6191    ,,,
XS GIS Cut Line= 3
2475987.43851461767020.620042894 2470862.9961366761042.103935215
2469368.36710968758693.401178627
#Sta/Elev= 30
       0    44.6     335   43.43   570.8   56.14   783.7   44.45  1804.5   43.12
    2039   33.62  2584.5   25.44  2817.8   29.17  4650.2   25.69  4751.2   33.35
  4883.3   25.73  5027.1   31.02  5235.2   25.58  5341.4   29.79  5373.8   25.64
  6244.5   25.73  6271.9   29.81  6293.9   25.58  7811.3   25.36  7914.1   31.34
  8005.8   25.94  8845.8   24.78 8910.42   -8.83 9025.35   -8.83  9129.7   24.78
  9654.7   25.77  9695.5   36.52  9751.9    68.2  9847.6   74.1210658.11   73.25
#Mann= 3 ,0,0
       0     .12       0  8845.8     .04       0  9129.7     .12       0
Bank Sta=8845.8,9129.7
XS Rating Curve= 0 ,0
Exp/Cntr(USF)=0,0
Exp/Cntr=0.3,0.1
LCMann Table=0

Chan Stop Cuts=-1
Use User Specified Reach Order=0
Composite Channel Slope=5

--- WillowCreek.g01 (geometry) ---

Geom Title=Duplicate Effective
Program Version=6.60

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
River Reach=Willow Creek    ,Reach-1
Reach XY= 30
      2389519.64       828073.95      2390493.08       827579.91
      2394378.97       828770.33      2397216.95       828578.38
      2398289.74       827746.36      2398504.35       826199.22
      2399361.73       826102.85        2401912.        823481.4
      2404242.72       822652.15      2404987.12       821385.17
      2406713.85       820827.98      2406601.76       820316.46
      2407965.83       820310.14      2409108.83        819210.6
      2410211.93       819081.65      2413131.23       821266.38
        2413420.       822664.68      2414734.94       824370.14
      2417705.38       824497.35      2418253.56       825415.54
      2420448.63       826618.31       2421834.5       826424.57
      2422600.38       827143.53      2424011.02       830917.02
      2425431.93       831511.31      2425995.36       830898.72
      2427723.21        830730.8      2429345.12       831610.39
      2429545.96       830862.02       2430902.5       831799.63

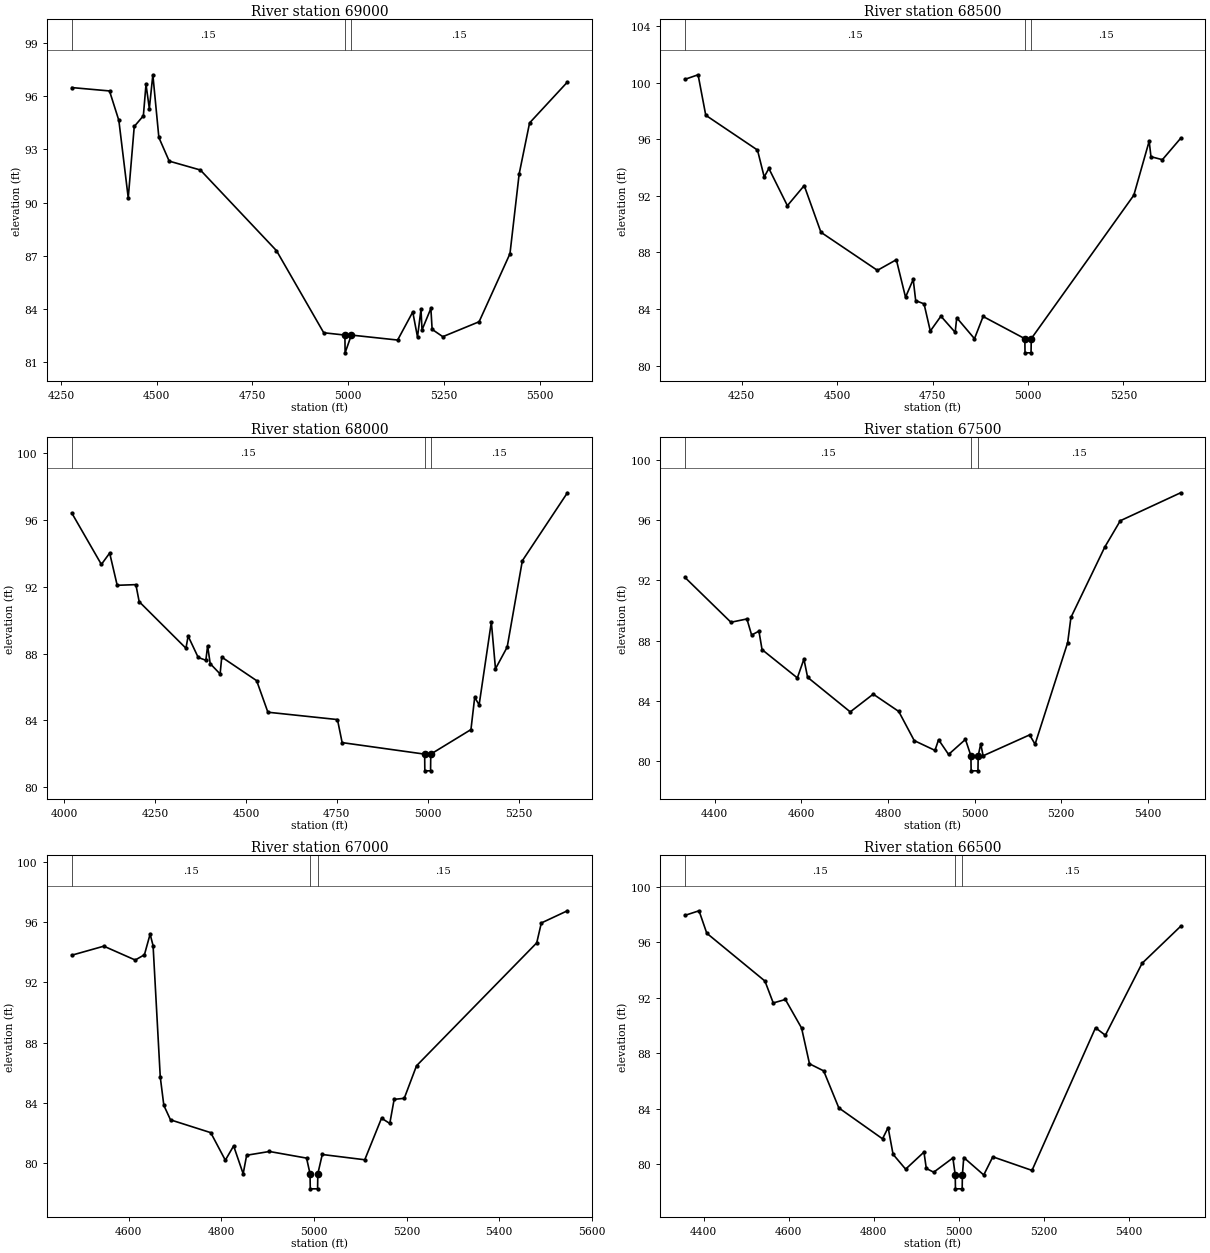
Type RM Length L Ch R = 1 ,69000   ,500,500,500
BEGIN DESCRIPTION:
Willow Creek 131.0
END DESCRIPTION:
XS GIS Cut Line= 3
      2389813.41       828778.87      2389726.32       828062.35
      2389620.07       827499.59
#Sta/Elev= 30
  4278.2   96.47  4376.8   96.28  4401.2   94.62  4425.7   90.26  4441.4   94.28
  4465.2   94.88  4472.1   96.65  4480.8   95.29    4490   97.19  4505.7   93.66
  4532.7   92.33  4614.1   91.83  4812.9   87.29  4936.3   82.67  4991.6   82.54
  4992.1   81.54  5008.4   82.54  5129.3   82.26  5168.8   83.84  5181.2   82.43
  5190.3   83.99    5193   82.83  5216.1   84.04  5219.4   82.86  5247.3   82.45
  5342.1   83.29  5422.7   87.12  5446.7   91.61  5473.9   94.48  5572.7   96.78
#Mann= 3 ,-1,0
  4278.2     .15       0  4991.6     .05       0  5008.4     .15       0
Bank Sta=4991.6,5008.4
XS Rating Curve= 0 ,0
Exp/Cntr=0.3,0.1

Type RM Length L Ch R = 1 ,68500   ,500,500,500
BEGIN DESCRIPTION:
Willow Creek 130.0
END DESCRIPTION:
XS GIS Cut Line= 3
      2390329.79       828676.68      2390076.78       827814.43
      2389979.79       827426.68
#Sta/Elev= 30
  4101.4  100.23  4135.7  100.55  4155.8   97.69  4291.3   95.23  4308.9   93.33
  4321.1   93.93  4369.6    91.3  4413.7   92.72  4457.5   89.42  4605.4   86.73
    4655   87.48  4679.1   84.83  4699.2   86.09  4705.7   84.59  4727.6   84.36
    4744   82.44  4771.8   83.49  4809.1   82.35  4813.2   83.38  4859.7    81.9
  4882.3   83.47  4991.6    81.9  4992.1    80.9  5007.9    80.9  5008.4    81.9
  5277.1   92.04  5317.3   95.86    5322   94.76  5351.9   94.55  5399.7   96.06
#Mann= 3 ,-1,0
  4101.4     .15       0  4991.6     .05       0  5008.4     .15       0
Bank Sta=4991.6,5008.4
XS Rating Curve= 0 ,0
Exp/Cntr=0.3,0.1

Type RM Length L Ch R = 1 ,68000   ,500,500,500
BEGIN DESCRIPTION:
Willow Creek 129.0
END DESCRIPTION:
XS GIS Cut Line= 3
      2390451.01       828585.52      2390384.74       827608.37
      2390429.79       827226.61
#Sta/Elev= 30
  4020.6   96.42  4102.1   93.34  4124.9   94.02  4145.6   92.09    4197   92.13
  4206.1   91.11  4334.8   88.32  4340.8   89.05  4368.5   87.77  4389.6    87.6
  4394.4   88.47  4401.5    87.4  4428.8   86.78  4433.3   87.79  4529.3   86.38
  4560.3   84.49  4751.7   84.05  4764.6   82.67  4991.6   81.98  4992.1   80.98
  5007.9   80.98  5008.4   81.98    5119   83.45  5129.3   85.38  5141.5   84.93
  5175.1   89.89  5186.5   87.09  5218.7   88.39  5260.4   93.56  5384.4   97.63
#Mann= 3 ,-1,0
  4020.6     .15       0  4991.6     .05       0  5008.4     .15       0
Bank Sta=4991.6,5008.4
XS Rating Curve= 0 ,0
Exp/Cntr=0.3,0.1

Type RM Length L Ch R = 1 ,67500   ,500,500,500
BEGIN DESCRIPTION:
Willow Creek 128.0
END DESCRIPTION:
XS GIS Cut Line= 3
      2390656.68       828453.95      2390787.38       827798.04
      2390940.53       827347.35
#Sta/Elev= 30
  4331.2    92.2  4437.3   89.22  4474.2   89.44  4485.1   88.37    4502   88.63
  4509.2    87.4  4590.7   85.52  4605.9   86.77  4614.4   85.56  4712.9   83.26
    4766   84.44  4824.9   83.29  4860.7   81.35  4908.6    80.7  4916.9   81.41
    4940   80.43    4979   81.43  4991.6   80.34  4992.1   79.34  5007.9   79.34
  5008.4   80.34  5014.3   81.13  5019.8   80.34  5127.2   81.73  5139.8   81.11
  5215.1   87.87  5222.6   89.54  5300.6   94.21  5336.6   95.97    5476   97.83
#Mann= 3 ,-1,0
  4331.2     .15       0  4991.6     .05       0  5008.4     .15       0
Bank Sta=4991.6,5008.4
XS Rating Curve= 0 ,0
Exp/Cntr=0.3,0.1

Type RM Length L Ch R = 1 ,67000   ,500,500,500
BEGIN DESCRIPTION:
Willow Creek 127.0
END DESCRIPTION:
XS GIS Cut Line= 3
      2391047.47       828490.97      2391176.79       827984.62
      2391379.77       827476.68
#Sta/Elev= 30
  4477.4   93.81  4546.6   94.41  4614.4   93.49  4634.2   93.84  4646.5   95.21
  4652.9   94.44  4668.4   85.72  4676.1   83.84  4690.5   82.88  4777.3   82.03
  4808.8    80.2  4826.7   81.15  4847.3    79.3  4854.8   80.53  4903.9   80.78
  4984.1   80.34  4991.6    79.3  4992.1    78.3  5007.9    78.3  5008.4    79.3
    5018   80.58  5109.7   80.23  5145.9   82.99  5163.7   82.64  5173.1   84.24
  5194.9   84.31  5221.4   86.47  5480.8   94.63  5490.7   95.95    5547   96.76
#Mann= 3 ,-1,0
  4477.4     .15       0  4991.6     .05       0  5008.4     .15       0
Bank Sta=4991.6,5008.4
XS Rating Curve= 0 ,0
Exp/Cntr=0.3,0.1

Type RM Length L Ch R = 1 ,66500   ,500,500,500
BEGIN DESCRIPTION:
Willow Creek 126.0
END DESCRIPTION:
XS GIS Cut Line= 3
      2391627.48        828630.8      2391584.45       827988.74
      2391475.27         827479.
#Sta/Elev= 30
  4356.5   97.94  4389.5   98.27  4407.7   96.65  4544.4    93.2  4563.9   91.62
  4592.4   91.87  4630.5   89.81  4649.1   87.23  4682.4   86.72    4718   84.05
  4820.7   81.82  4833.9   82.63  4845.5    80.7    4875   79.63  4918.1   80.86
  4923.6   79.68    4941   79.41  4986.1   80.44  4991.6   79.21  4992.1   78.21
  5007.9   78.21  5008.4   79.21  5011.6   80.47  5058.6   79.21  5079.9   80.52
    5172   79.54  5321.3   89.83  5344.4   89.29  5430.7   94.48  5521.3   97.15
#Mann= 3 ,-1,0
  4356.5     .15       0  4991.6     .05       0  5008.4     .15       0
Bank Sta=4991.6,5008.4
XS Rating Curve= 0 ,0
Exp/Cntr=0.3,0.1

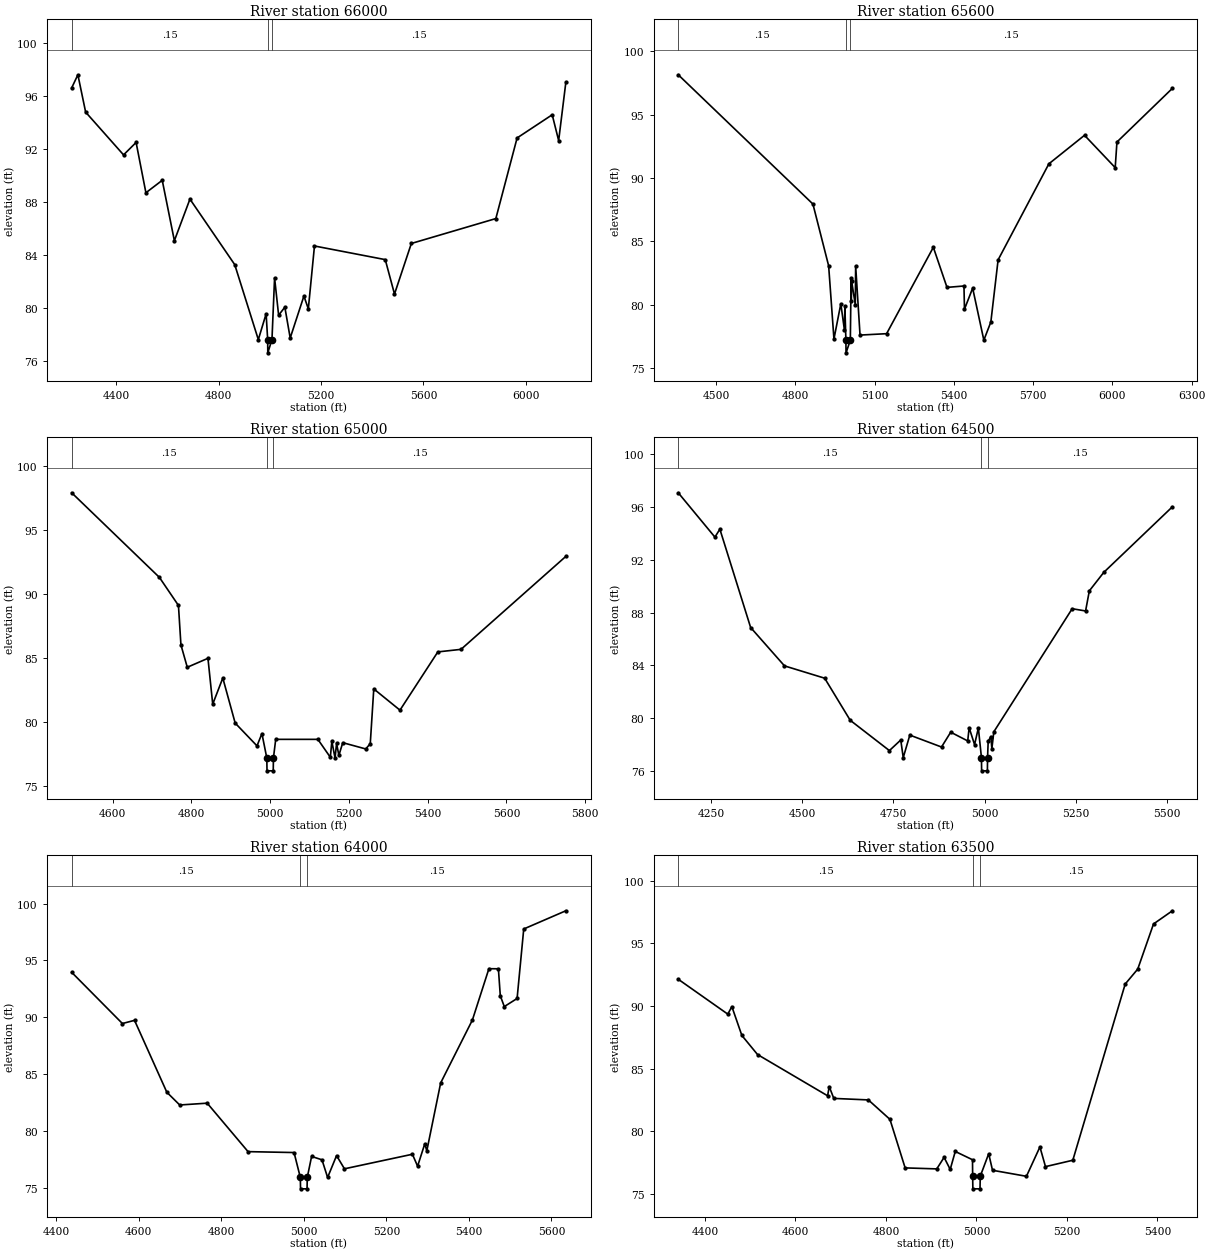
Type RM Length L Ch R = 1 ,66000   ,400,400,400
BEGIN DESCRIPTION:
Willow Creek 125.0
END DESCRIPTION:
XS GIS Cut Line= 3
      2391853.72       828750.13      2392067.92       828006.46
      2392232.17       826861.99
#Sta/Elev= 30
  4226.1   96.59  4250.3   97.58  4280.6   94.76  4428.7   91.53  4477.7   92.47
    4516   88.67  4579.8   89.61  4627.2   85.05    4688   88.19    4863   83.24
  4955.1   77.58  4985.6   79.53  4991.6   77.58  4992.1   76.58  5008.4   77.58
  5018.6   82.24  5034.4   79.42  5058.7   80.03  5079.6    77.7  5133.2   80.87
  5150.4    79.9  5174.4   84.65  5450.9   83.62    5487   81.02  5552.8   84.84
  5882.8   86.72  5965.9   92.81    6103   94.56  6128.2   92.61  6156.2      97
#Mann= 3 ,-1,0
  4226.1     .15       0  4991.6     .05       0  5008.4     .15       0
Bank Sta=4991.6,5008.4
XS Rating Curve= 0 ,0
Exp/Cntr=0.3,0.1

Type RM Length L Ch R = 1 ,65600   ,600,600,600
BEGIN DESCRIPTION:
Willow Creek 124.0
END DESCRIPTION:
XS GIS Cut Line= 3
       2392316.5        828791.2      2392406.83       828154.78
      2392859.48       827014.21
#Sta/Elev= 30
  4357.2   98.14  4866.8   87.95  4926.3   83.08  4946.4   77.31  4972.4   80.09
  4986.1   78.01  4987.7   79.89  4991.6   77.22  4992.1   76.22  5008.4   77.22
  5011.3   82.13  5011.9   80.29  5013.2   81.89  5027.2      80  5028.5   83.08
  5045.1   77.62  5145.6   77.73  5322.5   84.54  5374.2   81.38  5438.4   81.49
  5440.3   79.66  5471.3   81.32  5513.6   77.22  5540.1   78.65  5567.6   83.55
  5759.7   91.12  5894.6   93.37  6010.7   90.82  6017.3   92.84  6227.1   97.07
#Mann= 3 ,-1,0
  4357.2     .15       0  4991.6     .05       0  5008.4     .15       0
Bank Sta=4991.6,5008.4
XS Rating Curve= 0 ,0
Exp/Cntr=0.3,0.1

Type RM Length L Ch R = 1 ,65000   ,500,500,500
BEGIN DESCRIPTION:
Willow Creek 123.0
END DESCRIPTION:
XS GIS Cut Line= 3
      2392479.76       828647.33      2392730.85       828210.67
      2392884.07       827475.88
#Sta/Elev= 30
  4496.3   97.89    4719   91.28  4767.3   89.09  4773.6   86.01  4789.7   84.26
  4842.2   84.96  4854.3   81.38  4879.9   83.42  4911.3    79.9  4966.7   78.12
  4979.2   79.08  4991.6   77.17  4992.1   76.17  5007.9   76.17  5008.4   77.17
  5014.2   78.63  5121.2   78.63  5152.8   77.23  5156.7   78.47  5164.8   77.17
  5168.7   78.31  5174.5   77.38  5184.4   78.37  5242.7   77.88  5254.2   78.29
  5263.1   82.57  5329.6   80.91  5425.7   85.46  5484.6   85.66  5750.6   92.92
#Mann= 3 ,-1,0
  4496.3     .15       0  4991.6     .05       0  5008.4     .15       0
Bank Sta=4991.6,5008.4
XS Rating Curve= 0 ,0
Exp/Cntr=0.3,0.1

Type RM Length L Ch R = 1 ,64500   ,500,500,500
BEGIN DESCRIPTION:
Willow Creek 122.0
END DESCRIPTION:
XS GIS Cut Line= 3
      2392793.66        828894.1      2393126.67       828121.73
      2393394.27       827680.54
#Sta/Elev= 30
  4158.9   97.05  4259.6    93.7  4273.2    94.3  4357.7   86.87  4450.7   83.97
    4561   83.04  4631.2   79.86  4738.8   77.57    4770   78.37  4776.8   77.04
  4794.9   78.74  4881.9   77.84  4907.2   78.96  4953.9    78.3  4957.8    79.3
  4972.7   78.02  4983.1   79.28  4991.6   77.04  4992.1   76.04  5007.9   76.04
  5008.4   77.04  5010.1   78.27  5017.4   78.63  5020.2   77.71  5025.6   78.99
  5240.8   88.29  5277.6   88.12  5287.9   89.64  5327.7   91.04    5516   95.99
#Mann= 3 ,-1,0
  4158.9     .15       0  4991.6     .05       0  5008.4     .15       0
Bank Sta=4991.6,5008.4
XS Rating Curve= 0 ,0
Exp/Cntr=0.3,0.1

Type RM Length L Ch R = 1 ,64000   ,500,500,500
BEGIN DESCRIPTION:
Willow Creek 121.0
END DESCRIPTION:
XS GIS Cut Line= 3
      2393179.77        828926.7      2393394.17       828406.66
      2393745.96       827878.02
#Sta/Elev= 30
  4437.5   93.96  4560.4   89.46  4589.8   89.74  4668.1   83.42  4699.3    82.3
  4765.9   82.46  4864.9    78.2  4976.4   78.12  4991.6   75.93  4992.1   74.93
  5007.9   74.93  5008.4   75.93  5018.9   77.78  5044.1   77.48  5057.7   75.93
  5079.4   77.85  5098.5   76.69  5263.2   77.97  5275.8   76.92  5293.2   78.89
  5298.1   78.27  5331.7   84.24  5408.6   89.77  5448.6   94.28  5471.6   94.27
  5476.2    91.9  5485.9   90.95  5516.9   91.66    5533   97.77    5635   99.37
#Mann= 3 ,-1,0
  4437.5     .15       0  4991.6     .05       0  5008.4     .15       0
Bank Sta=4991.6,5008.4
XS Rating Curve= 0 ,0
Exp/Cntr=0.3,0.1

Type RM Length L Ch R = 1 ,63500   ,500,500,500
BEGIN DESCRIPTION:
Willow Creek 120.0
END DESCRIPTION:
XS GIS Cut Line= 3
      2393542.33       829103.88      2393829.77       828510.76
       2394029.8       828126.63
#Sta/Elev= 30
  4340.9   92.13  4450.4   89.35  4459.4   89.95  4481.5   87.65  4516.1   86.13
    4671   82.84  4674.6   83.57  4684.7   82.63  4761.1   82.51  4808.8   80.96
  4842.4   77.09  4912.3   77.01  4928.5   77.93    4942   76.97  4953.2    78.4
  4991.3   77.74  4991.6   76.42  4992.1   75.42  5007.9   75.42  5008.4   76.42
  5027.1   78.22  5035.5    76.9  5110.5   76.42  5140.3   78.76  5152.6   77.19
    5213    77.7  5328.8   91.75  5356.5   92.94  5391.4   96.54  5433.1   97.59
#Mann= 3 ,-1,0
  4340.9     .15       0  4991.6     .05       0  5008.4     .15       0
Bank Sta=4991.6,5008.4
XS Rating Curve= 0 ,0
Exp/Cntr=0.3,0.1

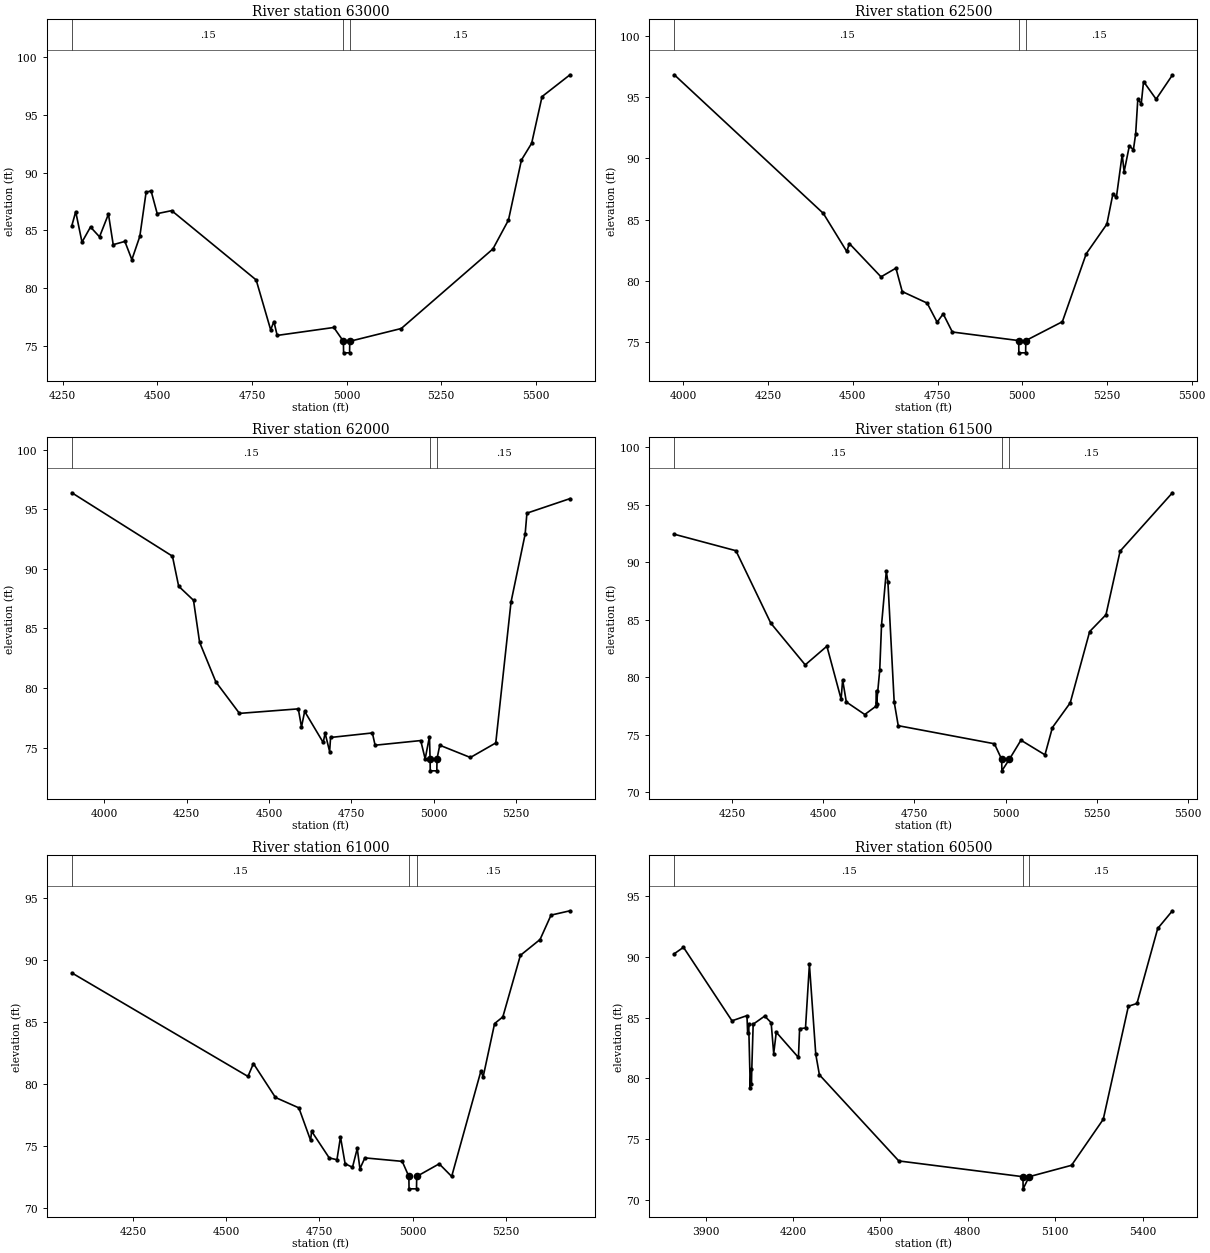
Type RM Length L Ch R = 1 ,63000   ,500,500,500
BEGIN DESCRIPTION:
Willow Creek 119.0
END DESCRIPTION:
XS GIS Cut Line= 3
      2393766.53       829247.83      2394275.64       828730.53
      2394479.79       828176.66
#Sta/Elev= 30
  4274.2   85.43  4284.3   86.63  4300.9   83.99  4323.4    85.3  4347.2   84.45
  4370.8   86.42  4383.4   83.77  4414.2   84.05  4432.7   82.47  4453.7   84.49
  4470.3   88.32  4483.5   88.43  4499.6   86.46  4537.9   86.72  4761.1   80.71
  4799.4   76.39    4808    77.1  4816.6    75.9  4966.3   76.59  4991.6   75.39
  4992.1   74.39  5007.9   74.39  5008.4   75.39  5144.5    76.5  5386.7    83.4
  5427.7    85.9    5462   91.11    5489   92.56  5516.5   96.61  5590.3    98.5
#Mann= 3 ,-1,0
  4274.2     .15       0  4991.6     .05       0  5008.4     .15       0
Bank Sta=4991.6,5008.4
XS Rating Curve= 0 ,0
Exp/Cntr=0.3,0.1

Type RM Length L Ch R = 1 ,62500   ,500,500,500
BEGIN DESCRIPTION:
Willow Creek 118.0
END DESCRIPTION:
XS GIS Cut Line= 3
      2394650.93       829746.44      2394738.27       828723.26
      2394811.36       828286.13
#Sta/Elev= 30
  3973.1   96.81  4412.9    85.5  4482.1   82.39  4489.7   83.04  4583.2   80.32
  4627.2   81.03  4645.8   79.12  4719.3   78.18  4748.8   76.62  4766.7    77.3
  4793.7   75.82  4989.5   75.12    4990   74.12    5010   74.12  5010.5   75.12
  5118.4   76.66  5188.9   82.21  5249.7   84.62  5267.5   87.08  5277.9   86.82
    5295    90.3  5300.7    88.9    5316      91  5328.1    90.7  5334.7   91.98
  5341.1   94.83  5351.2   94.44    5358   96.26  5395.1   94.82  5443.2   96.79
#Mann= 3 ,-1,0
  3973.1     .15       0  4989.5     .05       0  5010.5     .15       0
Bank Sta=4989.5,5010.5
XS Rating Curve= 0 ,0
Exp/Cntr=0.3,0.1

Type RM Length L Ch R = 1 ,62000   ,500,500,500
BEGIN DESCRIPTION:
Willow Creek 117.0
END DESCRIPTION:
XS GIS Cut Line= 3
      2394951.21       829775.24      2395234.14       828713.18
      2395374.92       828323.11
#Sta/Elev= 30
  3900.9   96.38  4206.5   91.06  4225.4   88.54  4270.5   87.36    4289   83.84
  4338.5   80.51  4410.2   77.87    4589   78.25  4598.7   76.73  4608.3   78.04
  4664.6   75.43  4670.5   76.21  4684.2   74.67  4687.1   75.85  4814.1   76.23
  4822.4    75.2  4961.1   75.59  4974.5   74.05  4987.6   75.92  4989.5   74.05
    4990   73.05    5010   73.05  5010.5   74.05  5018.9    75.2    5112   74.17
  5189.1   75.39  5235.4    87.2  5278.4   92.91  5283.8   94.67  5414.7   95.89
#Mann= 3 ,-1,0
  3900.9     .15       0  4989.5     .05       0  5010.5     .15       0
Bank Sta=4989.5,5010.5
XS Rating Curve= 0 ,0
Exp/Cntr=0.3,0.1

Type RM Length L Ch R = 1 ,61500   ,500,500,500
BEGIN DESCRIPTION:
Willow Creek 116.0
END DESCRIPTION:
XS GIS Cut Line= 3
      2395341.99       829725.88      2395672.15       828880.35
      2395839.74       828454.76
#Sta/Elev= 30
  4092.3   92.42  4261.2   90.99  4356.8    84.7  4451.1   81.08  4510.5    82.7
  4549.5    78.1  4553.6   79.78  4563.7   77.86  4614.3   76.77  4645.8   77.51
  4646.5   78.85  4646.7   77.71  4655.3   80.62  4660.2   84.53  4673.3   89.21
  4677.7   88.28  4694.9   77.86    4706    75.8  4969.6   74.23  4989.5   72.88
    4990   71.88  5010.5   72.88  5042.3   74.54  5108.1   73.27  5128.5   75.64
  5177.3   77.78  5230.6   83.97  5275.3   85.43    5314   90.95  5457.4   96.02
#Mann= 3 ,-1,0
  4092.3     .15       0  4989.5     .05       0  5010.5     .15       0
Bank Sta=4989.5,5010.5
XS Rating Curve= 0 ,0
Exp/Cntr=0.3,0.1

Type RM Length L Ch R = 1 ,61000   ,500,500,500
BEGIN DESCRIPTION:
Willow Creek 115.0
END DESCRIPTION:
XS GIS Cut Line= 3
      2396376.58        829762.9      2396103.54       828891.36
      2396029.79       828476.67
#Sta/Elev= 30
  4086.7   88.96  4558.4    80.6  4573.1   81.64  4632.1    78.9  4694.8   78.06
  4726.2   75.44    4729   76.17  4776.1   74.02  4796.8   73.87  4806.3   75.71
  4818.7   73.55  4838.5   73.26  4851.2   74.78  4858.4   73.15  4871.7   74.02
  4971.7   73.74  4989.5   72.52    4990   71.52    5010   71.52  5010.5   72.52
  5070.8   73.54  5104.2   72.52  5182.4   81.02  5188.6   80.58  5219.2   84.87
  5241.3   85.41  5288.3   90.38    5341   91.66  5370.4   93.63  5421.2   93.98
#Mann= 3 ,-1,0
  4086.7     .15       0  4989.5     .05       0  5010.5     .15       0
Bank Sta=4989.5,5010.5
XS Rating Curve= 0 ,0
Exp/Cntr=0.3,0.1

Type RM Length L Ch R = 1 ,60500   ,500,500,500
BEGIN DESCRIPTION:
Willow Creek 114.0
END DESCRIPTION:
XS GIS Cut Line= 3
      2397022.38       829729.94      2396439.73       828672.08
      2396257.25       828203.78
#Sta/Elev= 30
  3792.3   90.27  3823.8    90.8  3990.4   84.74  4041.8   85.17  4044.1   83.74
  4047.7   84.48  4053.1   79.23    4056   80.76  4056.8   79.51  4063.1   84.46
  4102.7   85.13  4124.8   84.59  4133.6   82.04  4142.4    83.8  4218.5   81.72
  4222.6   84.09  4242.8   84.15  4256.2   89.39    4278   81.99  4290.5   80.29
  4563.1   73.19  4989.5   71.89    4990   70.89  5010.5   71.89  5156.2   72.83
  5265.1   76.62  5351.4   85.94  5380.9   86.17  5452.1   92.35  5502.6   93.81
#Mann= 3 ,-1,0
  3792.3     .15       0  4989.5     .05       0  5010.5     .15       0
Bank Sta=4989.5,5010.5
XS Rating Curve= 0 ,0
Exp/Cntr=0.3,0.1