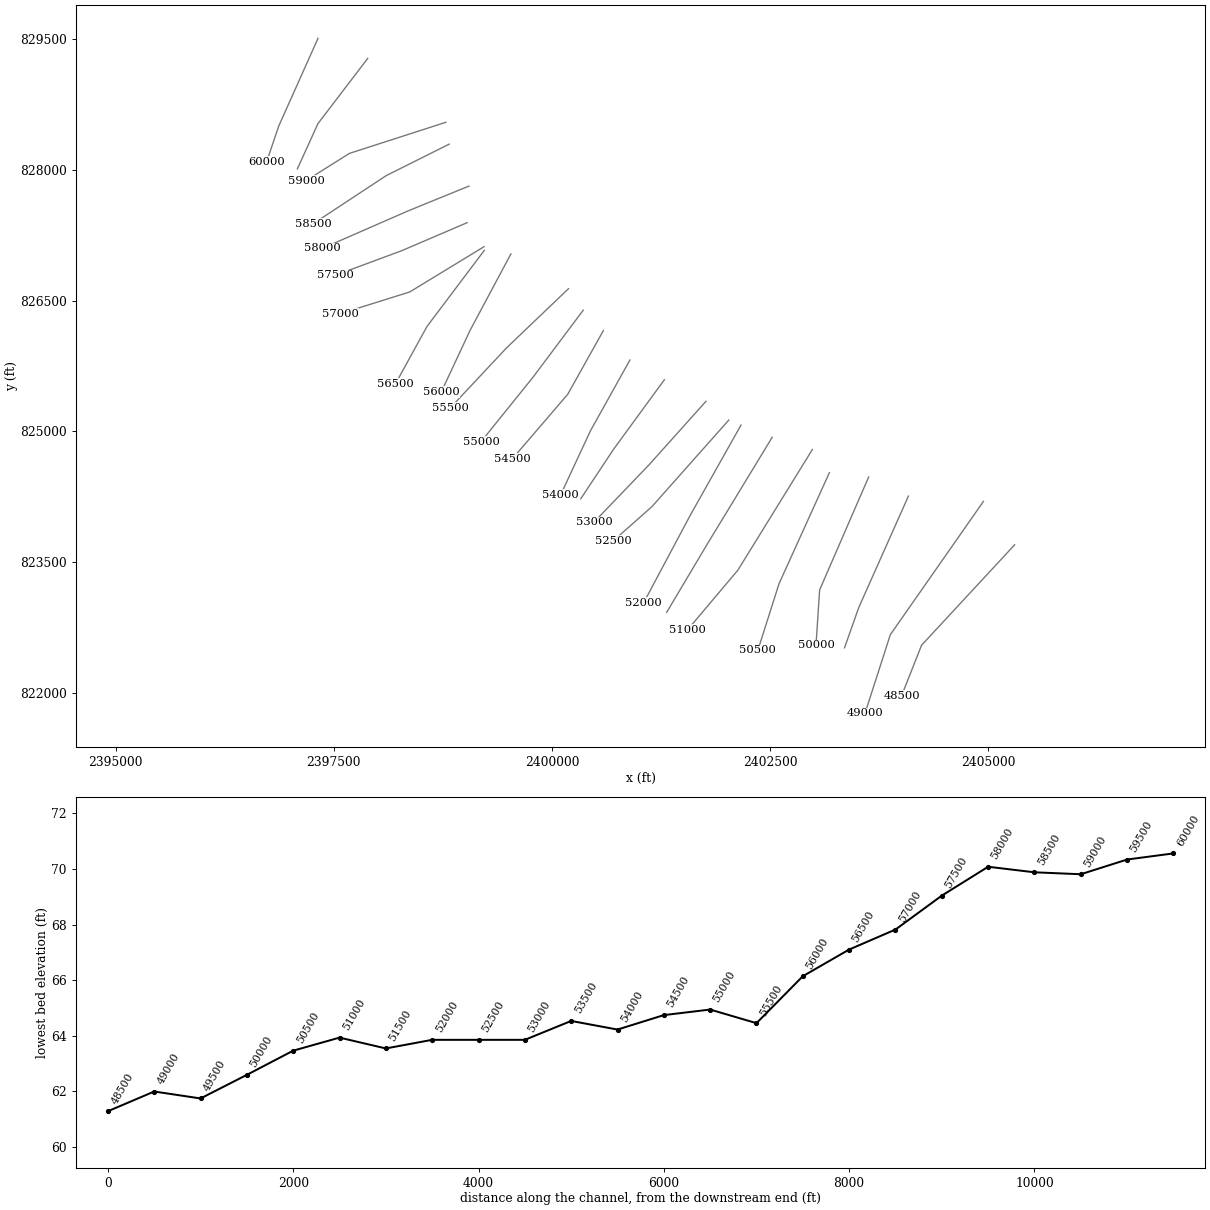
HEC-RAS study WillowCreek.prj: S-21-57 over Willow Creek

--- WillowCreek.g01 (geometry) --- (continued)

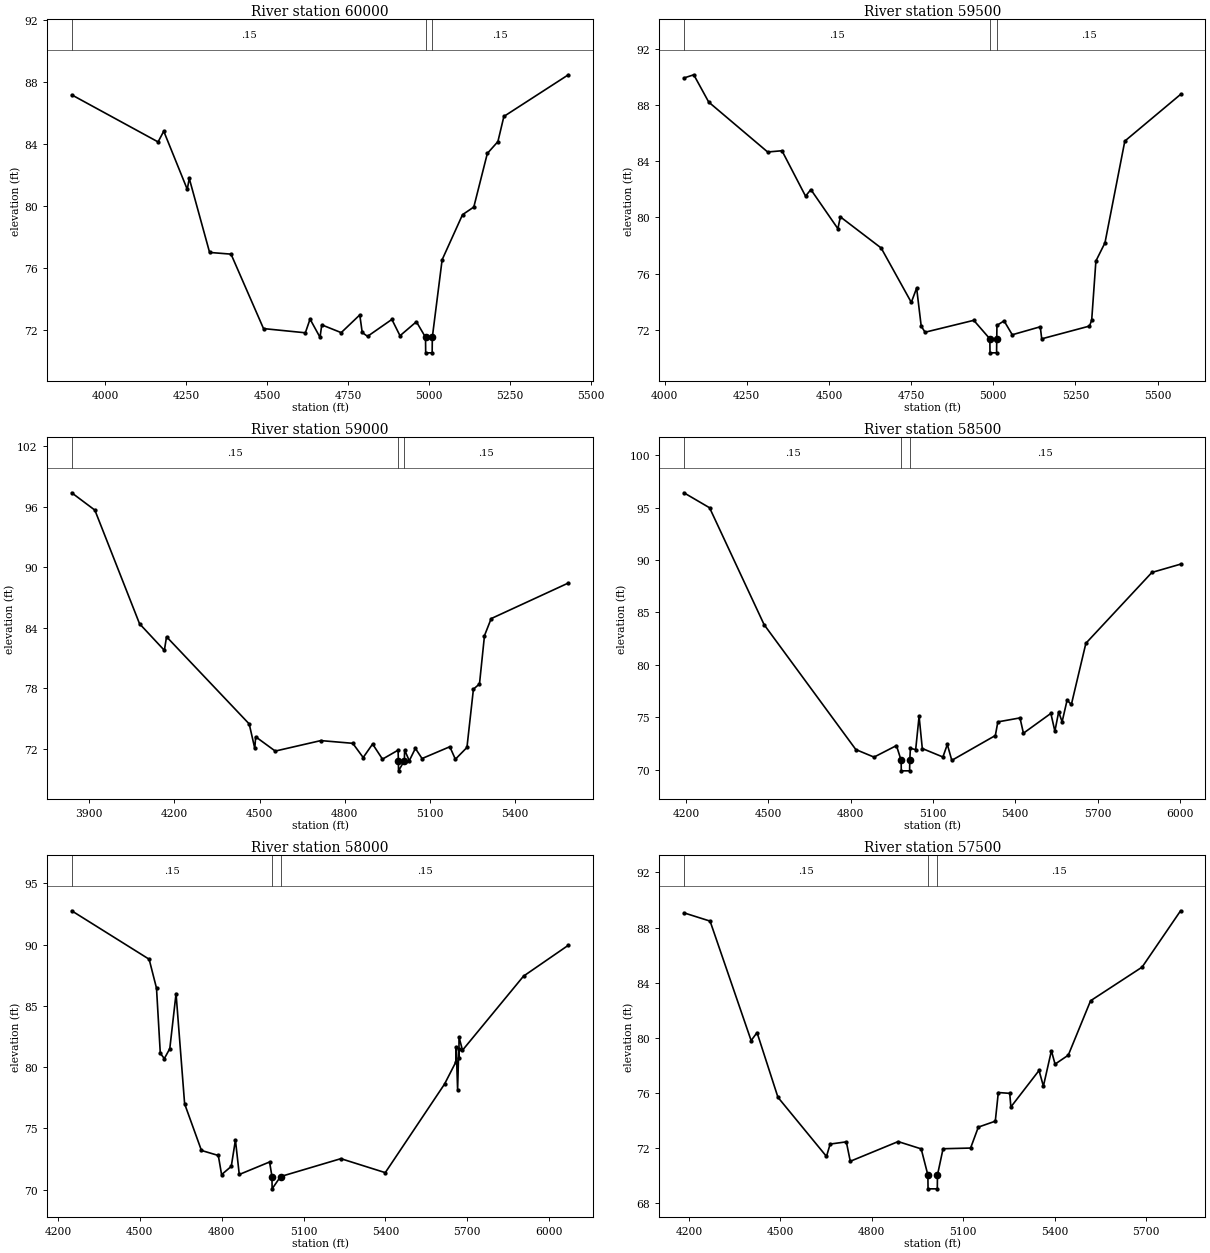
Type RM Length L Ch R = 1 ,60000   ,500,500,500
BEGIN DESCRIPTION:
Willow Creek 113.0
END DESCRIPTION:
XS GIS Cut Line= 3
      2397318.55       829507.79      2396868.22       828500.69
      2396730.33       828092.76
#Sta/Elev= 30
  3896.8   87.16  4163.6   84.13  4181.1   84.82  4253.7   81.08  4259.9   81.78
  4322.7   77.02  4388.9   76.91  4489.2   72.12  4618.4   71.85  4632.9   72.73
  4663.7   71.56  4669.1   72.36  4729.1   71.86  4786.5      73    4794   71.87
  4810.4   71.62  4885.6   72.71  4910.7   71.66  4961.3   72.56  4989.5   71.56
    4990   70.56    5010   70.56  5010.5   71.56  5040.8   76.55  5103.8   79.45
  5138.6   79.94  5180.4   83.39    5213   84.15  5231.5   85.77  5430.6   88.45
#Mann= 3 ,-1,0
  3896.8     .15       0  4989.5     .05       0  5010.5     .15       0
Bank Sta=4989.5,5010.5
XS Rating Curve= 0 ,0
Exp/Cntr=0.3,0.1

Type RM Length L Ch R = 1 ,59500   ,500,500,500
BEGIN DESCRIPTION:
Willow Creek 112.0
END DESCRIPTION:
XS GIS Cut Line= 3
       2397888.3       829277.47      2397317.59       828529.16
      2397082.02       828010.45
#Sta/Elev= 30
  4058.9   89.95  4088.9   90.18  4134.4   88.23  4313.7   84.67  4357.2   84.76
  4428.9   81.52  4445.1   81.99  4527.2    79.2  4534.9   80.04  4658.9   77.82
  4750.6   73.94  4766.8   74.96  4780.7   72.25  4792.4   71.81  4940.6   72.66
  4989.5   71.34    4990   70.34    5010   70.34  5010.5   71.34  5011.1    72.3
  5032.8   72.62  5057.7   71.63  5142.9    72.2  5147.3   71.34  5292.6   72.25
  5299.3   72.67  5312.1   76.89  5339.7   78.19  5400.1   85.45  5569.7   88.78
#Mann= 3 ,-1,0
  4058.9     .15       0  4989.5     .05       0  5010.5     .15       0
Bank Sta=4989.5,5010.5
XS Rating Curve= 0 ,0
Exp/Cntr=0.3,0.1

Type RM Length L Ch R = 1 ,59000   ,500,500,500
BEGIN DESCRIPTION:
Willow Creek 111.0
END DESCRIPTION:
XS GIS Cut Line= 3
      2398785.02       828545.24      2397678.99        828188.3
      2397180.75       827874.74
#Sta/Elev= 30
  3837.8   97.39  3919.5   95.67    4077    84.4  4164.5   81.76  4172.2   83.11
  4463.6   74.46  4483.3   72.03  4486.3   73.19  4555.4   71.77  4716.1   72.81
  4828.7   72.54  4865.4   71.13  4898.6   72.47  4933.4   70.97  4988.4   71.86
  4989.5   70.81    4990   69.81  5010.5   70.81  5011.5   71.88  5027.9   70.81
  5049.4   72.04  5072.9   71.03  5170.8    72.2  5190.4   70.96  5231.2   72.13
    5254   77.91  5275.4   78.43    5293   83.22  5316.6   84.91  5588.7   88.44
#Mann= 3 ,-1,0
  3837.8     .15       0  4989.5     .05       0  5010.5     .15       0
Bank Sta=4989.5,5010.5
XS Rating Curve= 0 ,0
Exp/Cntr=0.3,0.1

Type RM Length L Ch R = 1 ,58500   ,500,500,500
BEGIN DESCRIPTION:
Willow Creek 110.0
END DESCRIPTION:
XS GIS Cut Line= 3
      2398822.06       828294.32      2398100.09       827933.08
      2397263.08       827381.15
#Sta/Elev= 30
  4192.7   96.41  4286.2   94.98  4484.9   83.83  4819.2   71.91  4885.5   71.19
  4967.2   72.29  4984.3   70.88  4984.8   69.88  5015.2   69.88  5015.7   70.88
    5018   72.02  5037.3   71.91  5049.7   75.09  5061.4   72.01  5136.5    71.2
  5152.6    72.4  5168.9   70.88  5327.6   73.25  5336.7   74.55  5417.4   74.93
  5429.9   73.47  5529.9   75.36  5544.5   73.66  5558.3    75.5  5570.9   74.56
    5589   76.62  5604.6   76.21  5657.5   82.05  5898.1   88.81  6002.6    89.6
#Mann= 3 ,-1,0
  4192.7     .15       0  4984.3     .05       0  5015.7     .15       0
Bank Sta=4984.3,5015.7
XS Rating Curve= 0 ,0
Exp/Cntr=0.3,0.1

Type RM Length L Ch R = 1 ,58000   ,500,500,500
BEGIN DESCRIPTION:
Willow Creek 109.0
END DESCRIPTION:
XS GIS Cut Line= 3
      2399048.35       827813.05      2398354.47       827529.98
      2397374.06       827101.38
#Sta/Elev= 30
  4250.6   92.75  4534.3    88.8  4561.3   86.44  4575.2   81.13    4590    80.7
    4610   81.51  4632.9      86  4664.3   77.01  4725.9   73.21  4787.7    72.8
  4799.7   71.24  4835.2   71.91  4850.4   74.06  4864.5   71.25  4975.5   72.27
  4984.3   71.08  4984.8   70.08  5015.7   71.08  5236.7   72.54  5399.3    71.4
  5616.4   78.62  5658.1   80.43  5659.1   81.66  5664.3   78.17  5668.5   81.46
  5669.3   80.74  5669.4   82.46  5682.2   81.38  5905.7   87.42    6070   89.94
#Mann= 3 ,-1,0
  4250.6     .15       0  4984.3     .05       0  5015.7     .15       0
Bank Sta=4984.3,5015.7
XS Rating Curve= 0 ,0
Exp/Cntr=0.3,0.1

Type RM Length L Ch R = 1 ,57500   ,500,500,500
BEGIN DESCRIPTION:
Willow Creek 108.0
END DESCRIPTION:
XS GIS Cut Line= 3
      2399027.75       827393.46       2398277.1       827071.71
      2397513.97       826788.77
#Sta/Elev= 30
  4183.3   89.07  4269.2   88.47    4404    79.8  4423.4   80.38  4492.1   75.68
  4651.4   71.39  4663.4   72.29  4716.5   72.45  4729.5   71.04  4886.6   72.47
  4962.3   71.94  4984.3   70.04  4984.8   69.04  5015.2   69.04  5015.7   70.04
  5034.1   71.95  5124.5      72  5149.9   73.52  5205.6   73.95  5215.5   76.03
    5253   75.97  5256.7   74.98  5349.2   77.63  5363.5   76.49  5389.8   79.06
  5401.8   78.09  5445.2   78.74  5518.4   82.69  5687.5   85.13  5813.9   89.22
#Mann= 3 ,-1,0
  4183.3     .15       0  4984.3     .05       0  5015.7     .15       0
Bank Sta=4984.3,5015.7
XS Rating Curve= 0 ,0
Exp/Cntr=0.3,0.1

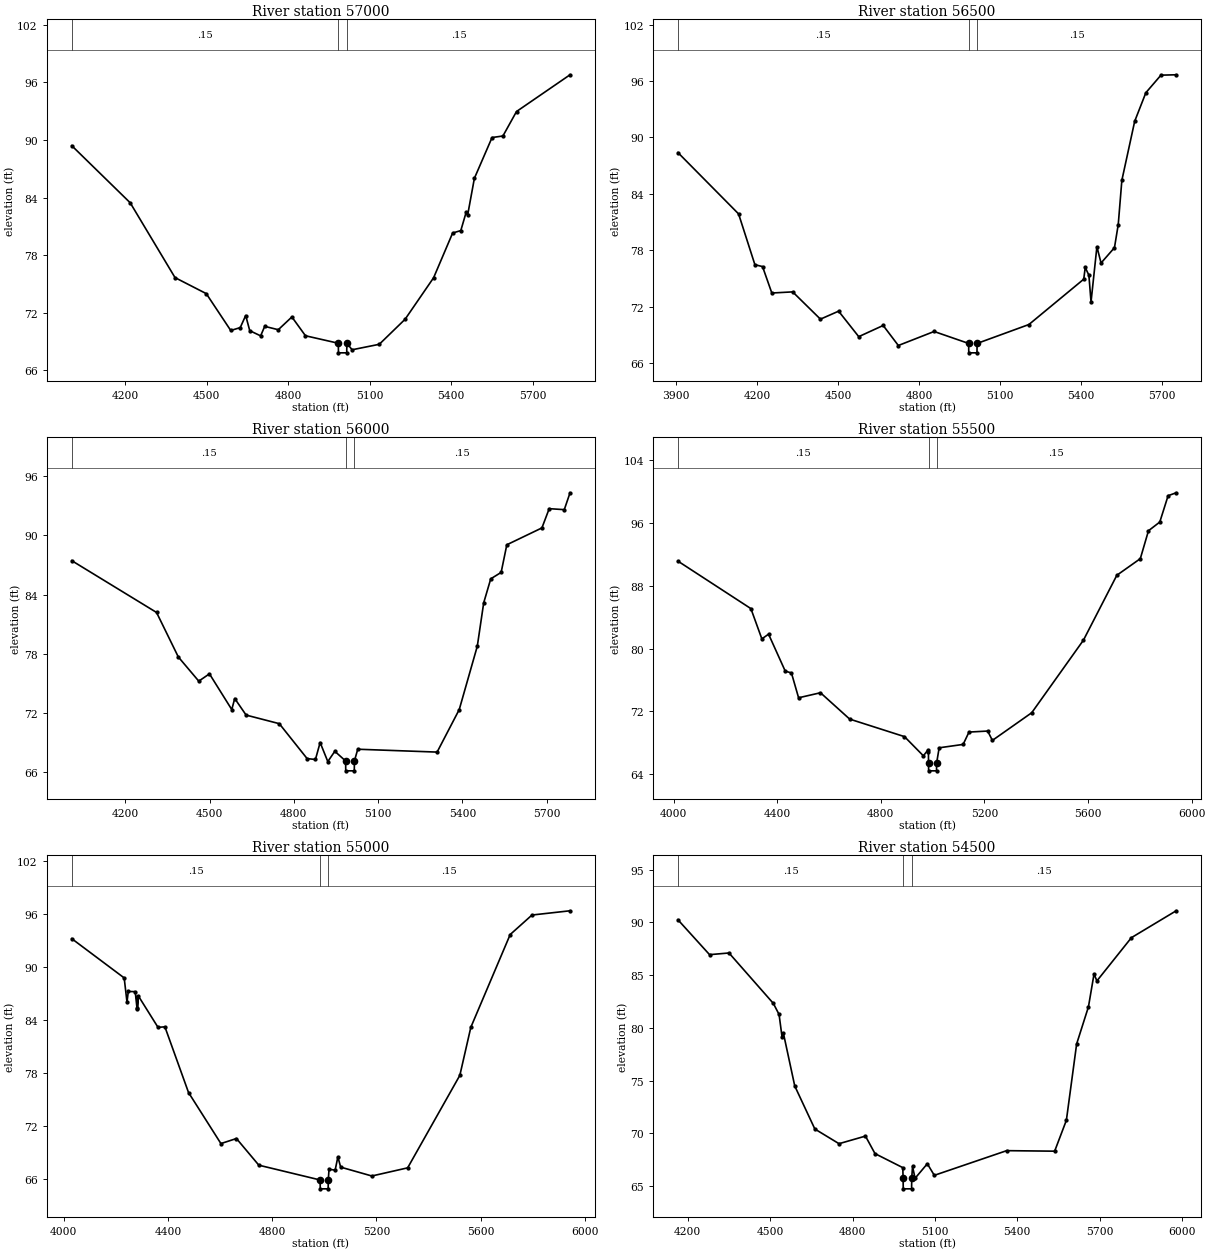
Type RM Length L Ch R = 1 ,57000   ,500,500,500
BEGIN DESCRIPTION:
Willow Creek 107.0
END DESCRIPTION:
XS GIS Cut Line= 3
      2399221.05       827117.83       2398370.2       826598.94
      2397571.51        826348.6
#Sta/Elev= 30
  4003.4   89.41  4218.4   83.46  4383.4   75.66  4498.4   73.99  4588.4   70.15
  4623.4   70.45  4643.4   71.71  4658.4   70.13  4698.4   69.59  4713.4   70.58
  4763.4   70.23  4813.4   71.56  4863.4    69.6  4984.3   68.82  4984.8   67.82
  5015.2   67.82  5015.7   68.82    5035   68.14    5135   68.71    5230   71.32
    5335   75.65    5405   80.31    5435   80.56    5455    82.5    5460   82.15
    5485   86.01    5550   90.26    5590   90.42    5640   92.97    5837    96.8
#Mann= 3 ,-1,0
  4003.4     .15       0  4984.3     .05       0  5015.7     .15       0
Bank Sta=4984.3,5015.7
XS Rating Curve= 0 ,0
Exp/Cntr=0.3,0.1

Type RM Length L Ch R = 1 ,56500   ,500,500,500
BEGIN DESCRIPTION:
Willow Creek 106.0
END DESCRIPTION:
XS GIS Cut Line= 3
      2399225.16       827076.68      2398567.68       826203.04
      2398205.01       825542.33
#Sta/Elev= 30
  3906.6   88.39  4131.5   81.87    4192   76.47  4220.3   76.27  4254.7   73.46
    4332   73.58  4434.9   70.68  4502.3   71.53  4576.9   68.82  4667.5   70.01
  4723.7   67.88  4856.3   69.37  4984.3    68.1  4984.8    67.1  5015.2    67.1
  5015.7    68.1  5207.7   70.11    5411   74.93  5416.5   76.18  5430.1   75.35
    5438   72.51  5459.8   78.38  5475.2   76.65  5524.9   78.28  5538.9   80.74
  5552.3   85.44  5599.9   91.72  5641.2   94.75  5697.2   96.62  5753.7   96.66
#Mann= 3 ,-1,0
  3906.6     .15       0  4984.3     .05       0  5015.7     .15       0
Bank Sta=4984.3,5015.7
XS Rating Curve= 0 ,0
Exp/Cntr=0.3,0.1

Type RM Length L Ch R = 1 ,56000   ,500,500,500
BEGIN DESCRIPTION:
Willow Creek 105.0
END DESCRIPTION:
XS GIS Cut Line= 3
      2399529.61       827035.61      2399063.06       826161.64
      2398731.55       825451.84
#Sta/Elev= 30
  4009.3   87.44  4311.2   82.19  4388.7   77.68  4461.5   75.23  4499.5   75.97
    4579   72.35  4589.5   73.47  4630.1   71.79  4748.2   70.92  4847.3   67.38
  4876.9   67.29  4893.6   69.01  4920.9   67.08  4945.9   68.12  4984.3   67.14
  4984.8   66.14  5015.2   66.14  5015.7   67.14  5027.5   68.33  5310.1   68.04
  5388.9   72.35  5453.2   78.77    5476   83.17  5501.1    85.6  5538.1   86.25
  5558.3   89.05  5683.3   90.76  5709.2   92.71  5762.9   92.61  5783.4   94.32
#Mann= 3 ,-1,0
  4009.3     .15       0  4984.3     .05       0  5015.7     .15       0
Bank Sta=4984.3,5015.7
XS Rating Curve= 0 ,0
Exp/Cntr=0.3,0.1

Type RM Length L Ch R = 1 ,55500   ,500,500,500
BEGIN DESCRIPTION:
Willow Creek 104.0
END DESCRIPTION:
XS GIS Cut Line= 3
      2400189.81       826636.56      2399479.34       825957.21
      2398836.46       825270.87
#Sta/Elev= 30
    4017   91.12  4298.7   85.08    4341   81.23  4366.9   81.83  4431.3   77.13
  4455.2    76.9  4482.8   73.74  4567.3   74.38    4680   71.03  4891.6    68.8
  4964.5   66.36  4981.6   67.08  4984.1   66.85  4984.3   65.45  4984.8   64.45
  5015.2   64.45  5015.7   65.45  5025.4   67.38    5118   67.81  5140.6   69.38
  5212.7   69.51  5230.9   68.32  5382.8   71.84  5582.4   81.07  5711.3   89.32
  5801.9   91.43  5833.4   94.98  5877.1   96.09  5909.2   99.44  5940.4   99.81
#Mann= 3 ,-1,0
    4017     .15       0  4984.3     .05       0  5015.7     .15       0
Bank Sta=4984.3,5015.7
XS Rating Curve= 0 ,0
Exp/Cntr=0.3,0.1

Type RM Length L Ch R = 1 ,55000   ,500,500,500
BEGIN DESCRIPTION:
Willow Creek 103.0
END DESCRIPTION:
XS GIS Cut Line= 3
      2400358.46       826389.74      2399777.83       825614.58
      2399186.11       824880.08
#Sta/Elev= 30
  4031.5   93.18  4232.6   88.75  4243.4   86.02  4248.3   87.22    4275    87.2
  4282.3   85.19  4283.2   86.57  4283.4   85.34  4286.9   86.72  4362.4   83.17
  4388.8   83.23  4479.5   75.81  4603.7   70.05  4663.3   70.62  4749.2   67.61
  4984.3   65.94  4984.8   64.94  5015.2   64.94  5015.7   65.94  5018.5   67.15
    5042   67.05  5052.5   68.55  5063.2   67.39  5182.8   66.39  5320.2   67.31
  5520.4   77.75  5562.5   83.17  5713.6   93.65  5797.2   95.85  5943.2   96.33
#Mann= 3 ,-1,0
  4031.5     .15       0  4984.3     .05       0  5015.7     .15       0
Bank Sta=4984.3,5015.7
XS Rating Curve= 0 ,0
Exp/Cntr=0.3,0.1

Type RM Length L Ch R = 1 ,54500   ,500,500,500
BEGIN DESCRIPTION:
Willow Creek 102.0
END DESCRIPTION:
XS GIS Cut Line= 3
      2400588.85       826155.31      2400181.18       825425.67
      2399544.01       824682.66
#Sta/Elev= 30
  4164.2   90.25  4279.4   86.94  4350.2    87.1  4511.7   82.32  4532.6   81.27
  4543.2   79.18  4548.2   79.51  4589.7   74.49  4662.9   70.41  4750.9   69.02
  4847.2   69.74  4881.9   68.08  4983.1   66.75  4984.3   65.74  4984.8   64.74
  5015.2   64.74  5015.7   65.74  5018.6   66.86  5027.9   65.74  5072.5   67.12
  5097.9   66.02  5361.5   68.36  5536.2   68.31  5578.9   71.24  5616.3   78.48
  5659.3      82  5679.6   85.11    5690   84.45  5815.7   88.55  5978.8    91.1
#Mann= 3 ,-1,0
  4164.2     .15       0  4984.3     .05       0  5015.7     .15       0
Bank Sta=4984.3,5015.7
XS Rating Curve= 0 ,0
Exp/Cntr=0.3,0.1

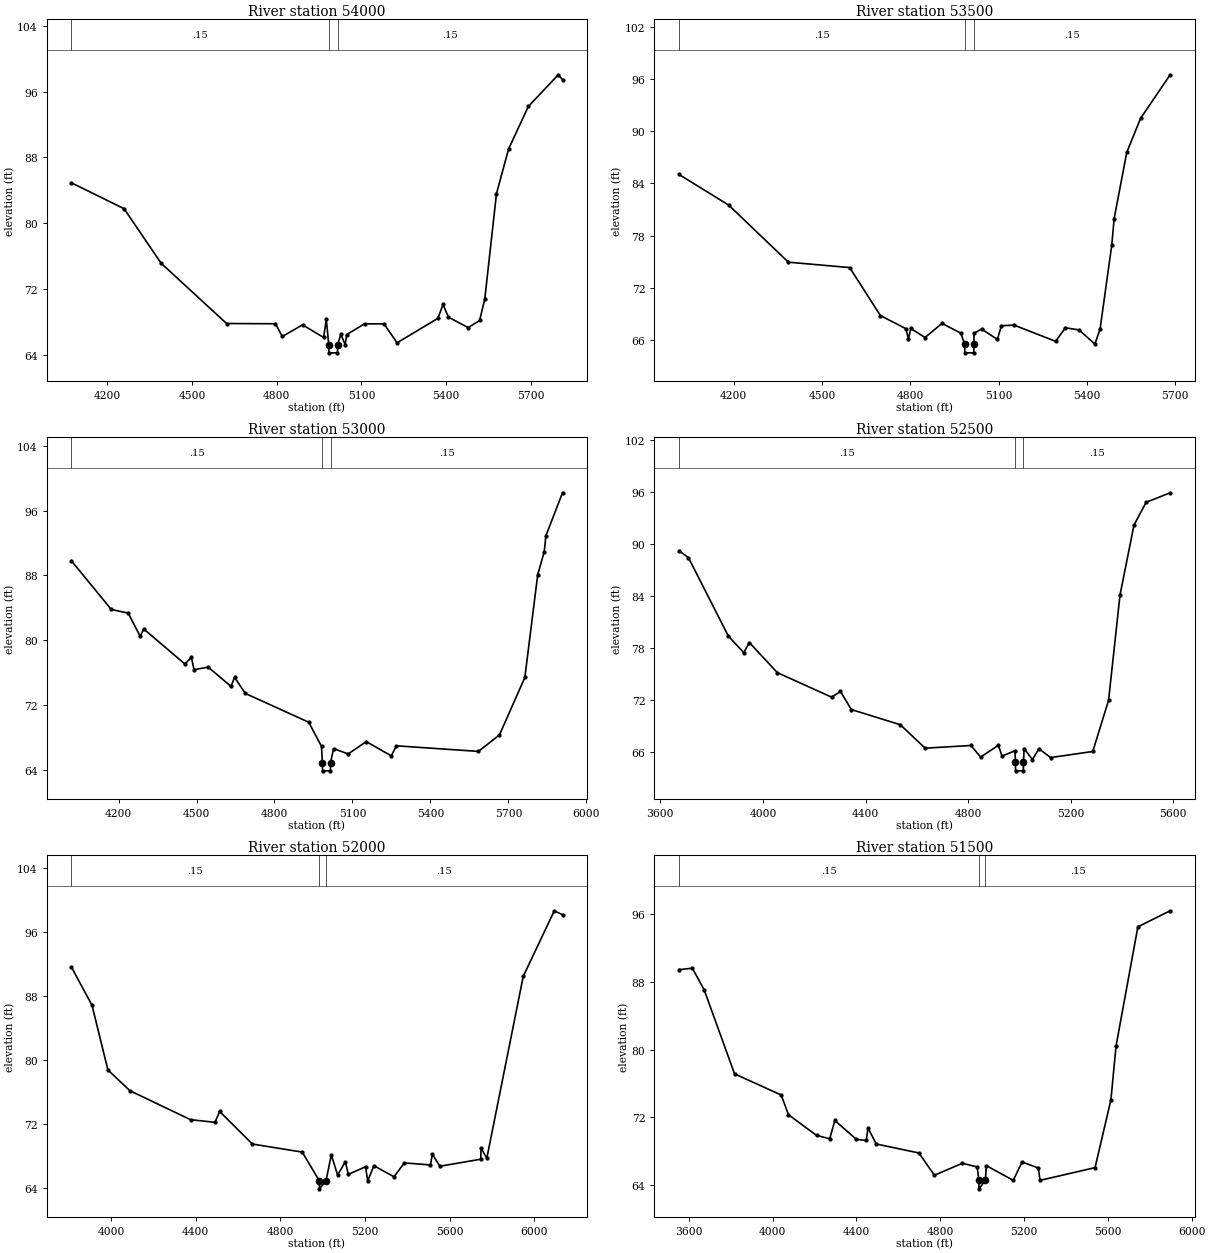
Type RM Length L Ch R = 1 ,54000   ,500,500,500
BEGIN DESCRIPTION:
Willow Creek 101.0
END DESCRIPTION:
XS GIS Cut Line= 3
      2400893.23       825817.97      2400441.98       825007.76
      2400099.31       824271.27
#Sta/Elev= 30
  4072.6   84.92    4259   81.77  4390.9   75.11  4622.3   67.79  4795.4   67.76
  4819.9   66.21  4891.3   67.63  4966.1   66.09  4975.5    68.3  4984.3   65.22
  4984.8   64.22  5015.2   64.22  5015.7   65.22  5027.1   66.47  5042.4   65.22
  5047.9   66.45  5110.9   67.75  5179.9   67.75  5226.4   65.44  5371.2   68.43
  5389.1   70.12  5407.8   68.58    5478   67.29  5518.7   68.16    5537   70.78
  5578.4    83.6  5621.4   89.04  5691.2   94.21  5797.2   98.07  5812.3   97.48
#Mann= 3 ,-1,0
  4072.6     .15       0  4984.3     .05       0  5015.7     .15       0
Bank Sta=4984.3,5015.7
XS Rating Curve= 0 ,0
Exp/Cntr=0.3,0.1

Type RM Length L Ch R = 1 ,53500   ,500,500,500
BEGIN DESCRIPTION:
Willow Creek 100.0
END DESCRIPTION:
XS GIS Cut Line= 3
      2401288.12       825591.71      2400706.76       824795.34
      2400329.79       824226.63
#Sta/Elev= 30
    4014   85.03  4182.7   81.51  4385.4   74.95  4593.7   74.33  4697.9   68.82
  4784.3   67.31  4793.3   66.15  4801.5   67.33  4849.5   66.29  4907.2   67.91
  4971.1    66.8  4984.3   65.53  4984.8   64.53  5015.2   64.53  5015.7   65.53
  5016.1   66.78  5041.6   67.26  5095.3   66.08  5109.2   67.64    5152   67.72
  5293.3   65.85  5326.3   67.41  5373.2   67.16  5426.6   65.53  5444.3   67.27
  5484.1   76.94  5492.1   79.97    5535   87.58    5582   91.49  5682.3   96.49
#Mann= 3 ,-1,0
    4014     .15       0  4984.3     .05       0  5015.7     .15       0
Bank Sta=4984.3,5015.7
XS Rating Curve= 0 ,0
Exp/Cntr=0.3,0.1

Type RM Length L Ch R = 1 ,53000   ,500,500,500
BEGIN DESCRIPTION:
Willow Creek 99.0
END DESCRIPTION:
XS GIS Cut Line= 3
      2401765.33       825344.95      2401110.62       824613.98
      2400481.86       823958.63
#Sta/Elev= 30
  4018.7   89.79  4172.1   83.78  4237.2   83.33  4283.2   80.48  4297.3   81.36
  4455.1   77.05  4480.3   77.85  4490.6   76.34  4544.9   76.66  4632.7   74.28
  4646.8   75.39  4687.8   73.41    4932   69.85    4981   66.86  4984.3   64.85
  4984.8   63.85  5015.2   63.85  5015.7   64.85  5027.3   66.59  5083.7   65.94
  5153.3   67.46  5249.3    65.7  5269.1   66.94  5584.7   66.25  5665.5   68.28
  5763.3   75.38  5812.9   88.09    5838   90.93  5844.2   92.87  5908.2   98.19
#Mann= 3 ,-1,0
  4018.7     .15       0  4984.3     .05       0  5015.7     .15       0
Bank Sta=4984.3,5015.7
XS Rating Curve= 0 ,0
Exp/Cntr=0.3,0.1

Type RM Length L Ch R = 1 ,52500   ,500,500,500
BEGIN DESCRIPTION:
Willow Creek 98.0
END DESCRIPTION:
XS GIS Cut Line= 3
      2402026.54        825129.4       2401145.9       824136.73
      2400706.08       823747.22
#Sta/Elev= 30
    3673   89.19  3709.7    88.4  3865.3   79.36  3925.3   77.46  3947.2   78.62
  4056.1   75.16  4268.1   72.33  4302.4   72.99  4344.6   70.91  4535.7   69.16
  4632.5   66.46  4811.2   66.77  4848.6   65.43  4917.9   66.79  4932.1   65.55
  4982.6   66.16  4984.3   64.85  4984.8   63.85  5015.2   63.85  5015.7   64.85
  5018.2   66.42  5050.4   65.15    5076   66.39  5121.7   65.38  5285.9   66.08
  5347.5   71.98  5392.1   84.11  5446.6   92.16  5493.9   94.77  5587.5   95.87
#Mann= 3 ,-1,0
    3673     .15       0  4984.3     .05       0  5015.7     .15       0
Bank Sta=4984.3,5015.7
XS Rating Curve= 0 ,0
Exp/Cntr=0.3,0.1

Type RM Length L Ch R = 1 ,52000   ,500,500,500
BEGIN DESCRIPTION:
Willow Creek 97.0
END DESCRIPTION:
XS GIS Cut Line= 3
      2402166.35       825071.73      2401584.29       824036.32
       2401051.6       823035.56
#Sta/Elev= 30
  3812.2   91.62  3909.5   86.84  3984.7   78.74  4088.7   76.14  4375.3   72.51
    4491   72.18  4512.9   73.54  4667.6   69.46  4903.4   68.45  4984.3   64.85
  4984.8   63.85  5015.7   64.85  5040.8   68.11  5070.5   65.59  5107.1   67.23
  5121.4   65.66  5202.5   66.62  5212.8   64.85  5242.2   66.74  5337.3   65.36
  5386.2    67.1  5509.6   66.84  5518.2   68.18  5554.3   66.68  5747.1   67.56
  5748.7   68.98  5775.8   67.67  5948.1   90.46  6094.9   98.67  6133.7   98.18
#Mann= 3 ,-1,0
  3812.2     .15       0  4984.3     .05       0  5015.7     .15       0
Bank Sta=4984.3,5015.7
XS Rating Curve= 0 ,0
Exp/Cntr=0.3,0.1

Type RM Length L Ch R = 1 ,51500   ,500,500,500
BEGIN DESCRIPTION:
Willow Creek 96.0
END DESCRIPTION:
XS GIS Cut Line= 3
      2402524.26       824931.93      2401773.37       823695.82
      2401314.87       822924.51
#Sta/Elev= 30
  3553.7   89.45  3617.4   89.62  3673.6   87.06  3818.7   77.13  4041.4   74.63
  4075.9    72.3  4209.7   69.86  4272.8   69.46    4297   71.62    4400   69.39
  4447.3   69.26  4455.2   70.73  4494.9   68.84  4698.2   67.78  4772.3   65.15
  4905.6   66.56  4976.7   66.13  4984.3   64.54  4984.8   63.54  5015.7   64.54
  5019.9   66.29  5148.5   64.54  5190.5   66.72  5268.7      66  5276.1   64.54
    5539   66.05  5614.5   74.04  5639.3   80.45  5743.3   94.51  5897.3   96.41
#Mann= 3 ,-1,0
  3553.7     .15       0  4984.3     .05       0  5015.7     .15       0
Bank Sta=4984.3,5015.7
XS Rating Curve= 0 ,0
Exp/Cntr=0.3,0.1

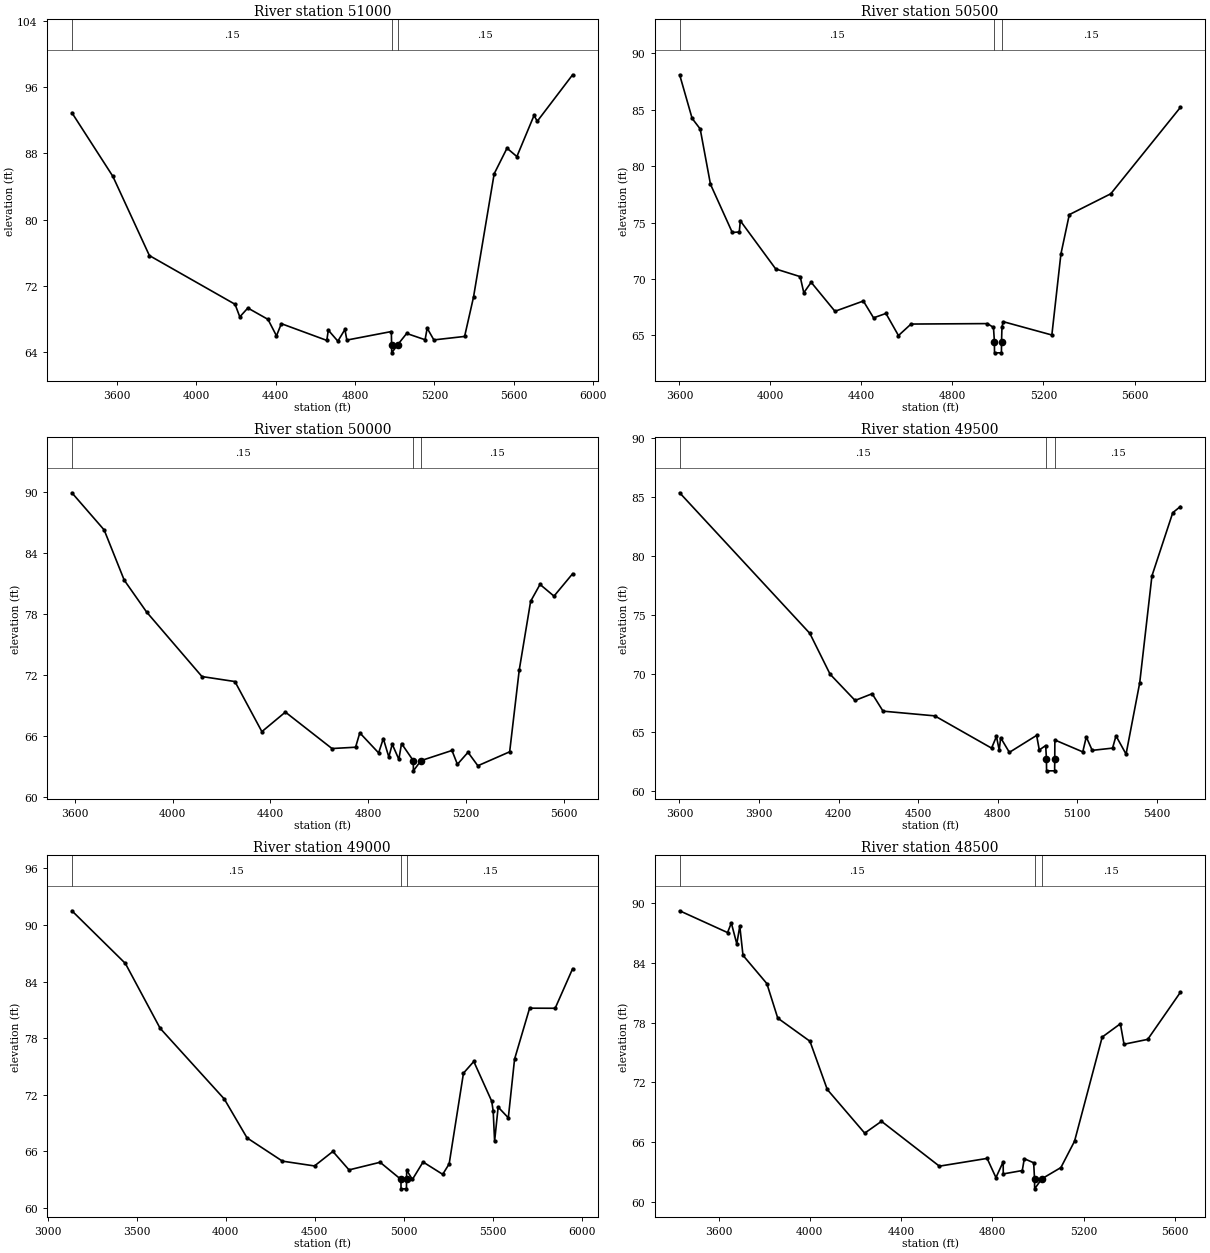
Type RM Length L Ch R = 1 ,51000   ,500,500,500
BEGIN DESCRIPTION:
Willow Creek 95.0
END DESCRIPTION:
XS GIS Cut Line= 3
      2402984.95       824792.03      2402131.01       823408.21
      2401553.45       822722.94
#Sta/Elev= 30
  3373.9   92.91  3580.3   85.23  3764.3   75.67  4195.8   69.79  4219.7   68.27
  4260.2   69.34  4361.6   67.97  4404.5   65.98    4429   67.45    4658   65.43
  4665.5   66.67  4713.6   65.34  4749.2   66.75  4758.9   65.47  4983.1    66.5
  4984.3   64.93  4984.8   63.93  5015.7   64.93  5060.2   66.27  5153.1   65.51
  5163.5   66.91  5197.2   65.49  5352.1   65.91  5396.9   70.65    5501   85.54
  5565.7   88.63  5615.4   87.62  5701.8   92.58  5718.1   91.88  5896.2   97.49
#Mann= 3 ,-1,0
  3373.9     .15       0  4984.3     .05       0  5015.7     .15       0
Bank Sta=4984.3,5015.7
XS Rating Curve= 0 ,0
Exp/Cntr=0.3,0.1

Type RM Length L Ch R = 1 ,50500   ,500,500,500
BEGIN DESCRIPTION:
Willow Creek 94.0
END DESCRIPTION:
XS GIS Cut Line= 3
       2403179.8       824526.63      2402602.43       823252.43
      2402359.71       822488.47
#Sta/Elev= 30
  3601.1   88.09  3655.9   84.23  3691.4   83.29  3736.6   78.39  3832.5   74.12
  3863.2   74.17  3867.7   75.16  4023.3   70.89  4130.8   70.21  4146.7   68.78
    4179   69.71  4283.7   67.14  4408.4   68.05  4453.3   66.56  4507.7   66.95
  4562.7   64.99  4617.9   66.01  4953.7   66.05  4980.3   65.71  4984.3   64.46
  4984.8   63.46  5015.2   63.46  5015.7   64.46  5017.6   65.77  5023.2   66.22
  5236.8   65.04  5276.6   72.21  5313.4    75.7  5495.8   77.55  5801.6    85.2
#Mann= 3 ,-1,0
  3601.1     .15       0  4984.3     .05       0  5015.7     .15       0
Bank Sta=4984.3,5015.7
XS Rating Curve= 0 ,0
Exp/Cntr=0.3,0.1

Type RM Length L Ch R = 1 ,50000   ,500,500,500
BEGIN DESCRIPTION:
Willow Creek 93.0
END DESCRIPTION:
XS GIS Cut Line= 3
       2403629.8       824476.62      2403067.75       823180.87
       2403026.1       822546.03
#Sta/Elev= 30
  3587.6    89.9  3719.6   86.25  3801.7   81.32  3893.2   78.19  4119.8   71.85
  4254.6   71.36  4364.9   66.44    4461   68.36  4651.7   64.78  4748.2   64.91
  4765.5   66.32  4842.5   64.35  4861.7   65.76  4884.2   63.95  4898.2    65.2
  4925.3   63.72  4936.2   65.27  4984.3   63.59  4984.8   62.59  5015.7   63.59
  5142.6   64.59  5164.8   63.23  5208.2   64.41  5248.5   63.09  5378.6   64.46
  5417.9   72.51  5464.4   79.24  5502.8    80.9    5560   79.75  5636.2   81.95
#Mann= 3 ,-1,0
  3587.6     .15       0  4984.3     .05       0  5015.7     .15       0
Bank Sta=4984.3,5015.7
XS Rating Curve= 0 ,0
Exp/Cntr=0.3,0.1

Type RM Length L Ch R = 1 ,49500   ,500,500,500
BEGIN DESCRIPTION:
Willow Creek 92.0
END DESCRIPTION:
XS GIS Cut Line= 3
      2404085.35       824257.32      2403516.13       822978.92
      2403353.12       822517.25
#Sta/Elev= 30
  3600.6   85.36  4091.6   73.42  4168.1   69.95  4262.4   67.72  4326.8   68.29
  4367.9   66.81    4563   66.41  4777.3   63.67  4795.7   64.66  4806.2    63.5
  4811.6   64.55  4844.5   63.31  4947.3   64.75  4957.4   63.51  4981.5   63.89
  4984.3   62.74  4984.8   61.74  5015.2   61.74  5015.7   62.74  5016.1   64.36
  5121.4   63.35  5134.6   64.62    5157   63.48  5233.8   63.67  5246.7   64.71
  5284.7   63.16  5336.2   69.22  5382.3    78.3  5460.9   83.67  5489.6   84.19
#Mann= 3 ,-1,0
  3600.6     .15       0  4984.3     .05       0  5015.7     .15       0
Bank Sta=4984.3,5015.7
XS Rating Curve= 0 ,0
Exp/Cntr=0.3,0.1

Type RM Length L Ch R = 1 ,49000   ,500,500,500
BEGIN DESCRIPTION:
Willow Creek 91.0
END DESCRIPTION:
XS GIS Cut Line= 3
      2404945.08       824196.42      2403878.18       822668.19
       2403587.6        821765.3
#Sta/Elev= 30
  3136.2   91.51  3436.5   85.92  3631.6   79.04    3992   71.53  4119.9    67.4
  4318.7   64.93  4498.8   64.42  4602.1   65.96  4692.7      64  4867.2   64.81
  4984.3   62.99  4984.8   61.99  5015.2   61.99  5015.7   62.99  5016.5   63.96
  5048.7   62.99  5108.5   64.84  5218.8   63.53  5255.1   64.64  5335.4   74.27
  5393.4   75.51  5494.2   71.29  5502.4   70.23  5510.3   67.05  5530.2   70.67
  5587.3   69.53  5622.4   75.76  5706.9   81.17  5850.4   81.16  5948.5   85.36
#Mann= 3 ,-1,0
  3136.2     .15       0  4984.3     .05       0  5015.7     .15       0
Bank Sta=4984.3,5015.7
XS Rating Curve= 0 ,0
Exp/Cntr=0.3,0.1

Type RM Length L Ch R = 1 ,48500   ,500,500,500
BEGIN DESCRIPTION:
Willow Creek 90.0
END DESCRIPTION:
XS GIS Cut Line= 3
      2405302.93       823698.66       2404235.8       822546.66
      2404007.19       821966.91
#Sta/Elev= 30
  3429.7   89.24  3639.5   87.05  3656.1   88.01  3680.1   85.91  3693.2    87.7
  3707.2   84.76  3811.7   81.92  3859.4   78.45  4000.5   76.12  4076.4   71.27
  4240.4   66.88  4313.9   68.07  4567.4   63.56  4776.6   64.34  4815.3   62.41
    4847      64  4847.3   62.78  4930.6   63.12  4939.5   64.31  4980.5    63.9
  4984.3   62.28  4984.8   61.28  5015.7   62.28  5099.8   63.42  5159.6   66.07
  5280.7   76.54  5360.3   77.88  5376.3   75.82  5480.1   76.31  5623.2   81.04
#Mann= 3 ,-1,0
  3429.7     .15       0  4984.3     .05       0  5015.7     .15       0
Bank Sta=4984.3,5015.7
XS Rating Curve= 0 ,0
Exp/Cntr=0.3,0.1