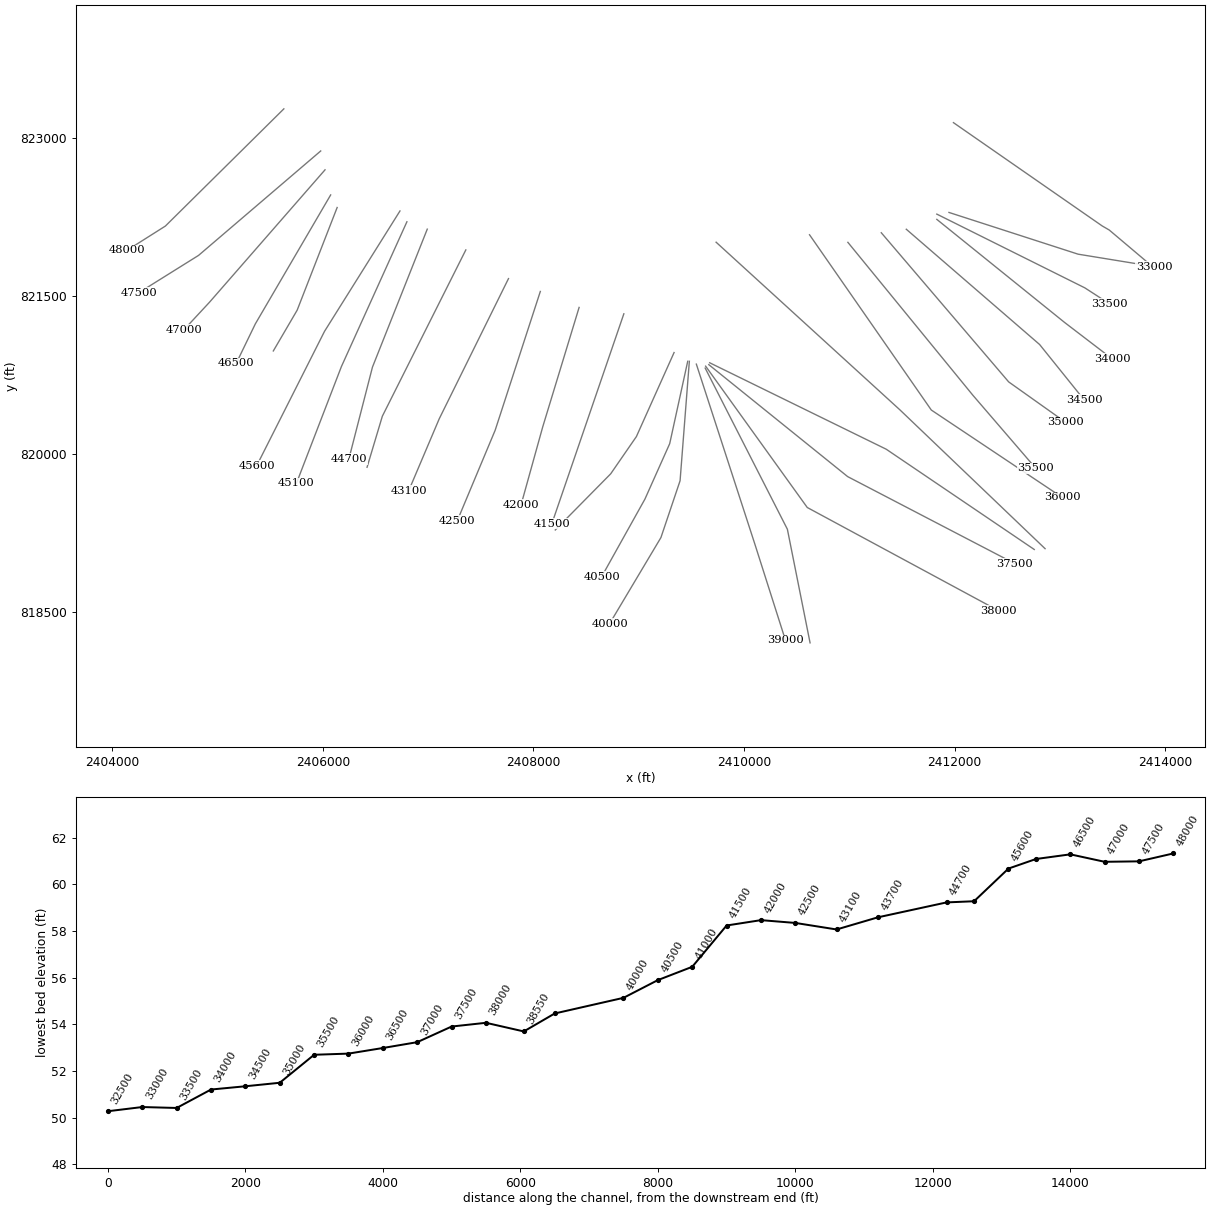
HEC-RAS study WillowCreek.prj: S-21-57 over Willow Creek

--- WillowCreek.g01 (geometry) --- (continued)

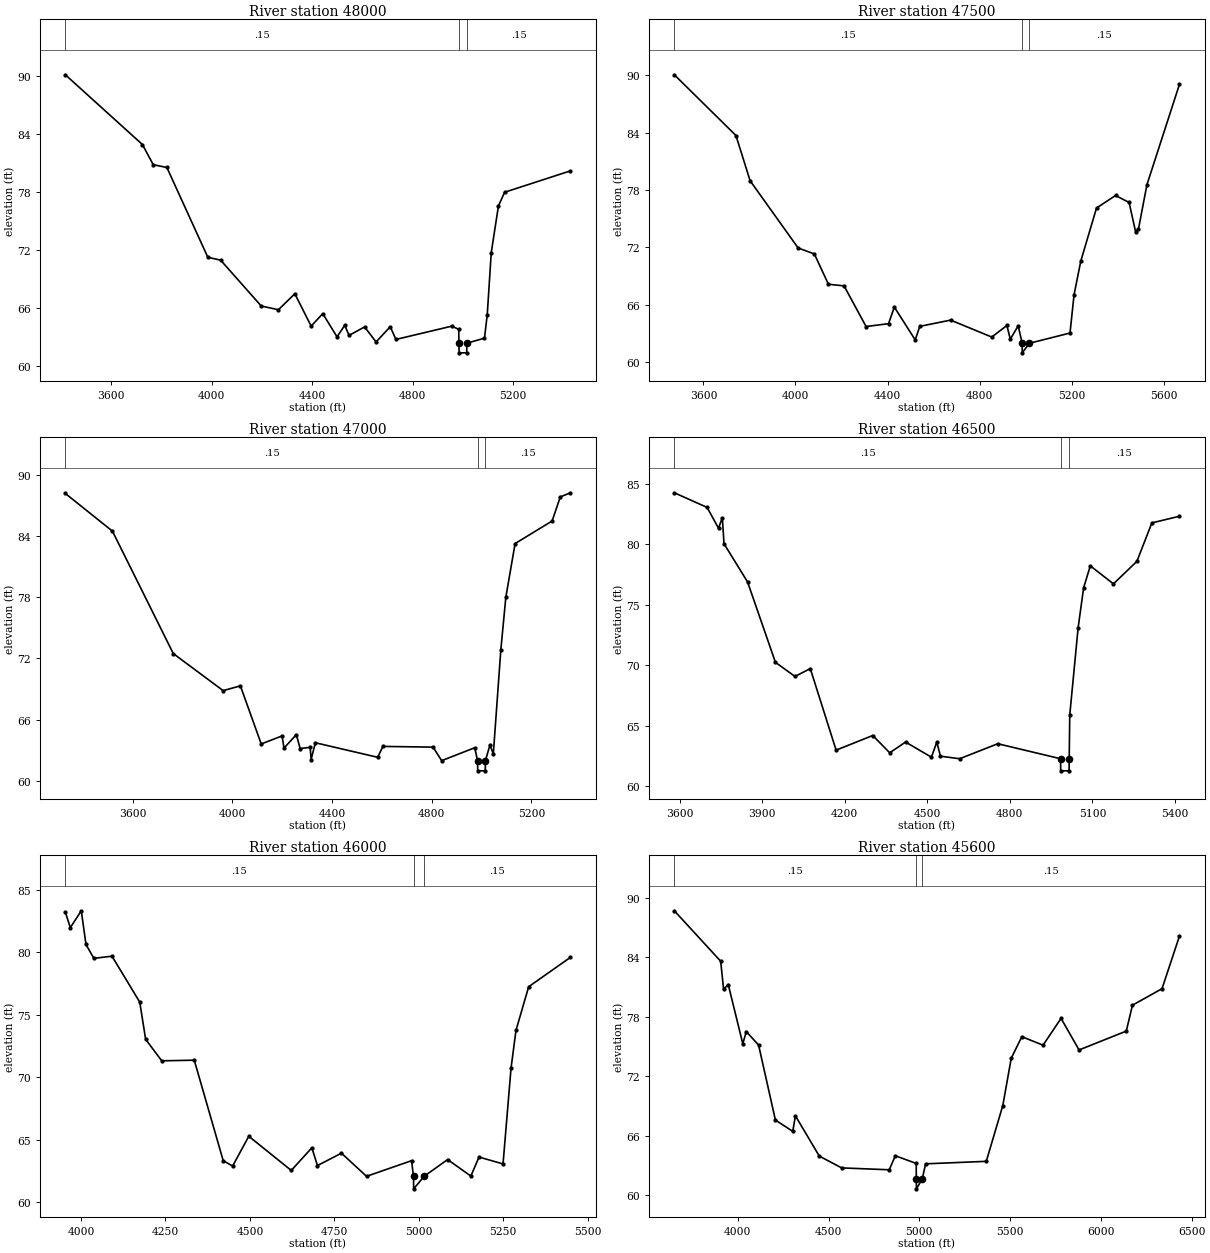
Type RM Length L Ch R = 1 ,48000   ,500,500,500
BEGIN DESCRIPTION:
Willow Creek 89.0
END DESCRIPTION:
XS GIS Cut Line= 3
      2405629.85       823276.68      2404504.79       822163.06
      2404142.92       821933.96
#Sta/Elev= 30
    3417   90.17    3724   82.93  3766.9   80.84  3821.3   80.55  3984.4   71.23
  4035.2   70.94    4197   66.18  4265.3   65.79  4330.8   67.45  4395.8   64.09
    4442   65.39  4498.8   62.98  4529.5   64.17  4546.8   63.13  4608.6   64.01
  4654.2   62.45  4710.7   64.03  4733.3   62.71  4955.9   64.09  4983.4   63.76
  4984.3   62.32  4984.8   61.32  5015.2   61.32  5015.7   62.32  5085.9   62.84
    5097   65.27  5112.9   71.71  5141.5   76.55  5165.9   77.98  5428.3    80.2
#Mann= 3 ,-1,0
    3417     .15       0  4984.3     .05       0  5015.7     .15       0
Bank Sta=4984.3,5015.7
XS Rating Curve= 0 ,0
Exp/Cntr=0.3,0.1

Type RM Length L Ch R = 1 ,47500   ,500,500,500
BEGIN DESCRIPTION:
Willow Creek 88.0
END DESCRIPTION:
XS GIS Cut Line= 3
      2405979.79       822876.62      2404820.03       821884.53
      2404253.95       821530.81
#Sta/Elev= 30
  3473.8   90.05  3741.4    83.7  3802.9   78.97  4011.6   71.94  4081.9   71.32
    4143   68.15    4211   67.98  4306.5   63.73  4404.2   64.03  4429.3   65.76
  4520.1   62.33  4539.8   63.75  4673.8    64.4  4852.5   62.63  4918.3   63.84
  4932.9   62.41  4967.4   63.81  4984.3   61.98  4984.8   60.98  5015.7   61.98
  5192.3   63.05  5209.8   67.05  5239.2   70.58  5307.4   76.12  5390.1   77.43
  5448.9    76.7    5477   73.65  5489.6   73.92  5526.4   78.56  5667.5   89.04
#Mann= 3 ,-1,0
  3473.8     .15       0  4984.3     .05       0  5015.7     .15       0
Bank Sta=4984.3,5015.7
XS Rating Curve= 0 ,0
Exp/Cntr=0.3,0.1

Type RM Length L Ch R = 1 ,47000   ,500,500,500
BEGIN DESCRIPTION:
Willow Creek 87.0
END DESCRIPTION:
XS GIS Cut Line= 3
      2406020.77       822697.45      2404922.78       821438.35
      2404679.82       821176.65
#Sta/Elev= 30
  3329.4   88.21  3518.4   84.51  3762.7   72.48  3962.9   68.84  4032.1   69.31
  4115.7    63.6  4199.2   64.39  4207.3    63.2  4256.7   64.52    4272   63.15
  4312.2   63.27  4316.1   62.07  4332.9   63.72  4583.3   62.29  4604.1   63.36
  4805.5   63.29  4840.1   61.96  4972.7   63.23  4984.3   61.96  4984.8   60.96
  5015.2   60.96  5015.7   61.96    5034    63.5  5047.4   62.61  5077.6   72.85
  5097.7   78.02  5134.9   83.29  5283.6   85.51  5316.2   87.87  5357.1   88.28
#Mann= 3 ,-1,0
  3329.4     .15       0  4984.3     .05       0  5015.7     .15       0
Bank Sta=4984.3,5015.7
XS Rating Curve= 0 ,0
Exp/Cntr=0.3,0.1

Type RM Length L Ch R = 1 ,46500   ,500,500,500
BEGIN DESCRIPTION:
Willow Creek 86.0
END DESCRIPTION:
XS GIS Cut Line= 3
      2406074.26       822458.89      2405358.78       821233.35
      2405177.49       820858.71
#Sta/Elev= 30
  3580.9   84.26    3700   83.05  3741.4   81.33  3755.3    82.2  3761.4   80.05
    3847   76.89  3948.2   70.25  4019.3   69.08  4074.9   69.73  4168.7   62.99
  4301.9    64.2  4363.5   62.77  4421.1   63.66    4515   62.41  4534.6   63.65
  4547.9   62.49  4617.7   62.28  4756.1   63.52  4984.3   62.28  4984.8   61.28
  5015.2   61.28  5015.7   62.28  5017.7    65.9  5048.1    73.1  5068.1   76.41
  5092.4   78.22  5176.5   76.73  5261.8    78.6    5316   81.77  5416.2   82.32
#Mann= 3 ,-1,0
  3580.9     .15       0  4984.3     .05       0  5015.7     .15       0
Bank Sta=4984.3,5015.7
XS Rating Curve= 0 ,0
Exp/Cntr=0.3,0.1

Type RM Length L Ch R = 1 ,46000   ,400,400,400
BEGIN DESCRIPTION:
Willow Creek 85.0
END DESCRIPTION:
XS GIS Cut Line= 3
      2406135.92       822339.52      2405756.32        821364.3
       2405529.8       820976.63
#Sta/Elev= 30
  3953.5   83.19  3968.2   81.95  4000.7    83.3  4014.5   80.61  4037.8    79.5
  4091.6   79.67  4173.8      76  4191.2   73.03  4238.9   71.31  4335.2   71.36
  4420.9   63.33  4448.7    62.9  4496.6   65.28  4622.4   62.55  4683.3   64.36
  4699.9   62.94    4771   63.93  4845.2   62.08  4978.5   63.33  4984.3   62.08
  4984.8   61.08  5015.7   62.08  5085.3   63.42  5154.1    62.1  5178.3   63.62
  5249.4   63.07  5273.1   70.73  5287.7   73.74  5325.3   77.23    5449   79.58
#Mann= 3 ,-1,0
  3953.5     .15       0  4984.3     .05       0  5015.7     .15       0
Bank Sta=4984.3,5015.7
XS Rating Curve= 0 ,0
Exp/Cntr=0.3,0.1

Type RM Length L Ch R = 1 ,45600   ,500,500,500
BEGIN DESCRIPTION:
Willow Creek 84.0
END DESCRIPTION:
XS GIS Cut Line= 3
      2406732.42       822306.69      2406016.16        821163.2
      2405370.85       819883.83
#Sta/Elev= 30
  3650.7   88.68  3905.9    83.6    3922   80.78  3947.7   81.25  4027.7   75.29
  4047.1   76.51  4114.9   75.15  4207.4    67.6  4302.9   66.46  4317.8   68.02
  4449.1   63.97  4572.4   62.78  4834.4   62.59    4868      64  4983.1   63.23
  4983.6   61.67  4984.1   60.67  5016.4   61.67  5034.7   63.19    5369   63.44
    5460   69.06  5506.4   73.82  5564.8      76  5681.6   75.14  5780.9   77.84
  5880.1   74.66  6140.2   76.56  6174.1   79.17    6337   80.83  6432.9   86.12
#Mann= 3 ,-1,0
  3650.7     .15       0  4983.6     .05       0  5016.4     .15       0
Bank Sta=4983.6,5016.4
XS Rating Curve= 0 ,0
Exp/Cntr=0.3,0.1

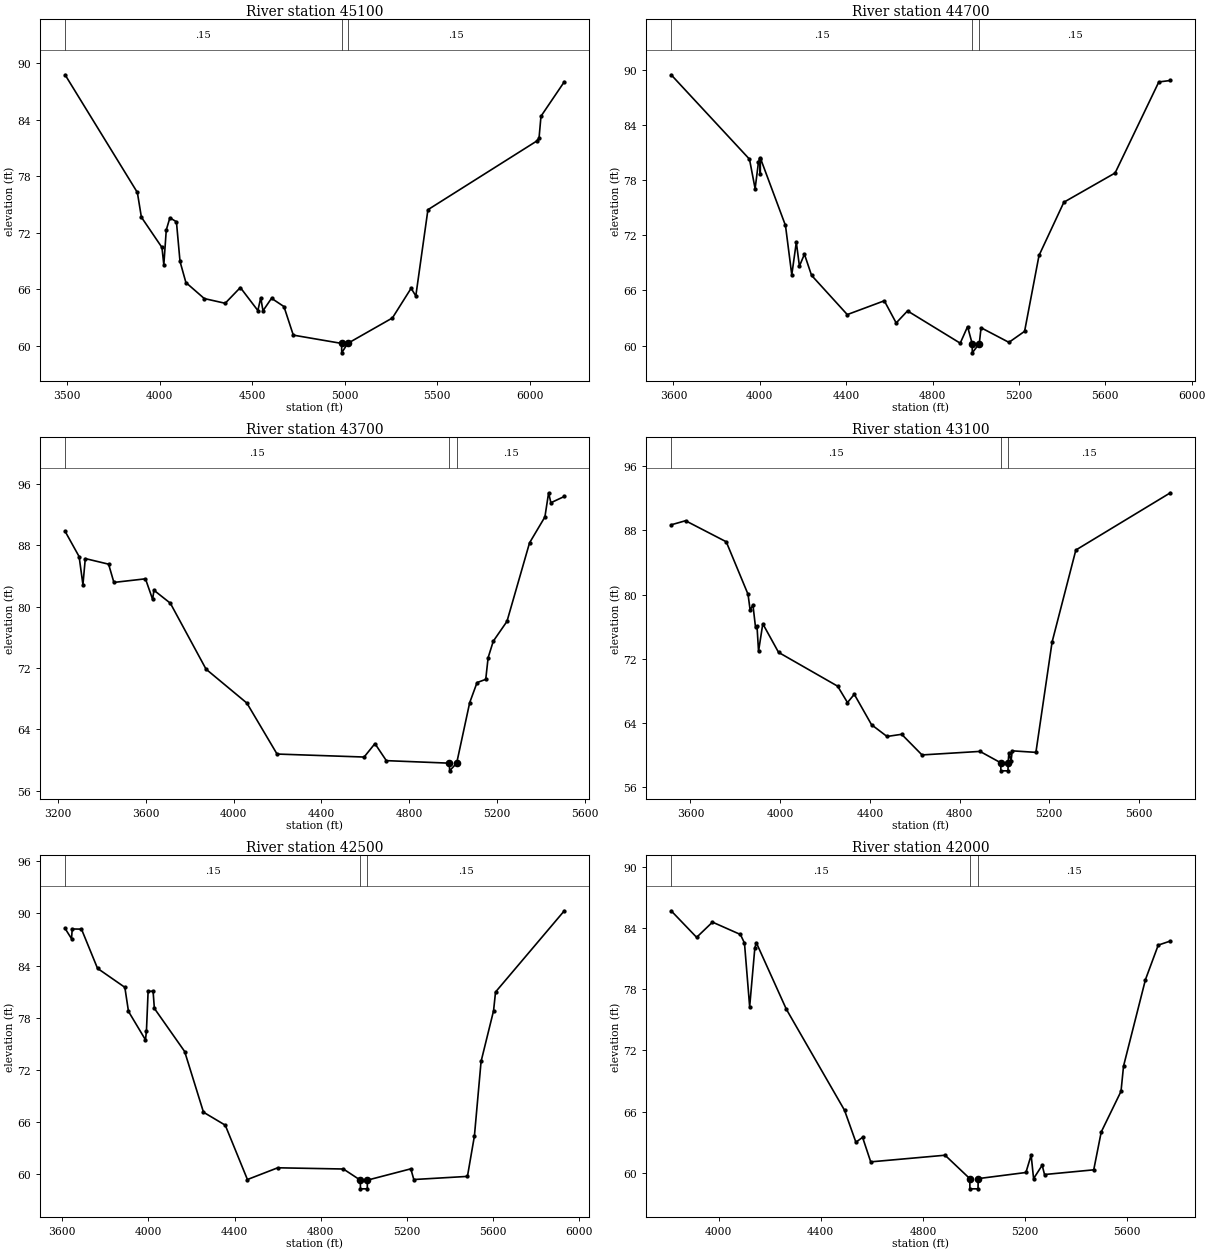
Type RM Length L Ch R = 1 ,45100   ,400,400,400
BEGIN DESCRIPTION:
Willow Creek 83.0
END DESCRIPTION:
XS GIS Cut Line= 3
      2406798.23       822203.83      2406175.84       820827.08
      2405749.28       819719.27
#Sta/Elev= 30
  3489.1   88.78  3879.8   76.29  3901.5   73.67  4012.8   70.45  4022.8   68.61
    4036   72.31  4055.5    73.6  4090.9   73.18  4110.3   68.97  4142.1   66.73
  4241.5   65.03  4354.4   64.53  4436.3    66.2    4531   63.76  4546.6   65.11
  4558.7   63.73  4604.8   65.06    4672   64.18  4722.5   61.15  4983.6   60.27
  4984.1   59.27  5016.4   60.27    5258   62.97  5359.1   66.12  5384.6   65.31
    5450   74.46  6037.5   81.74  6050.5   82.06    6061   84.38  6187.1   88.04
#Mann= 3 ,-1,0
  3489.1     .15       0  4983.6     .05       0  5016.4     .15       0
Bank Sta=4983.6,5016.4
XS Rating Curve= 0 ,0
Exp/Cntr=0.3,0.1

Type RM Length L Ch R = 1 ,44700   ,1000,1000,1000
BEGIN DESCRIPTION:
Willow Creek 82.0
END DESCRIPTION:
XS GIS Cut Line= 3
      2406991.56       822133.91      2406471.07       820822.85
      2406247.01       819949.64
#Sta/Elev= 30
  3589.4   89.46  3952.2   80.28  3978.3   77.08  3993.7   79.93  4001.4   80.34
  4002.1   78.63  4002.8   80.39  4118.9   73.07  4148.1    67.7  4169.1   71.25
  4183.5   68.65  4206.7   69.95  4239.6   67.65  4405.1   63.38  4576.6   64.88
  4631.6   62.47  4684.1   63.78  4928.2   60.27  4962.2   62.07  4983.6   60.22
  4984.1   59.22  5016.4   60.22  5024.7   61.95  5153.7   60.36  5226.3   61.56
  5293.1   69.81  5408.2    75.6  5645.5   78.78  5847.9   88.68  5901.5   88.84
#Mann= 3 ,-1,0
  3589.4     .15       0  4983.6     .05       0  5016.4     .15       0
Bank Sta=4983.6,5016.4
XS Rating Curve= 0 ,0
Exp/Cntr=0.3,0.1

Type RM Length L Ch R = 1 ,43700   ,600,600,600
BEGIN DESCRIPTION:
Willow Creek 81.0
END DESCRIPTION:
XS GIS Cut Line= 3
      2407357.67       821936.46      2406565.08       820356.85
      2406419.77       819871.43
#Sta/Elev= 30
  3232.7   89.82  3296.7   86.52  3314.1   82.85  3324.8   86.26    3431   85.53
  3455.1   83.15  3598.9   83.62  3631.5   80.94  3637.5   82.13  3712.2   80.44
  3874.8   71.84  4060.7   67.42  4198.2   60.77  4594.8   60.38  4644.1   62.13
    4696   59.91  4983.6   59.58  4984.1   58.58  5016.4   59.58  5075.7   67.47
  5109.2   70.09  5148.8   70.51  5159.6   73.33  5183.2   75.49  5245.5   78.07
  5348.3   88.31  5418.3   91.69  5435.2   94.84  5445.5   93.54  5506.7   94.36
#Mann= 3 ,-1,0
  3232.7     .15       0  4983.6     .05       0  5016.4     .15       0
Bank Sta=4983.6,5016.4
XS Rating Curve= 0 ,0
Exp/Cntr=0.3,0.1

Type RM Length L Ch R = 1 ,43100   ,600,600,600
BEGIN DESCRIPTION:
Willow Creek 80.0
END DESCRIPTION:
XS GIS Cut Line= 3
      2407762.82       821664.08      2407104.86       820331.35
      2406815.93       819650.08
#Sta/Elev= 30
  3513.7   88.69  3577.9    89.2  3759.4   86.58  3856.6   80.04  3865.9   78.08
  3878.4   78.72    3890   75.93  3896.6   76.06  3903.5   72.95  3922.4   76.37
  3992.7   72.81  4256.2    68.6  4300.1   66.56  4330.4   67.59  4407.4    63.8
  4476.3   62.34  4541.7   62.61  4632.4   60.04  4890.9   60.48  4983.6   59.06
  4984.1   58.06  5015.9   58.06  5016.4   59.06  5019.8   60.31  5029.6    59.3
  5034.7   60.55  5140.3   60.36  5212.4   74.09  5318.4   85.55    5740   92.68
#Mann= 3 ,-1,0
  3513.7     .15       0  4983.6     .05       0  5016.4     .15       0
Bank Sta=4983.6,5016.4
XS Rating Curve= 0 ,0
Exp/Cntr=0.3,0.1

Type RM Length L Ch R = 1 ,42500   ,500,500,500
BEGIN DESCRIPTION:
Willow Creek 79.0
END DESCRIPTION:
XS GIS Cut Line= 3
      2408065.09       821541.93      2407636.23       820223.21
      2407277.23       819364.97
#Sta/Elev= 30
  3613.3   88.28  3643.2    87.1  3646.6   88.22  3689.5    88.2  3763.9   83.69
  3890.7   81.51  3907.6   78.74  3986.5   75.47    3991   76.51  3998.7   81.04
  4021.8   81.07  4027.7   79.09  4168.3   74.13  4255.7   67.15  4356.7   65.66
  4459.6   59.41  4600.2   60.76  4904.9   60.62  4983.6   59.34  4984.1   58.34
  5015.9   58.34  5016.4   59.34  5217.9   60.64  5231.8   59.41  5480.7   59.77
  5513.1   64.42    5544   72.99  5601.9   78.81  5611.1   80.97  5930.3   90.31
#Mann= 3 ,-1,0
  3613.3     .15       0  4983.6     .05       0  5016.4     .15       0
Bank Sta=4983.6,5016.4
XS Rating Curve= 0 ,0
Exp/Cntr=0.3,0.1

Type RM Length L Ch R = 1 ,42000   ,500,500,500
BEGIN DESCRIPTION:
Willow Creek 78.0
END DESCRIPTION:
XS GIS Cut Line= 3
      2408433.35       821390.16      2408088.01       820255.55
      2407882.14       819514.41
#Sta/Elev= 30
    3814   85.67  3913.8   83.07  3975.9   84.56  4085.3   83.35  4101.2   82.51
  4121.5   76.28  4141.7   82.01  4147.5   82.55  4265.1   76.04    4493   66.15
  4537.6   63.02  4563.7    63.5  4595.6    61.1  4886.8   61.75  4983.6   59.46
  4984.1   58.46  5015.9   58.46  5016.4   59.46  5203.4   60.06  5223.9   61.76
  5233.4   59.46  5267.1   60.77  5276.2   59.86    5469   60.32  5498.3   64.02
  5575.8      68  5585.7   70.47  5671.6   78.94  5721.6   82.31  5769.2   82.71
#Mann= 3 ,-1,0
    3814     .15       0  4983.6     .05       0  5016.4     .15       0
Bank Sta=4983.6,5016.4
XS Rating Curve= 0 ,0
Exp/Cntr=0.3,0.1

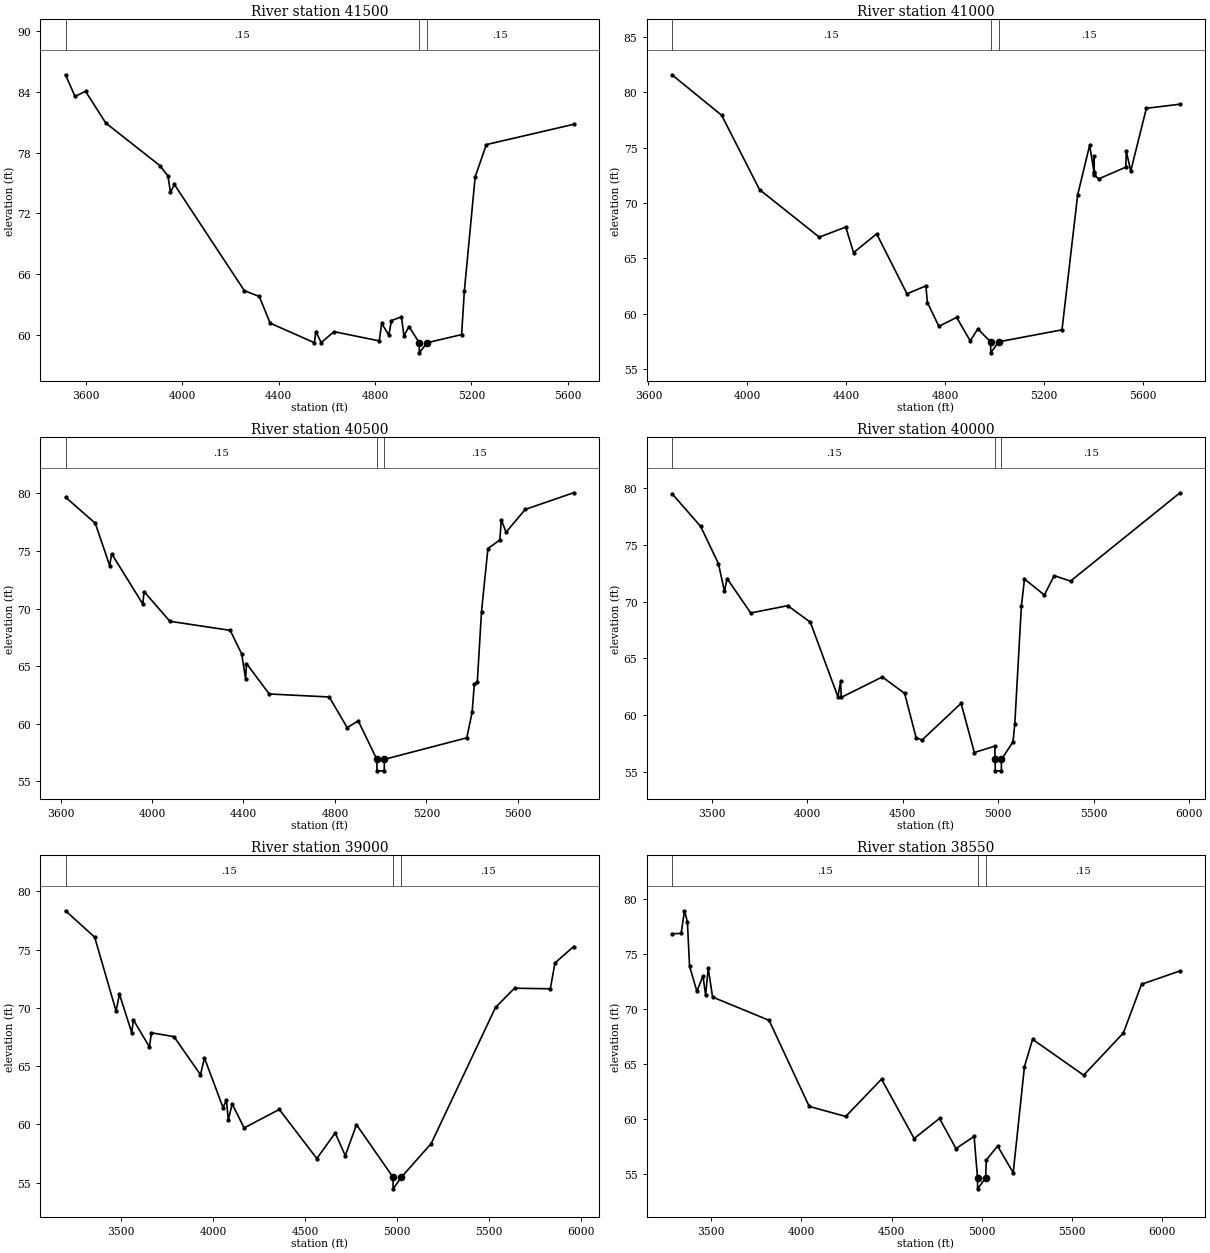
Type RM Length L Ch R = 1 ,41500   ,500,500,500
BEGIN DESCRIPTION:
Willow Creek 77.0
END DESCRIPTION:
XS GIS Cut Line= 3
      2408858.17       821329.48      2408376.57       819924.53
      2408173.94       819333.82
#Sta/Elev= 30
  3514.8   85.67  3554.2   83.53    3598   84.04  3682.1   80.91  3906.6   76.71
  3940.3   75.68  3950.6   74.07  3966.8   74.85  4257.3   64.37  4319.7   63.79
  4364.5   61.16  4548.3   59.23  4554.4   60.33  4576.6   59.24  4629.7   60.32
  4817.6   59.41  4827.8   61.13  4857.4   59.99  4868.5   61.42    4910   61.78
  4920.2   59.92  4941.3   60.82  4983.6   59.23  4984.1   58.23  5016.4   59.23
  5159.7   60.03  5170.9   64.29  5215.9   75.59  5262.4   78.78  5624.5   80.78
#Mann= 3 ,-1,0
  3514.8     .15       0  4983.6     .05       0  5016.4     .15       0
Bank Sta=4983.6,5016.4
XS Rating Curve= 0 ,0
Exp/Cntr=0.3,0.1

Type RM Length L Ch R = 1 ,41000   ,500,500,500
BEGIN DESCRIPTION:
Willow Creek 76.0
END DESCRIPTION:
XS GIS Cut Line= 4
      2409335.02       820961.42      2408977.37        820163.2
      2408733.27        819809.3      2408207.12       819275.81
#Sta/Elev= 30
  3695.4    81.6  3896.2   77.94  4049.3   71.22  4290.9   66.92    4398   67.83
  4429.6   65.52    4523   67.22  4645.4    61.8  4721.8   62.51    4728   61.01
  4774.5   58.86  4846.4   59.66  4901.2   57.54  4931.8   58.62  4983.6   57.46
  4984.1   56.46  5016.4   57.46  5272.2   58.54  5335.4   70.73    5384   75.23
  5401.9   72.77  5402.4   74.25  5402.5   72.71  5403.1   72.56  5419.9   72.18
  5529.9   73.25  5532.3   74.67  5550.1    72.9  5613.3   78.57  5749.3   78.94
#Mann= 3 ,-1,0
  3695.4     .15       0  4983.6     .05       0  5016.4     .15       0
Bank Sta=4983.6,5016.4
XS Rating Curve= 0 ,0
Exp/Cntr=0.3,0.1

Type RM Length L Ch R = 1 ,40500   ,500,500,500
BEGIN DESCRIPTION:
Willow Creek 75.0
END DESCRIPTION:
XS GIS Cut Line= 4
       2409464.6       820878.47      2409293.56       820095.81
      2409058.12       819568.73      2408647.24        818831.5
#Sta/Elev= 30
  3621.6   79.68  3751.8   77.41  3814.9   73.73  3823.5   74.76  3959.6   70.39
  3965.3   71.47  4078.2   68.89  4342.1    68.1  4392.3   66.05  4409.7   63.87
  4413.3   65.22  4512.8   62.57  4775.3   62.31  4853.7   59.65  4902.2   60.23
  4983.6   56.89  4984.1   55.89  5015.9   55.89  5016.4   56.89    5377   58.76
  5400.3   60.98  5409.9   63.42  5423.1   63.64  5441.4   69.74  5469.4   75.21
  5521.6   75.96  5527.9    77.7  5548.9   76.63  5632.3   78.61    5844   80.06
#Mann= 3 ,-1,0
  3621.6     .15       0  4983.6     .05       0  5016.4     .15       0
Bank Sta=4983.6,5016.4
XS Rating Curve= 0 ,0
Exp/Cntr=0.3,0.1

Type RM Length L Ch R = 1 ,40000   ,1000,1000,1000
BEGIN DESCRIPTION:
Willow Creek 74.0
END DESCRIPTION:
XS GIS Cut Line= 4
      2409480.16       820878.51      2409392.04       819743.35
      2409210.22       819203.63      2408723.37       818386.47
#Sta/Elev= 30
  3291.9   79.49  3441.8   76.61    3535   73.34  3566.4   70.93  3580.7   72.02
    3704      69  3897.8   69.64  4016.2   68.19  4160.4   61.64  4174.8   62.99
  4177.8   61.58  4393.1   63.38  4509.8   61.93  4569.8   58.05    4601   57.84
  4805.1   61.06  4874.8   56.74  4981.7    57.3  4983.6   56.13  4984.1   55.13
  5015.9   55.13  5016.4   56.13  5076.8   57.67  5086.4   59.25  5120.9   69.61
  5137.1   71.98  5241.3   70.58  5292.4   72.28    5378    71.8  5951.2   79.56
#Mann= 3 ,-1,0
  3291.9     .15       0  4983.6     .05       0  5016.4     .15       0
Bank Sta=4983.6,5016.4
XS Rating Curve= 0 ,0
Exp/Cntr=0.3,0.1

Type RM Length L Ch R = 1 ,39000   ,450,450,450
BEGIN DESCRIPTION:
Willow Creek 72.0
END DESCRIPTION:
XS GIS Cut Line= 3
      2409546.58       820851.47      2410103.07       819138.49
      2410393.46       818225.98
#Sta/Elev= 30
  3198.9   78.34  3357.1   76.08  3473.5   69.73  3491.8   71.18  3558.6   67.87
  3567.6   68.97  3654.5   66.65  3665.8   67.86  3787.9   67.53  3931.8   64.26
  3953.4    65.7  4054.2   61.44  4072.9   62.09  4082.7   60.39  4104.1   61.74
  4168.8   59.69  4359.7   61.28  4563.6   57.06  4663.3   59.26  4718.1   57.31
  4778.9   59.97  4977.3   55.46  4977.8   54.46  5022.7   55.46  5184.6   58.35
  5533.9   70.04  5637.1   71.69  5831.4   71.64  5856.7   73.86  5957.6   75.26
#Mann= 3 ,-1,0
  3198.9     .15       0  4977.3     .05       0  5022.7     .15       0
Bank Sta=4977.3,5022.7
XS Rating Curve= 0 ,0
Exp/Cntr=0.3,0.1

Type RM Length L Ch R = 1 ,38550   ,550,550,550
BEGIN DESCRIPTION:
Willow Creek 71.0
END DESCRIPTION:
XS GIS Cut Line= 3
      2409630.48        820813.7      2410410.88       819282.95
      2410626.39       818203.35
#Sta/Elev= 30
  3281.8   76.81  3332.6   76.84  3351.3   78.89  3367.4   77.89  3379.3   73.88
    3420   71.59  3453.9   72.99  3468.6   71.24    3483   73.69  3507.2   71.07
  3820.7   68.96  4043.3   61.16  4245.8   60.25  4444.7   63.63  4625.6   58.25
  4766.3   60.07  4857.7   57.34  4958.3   58.44  4977.3   54.69  4977.8   53.69
  5022.7   54.69  5025.8    56.3  5088.9   57.57  5175.3   55.15  5237.7   64.77
  5282.8   67.24  5566.3   63.99  5786.4   67.81  5887.4   72.23  6100.9   73.44
#Mann= 3 ,-1,0
  3281.8     .15       0  4977.3     .05       0  5022.7     .15       0
Bank Sta=4977.3,5022.7
XS Rating Curve= 0 ,0
Exp/Cntr=0.3,0.1

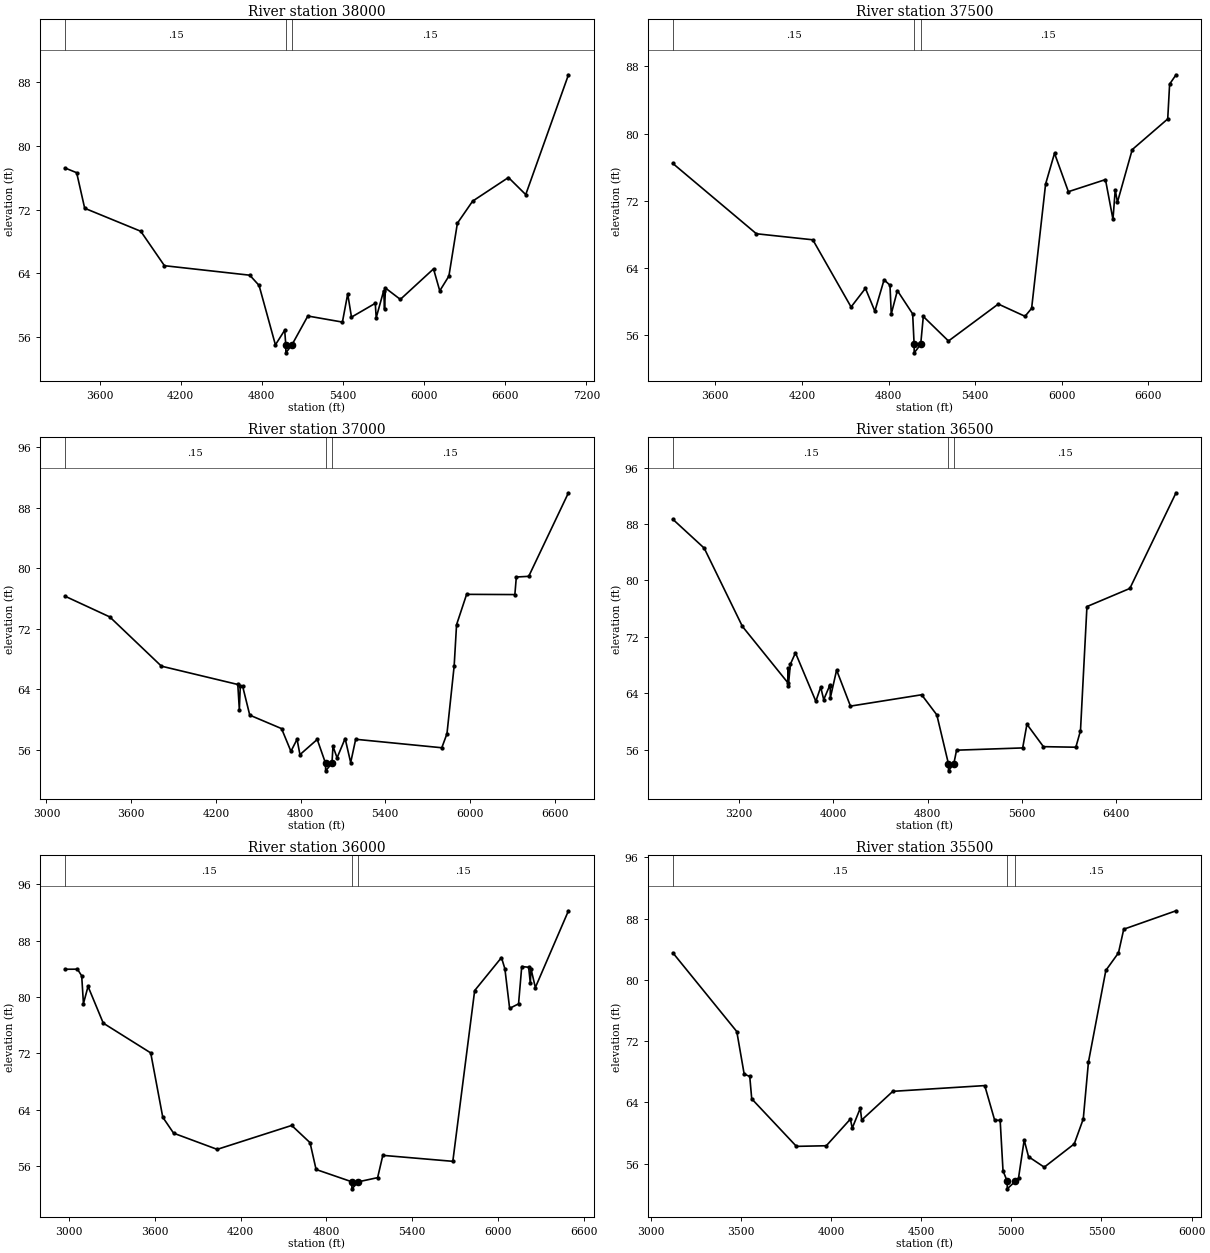
Type RM Length L Ch R = 1 ,38000   ,500,500,500
BEGIN DESCRIPTION:
Willow Creek 70.0
END DESCRIPTION:
XS GIS Cut Line= 3
      2409634.63       820832.21      2410599.63       819489.39
      2412419.12       818507.12
#Sta/Elev= 30
  3346.4   77.19  3430.7   76.61    3490   72.16  3904.7   69.28  4079.8   64.97
  4710.8   63.78  4779.7    62.5  4900.5   55.06  4969.1   56.89  4977.3   55.06
  4977.8   54.06  5022.7   55.06  5140.3   58.67    5396   57.91  5435.2   61.44
  5463.1   58.53    5639   60.26  5645.9   58.46  5701.4   61.84  5707.5   59.52
  5714.5   62.17  5824.4   60.75  6069.8   64.57    6116   61.82  6183.5   63.67
  6246.4   70.29    6359   73.05  6623.9   76.01  6751.7   73.87  7067.7   88.87
#Mann= 3 ,-1,0
  3346.4     .15       0  4977.3     .05       0  5022.7     .15       0
Bank Sta=4977.3,5022.7
XS Rating Curve= 0 ,0
Exp/Cntr=0.3,0.1

Type RM Length L Ch R = 1 ,37500   ,500,500,500
BEGIN DESCRIPTION:
Willow Creek 69.0
END DESCRIPTION:
XS GIS Cut Line= 3
      2409664.84       820846.34      2410983.25       819782.81
        2412572.       818955.38
#Sta/Elev= 30
  3306.1   76.45  3884.8   68.08  4275.6   67.36  4540.6   59.36    4640   61.58
  4705.3   58.86  4769.2    62.6    4810   61.95    4819   58.54  4861.3   61.31
  4967.1   58.54  4977.3    54.9  4977.8    53.9  5022.7    54.9  5040.9   58.23
  5215.2   55.31  5560.2   59.71  5745.5   58.25  5791.1    59.2  5887.9      74
  5949.6   77.66  6045.7   73.09  6302.5   74.53  6354.5    69.8  6370.2   73.31
  6385.5   71.84  6487.9    78.1  6733.7   81.75  6746.9    85.9  6791.3   87.01
#Mann= 3 ,-1,0
  3306.1     .15       0  4977.3     .05       0  5022.7     .15       0
Bank Sta=4977.3,5022.7
XS Rating Curve= 0 ,0
Exp/Cntr=0.3,0.1

Type RM Length L Ch R = 1 ,37000   ,500,500,500
BEGIN DESCRIPTION:
Willow Creek 68.0
END DESCRIPTION:
XS GIS Cut Line= 3
      2409673.18       820864.35      2411349.48       820043.01
      2412755.18       819090.35
#Sta/Elev= 30
  3133.3   76.29  3448.4   73.57  3814.5   67.06  4355.6   64.64  4366.6   61.31
  4373.1   64.39  4389.3   64.45  4440.3   60.59  4665.6   58.81    4732   55.81
  4775.4    57.4  4795.9   55.37  4918.3   57.38  4977.3   54.23  4977.8   53.23
  5022.7   54.23  5029.9   56.47  5058.9   54.95  5115.9    57.5  5155.3   54.32
  5190.7    57.4  5800.8   56.28  5837.4   58.13  5888.4   67.09  5905.4   72.54
  5976.6   76.55  6318.4   76.52  6328.8   78.84  6416.6   78.93  6698.1   89.97
#Mann= 3 ,-1,0
  3133.3     .15       0  4977.3     .05       0  5022.7     .15       0
Bank Sta=4977.3,5022.7
XS Rating Curve= 0 ,0
Exp/Cntr=0.3,0.1

Type RM Length L Ch R = 1 ,36500   ,500,500,500
BEGIN DESCRIPTION:
Willow Creek 67.0
END DESCRIPTION:
XS GIS Cut Line= 3
      2409734.27        822009.7      2411478.69       820417.65
      2412857.95       819098.12
#Sta/Elev= 30
  2638.3   88.66  2904.4   84.57  3228.5   73.47  3613.2    65.5  3616.3   67.59
  3618.9   65.05  3635.5   68.09    3679   69.72  3851.9   62.85  3893.2   64.85
  3918.8   63.08  3970.4   65.11  3974.2   64.95  3974.4   63.29  4028.2   67.27
  4145.7   62.16  4749.8   63.77  4878.6   60.92  4977.3   53.98  4977.8   52.98
  5022.7   53.98  5046.2   55.91  5607.3   56.23  5643.4   59.59  5783.3   56.41
  6058.6   56.33  6097.9   58.68  6152.7   76.28  6516.8   78.85  6908.8   92.42
#Mann= 3 ,-1,0
  2638.3     .15       0  4977.3     .05       0  5022.7     .15       0
Bank Sta=4977.3,5022.7
XS Rating Curve= 0 ,0
Exp/Cntr=0.3,0.1

Type RM Length L Ch R = 1 ,36000   ,500,500,500
BEGIN DESCRIPTION:
Willow Creek 66.0
END DESCRIPTION:
XS GIS Cut Line= 3
      2410621.26       822080.38      2411777.55       820415.29
      2413018.69       819586.55
#Sta/Elev= 30
  2972.8   83.95  3057.9   83.96  3087.8   83.01  3099.9   79.07  3132.1   81.51
  3238.6   76.29  3570.5   72.06  3654.8   62.92  3730.6   60.65  4035.4   58.35
  4556.6   61.75  4684.9    59.3  4727.2   55.49  4977.3   53.74  4977.8   52.74
  5022.7   53.74  5157.6   54.33    5194    57.5  5683.6   56.65  5836.4   80.92
  6023.9   85.61  6047.8   84.01  6080.9   78.39  6143.3   79.03  6165.7   84.34
  6214.1   84.23  6225.7   81.96  6230.5   84.01  6260.8   81.35  6492.4   92.26
#Mann= 3 ,-1,0
  2972.8     .15       0  4977.3     .05       0  5022.7     .15       0
Bank Sta=4977.3,5022.7
XS Rating Curve= 0 ,0
Exp/Cntr=0.3,0.1

Type RM Length L Ch R = 1 ,35500   ,500,500,500
BEGIN DESCRIPTION:
Willow Creek 65.0
END DESCRIPTION:
XS GIS Cut Line= 3
       2410985.4       822008.48      2412172.75       820555.14
      2412768.46        819862.6
#Sta/Elev= 30
  3123.3   83.53  3477.9   73.24  3518.8   67.69  3549.8   67.37  3560.7   64.45
  3808.6   58.24  3974.2   58.32  4107.6    61.8  4118.3   60.63  4162.7   63.23
  4170.5   61.68  4343.2   65.43  4852.8   66.18  4907.8   61.66  4938.3   61.64
  4954.1   55.05  4977.3   53.69  4977.8   52.69  5022.7   53.69  5040.1    54.1
  5071.5   59.06  5095.6   56.89  5182.8   55.52  5349.1   58.56  5399.1   61.82
  5427.8   69.25  5524.3   81.23  5594.3   83.52  5623.5   86.61  5913.5   89.02
#Mann= 3 ,-1,0
  3123.3     .15       0  4977.3     .05       0  5022.7     .15       0
Bank Sta=4977.3,5022.7
XS Rating Curve= 0 ,0
Exp/Cntr=0.3,0.1

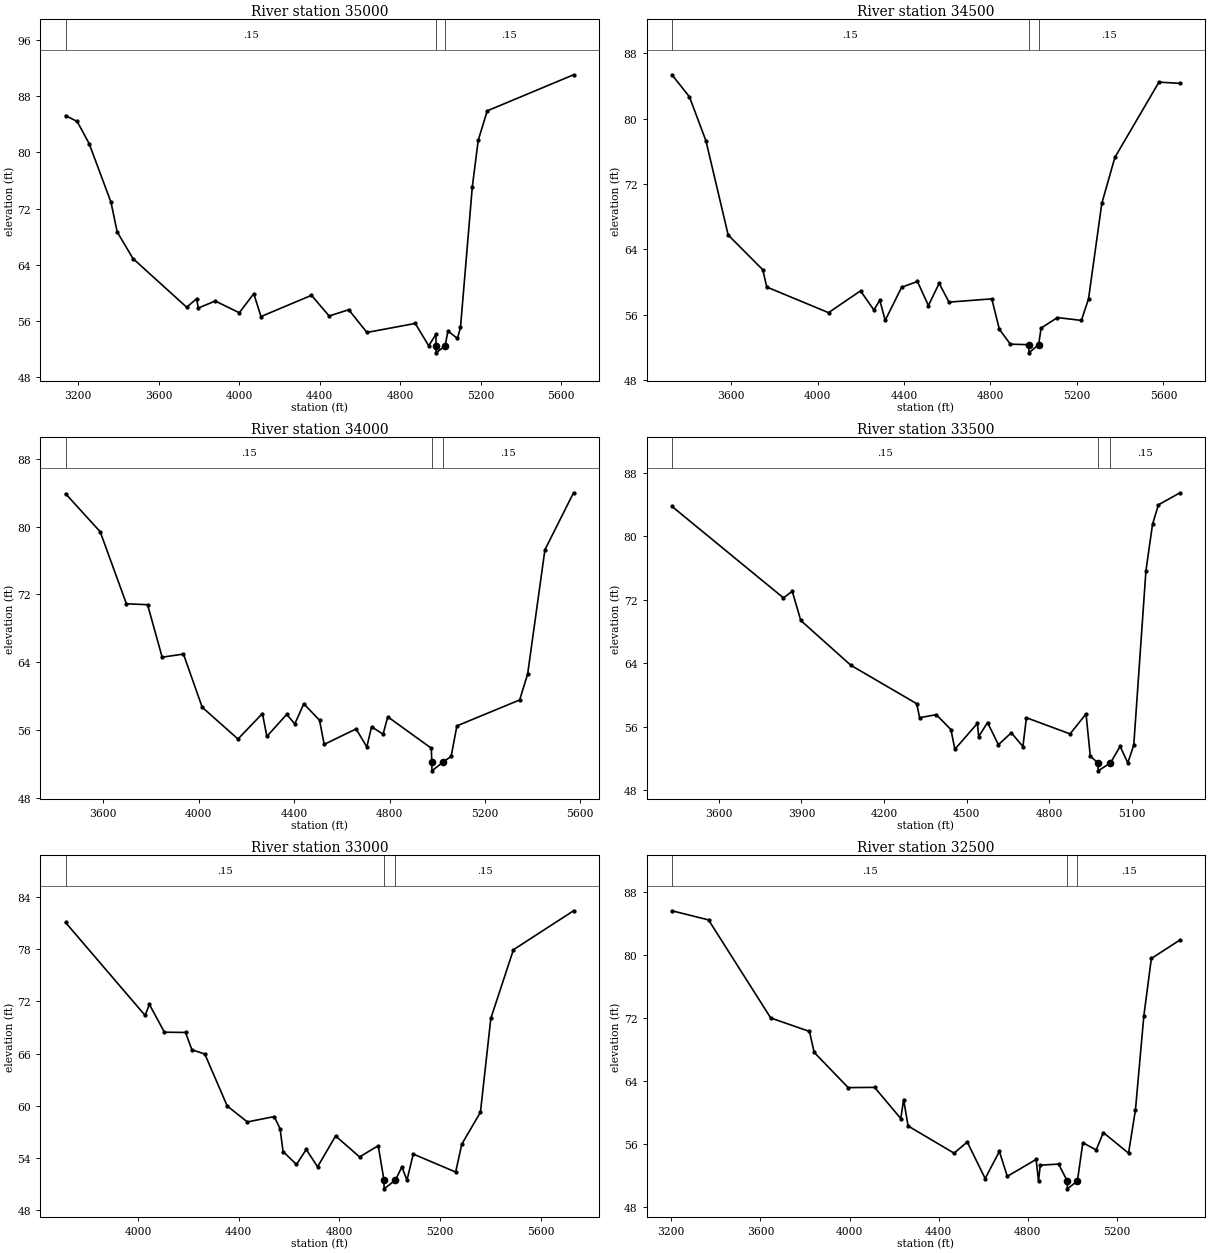
Type RM Length L Ch R = 1 ,35000   ,500,500,500
BEGIN DESCRIPTION:
Willow Creek 64.0
END DESCRIPTION:
XS GIS Cut Line= 3
      2411302.58       822099.65      2412512.23       820682.52
      2413050.81         820300.
#Sta/Elev= 30
  3136.8   85.23  3194.7   84.39  3254.1   81.25  3362.7   72.91  3393.5   68.69
  3472.2   64.89  3738.6   57.98  3788.1   59.18  3796.3   57.86  3880.7   58.86
  4000.1   57.19  4072.1    59.9  4107.9   56.65  4358.8   59.67  4446.5   56.73
  4543.9   57.62  4634.1   54.39  4874.2   55.67  4941.2   52.49  4977.2   54.13
  4977.3   52.49  4977.8   51.49  5022.7   52.49  5036.7    54.6  5083.8   53.53
    5099   55.11  5157.6   75.08  5187.2   81.73  5231.8    85.9  5660.6   91.03
#Mann= 3 ,-1,0
  3136.8     .15       0  4977.3     .05       0  5022.7     .15       0
Bank Sta=4977.3,5022.7
XS Rating Curve= 0 ,0
Exp/Cntr=0.3,0.1

Type RM Length L Ch R = 1 ,34500   ,500,500,500
BEGIN DESCRIPTION:
Willow Creek 63.0
END DESCRIPTION:
XS GIS Cut Line= 3
      2411540.05       822132.86       2412805.8       821037.95
      2413229.83       820510.45
#Sta/Elev= 30
  3326.4   85.39  3407.2   82.69  3483.7   77.29  3586.4   65.77  3746.6   61.51
  3764.9    59.4  4050.7   56.26  4198.7   58.93  4260.5   56.59    4288   57.78
  4312.8   55.32  4388.9   59.37  4462.1   60.08  4512.8   57.13  4562.4   59.85
  4608.1   57.55  4806.1   57.95    4841   54.22    4892    52.4  4977.3   52.34
  4977.8   51.34  5022.7   52.34    5034   54.37  5109.7   55.66  5220.4   55.31
  5253.5   57.94  5314.9   69.63  5375.4   75.27  5579.4   84.49  5676.8   84.34
#Mann= 3 ,-1,0
  3326.4     .15       0  4977.3     .05       0  5022.7     .15       0
Bank Sta=4977.3,5022.7
XS Rating Curve= 0 ,0
Exp/Cntr=0.3,0.1

Type RM Length L Ch R = 1 ,34000   ,500,500,500
BEGIN DESCRIPTION:
Willow Creek 62.0
END DESCRIPTION:
XS GIS Cut Line= 3
      2411829.82       822226.65      2413042.64       821247.72
      2413496.38       820900.42
#Sta/Elev= 30
  3441.4   83.89  3586.7    79.4  3696.7    70.9  3785.5   70.79  3846.6    64.6
  3935.9   64.97  4014.5    58.7  4164.5   54.95    4267   57.96  4285.6   55.26
  4368.9   57.86  4402.7   56.73  4440.5   59.11  4506.3   57.17    4526   54.32
  4659.6   56.14  4704.8   54.02  4724.4   56.39  4772.9   55.53  4792.6   57.57
    4975   53.87  4977.3    52.2  4977.8    51.2  5022.7    52.2  5058.3   52.91
  5082.3    56.5  5345.5   59.56  5378.9   62.61  5451.4   77.27  5571.4   83.99
#Mann= 3 ,-1,0
  3441.4     .15       0  4977.3     .05       0  5022.7     .15       0
Bank Sta=4977.3,5022.7
XS Rating Curve= 0 ,0
Exp/Cntr=0.3,0.1

Type RM Length L Ch R = 1 ,33500   ,500,500,500
BEGIN DESCRIPTION:
Willow Creek 61.0
END DESCRIPTION:
XS GIS Cut Line= 3
       2411829.8       822276.66      2413235.11       821576.21
       2413466.2       821426.59
#Sta/Elev= 30
  3429.8   83.77  3834.8   72.23  3866.7   73.06  3897.7   69.38  4079.9   63.72
  4318.9   58.88  4329.4   57.11    4390    57.5  4443.2   55.61  4457.4   53.13
  4539.3    56.4  4543.9   54.73  4576.1    56.5  4615.6   53.71  4662.5   55.21
  4704.6   53.48  4717.4   57.11  4875.9   55.07  4933.9   57.59  4949.4   52.26
  4977.3   51.41  4977.8   50.41  5022.7   51.41  5057.7    53.5  5085.7   51.41
  5107.3   53.66  5151.5   75.65  5175.6   81.54  5196.8   83.97  5275.3   85.49
#Mann= 3 ,-1,0
  3429.8     .15       0  4977.3     .05       0  5022.7     .15       0
Bank Sta=4977.3,5022.7
XS Rating Curve= 0 ,0
Exp/Cntr=0.3,0.1

Type RM Length L Ch R = 1 ,33000   ,500,500,500
BEGIN DESCRIPTION:
Willow Creek 60.0
END DESCRIPTION:
XS GIS Cut Line= 3
      2411945.32        822292.5      2413171.42       821896.07
      2413892.78       821778.32
#Sta/Elev= 30
  3711.4   81.08  4027.8   70.39  4044.8   71.65  4104.6   68.46  4188.6   68.43
  4213.7   66.44  4265.1   65.95  4354.3   59.97  4434.5   58.14  4541.2   58.76
  4564.4   57.34  4576.2   54.74  4629.5   53.25  4668.3   54.98  4713.4   52.98
    4785   56.53  4880.4   54.12  4954.4   55.41  4977.3   51.45  4977.8   50.45
  5022.7   51.45  5048.5   52.97  5068.7   51.45  5093.7   54.45  5262.3   52.38
  5286.6   55.58  5360.8   59.26  5402.1   70.05  5491.9   77.94  5730.9   82.42
#Mann= 3 ,-1,0
  3711.4     .15       0  4977.3     .05       0  5022.7     .15       0
Bank Sta=4977.3,5022.7
XS Rating Curve= 0 ,0
Exp/Cntr=0.3,0.1

Type RM Length L Ch R = 1 ,32500   ,500,500,500
BEGIN DESCRIPTION:
Willow Creek 59.0
END DESCRIPTION:
XS GIS Cut Line= 4
      2411987.74        823145.7      2413400.24       822164.23
      2413466.87       822125.65      2413835.92       821813.75
#Sta/Elev= 30
    3203   85.65  3367.1   84.49  3646.2   72.01    3820    70.3  3841.1   67.64
  3993.8   63.15  4112.4   63.18  4230.1   59.21  4242.6   61.63  4262.7   58.27
  4469.1   54.81  4528.3   56.23  4608.6   51.58  4672.5   55.03    4708   51.86
  4837.4   54.01  4848.2   51.27  4855.9   53.28  4938.3   53.42  4977.3   51.27
  4977.8   50.27  5022.7   51.27    5047   56.14    5107   55.22    5139   57.43
  5252.2   54.81  5283.2   60.32  5320.9   72.29  5354.6   79.58  5483.2   81.94
#Mann= 3 ,-1,0
    3203     .15       0  4977.3     .05       0  5022.7     .15       0
Bank Sta=4977.3,5022.7
XS Rating Curve= 0 ,0
Exp/Cntr=0.3,0.1