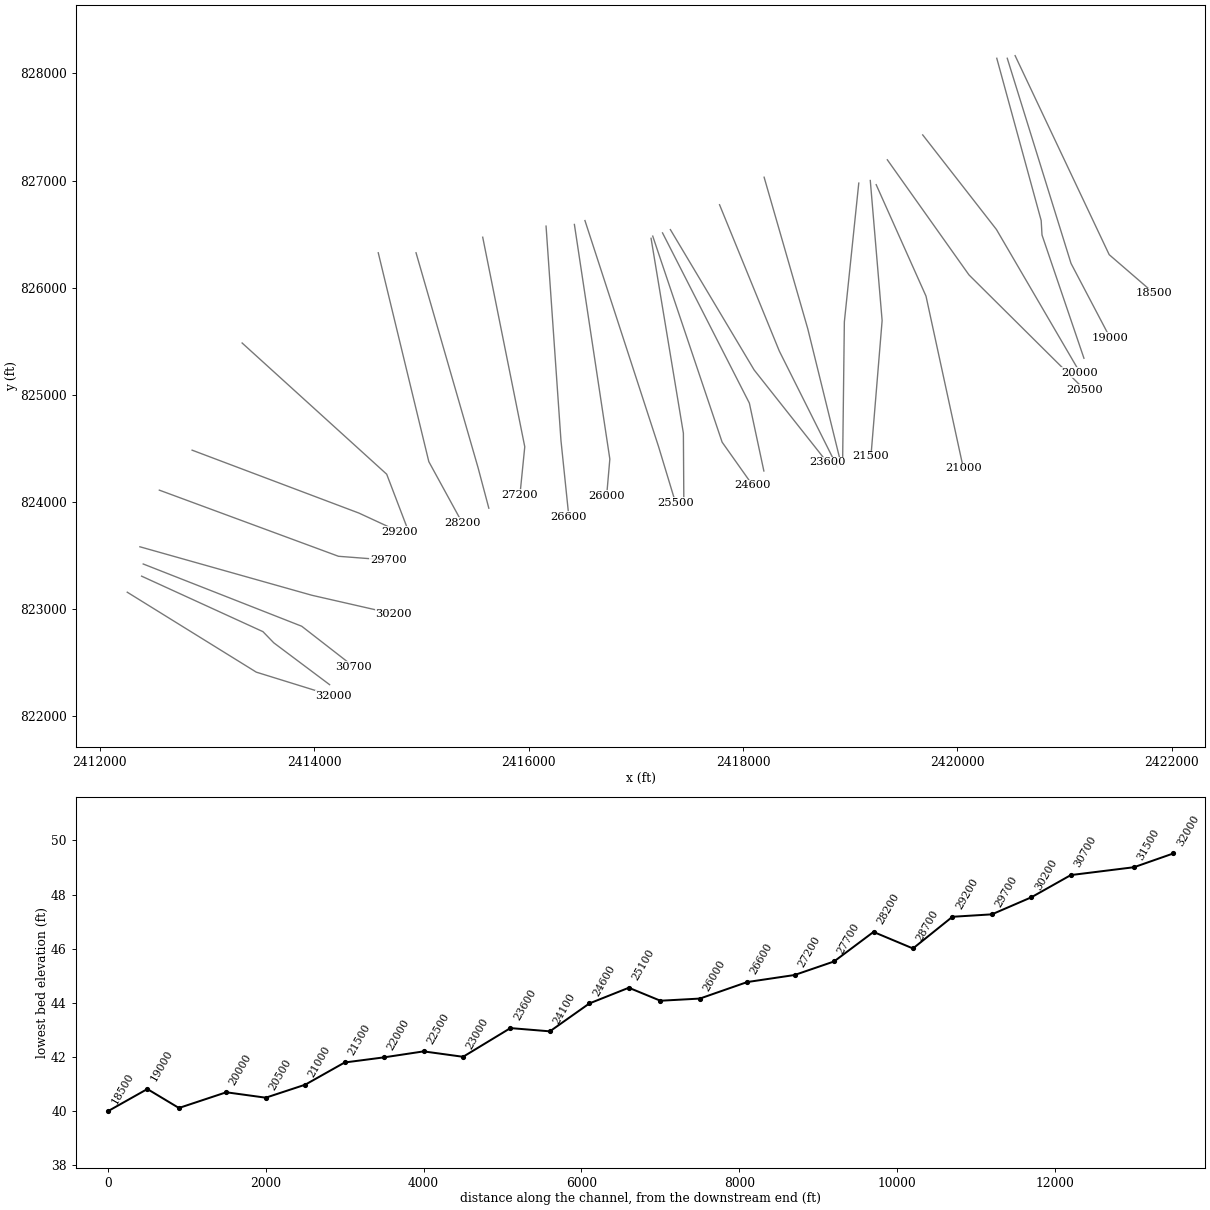
HEC-RAS study WillowCreek.prj: S-21-57 over Willow Creek

--- WillowCreek.g01 (geometry) --- (continued)

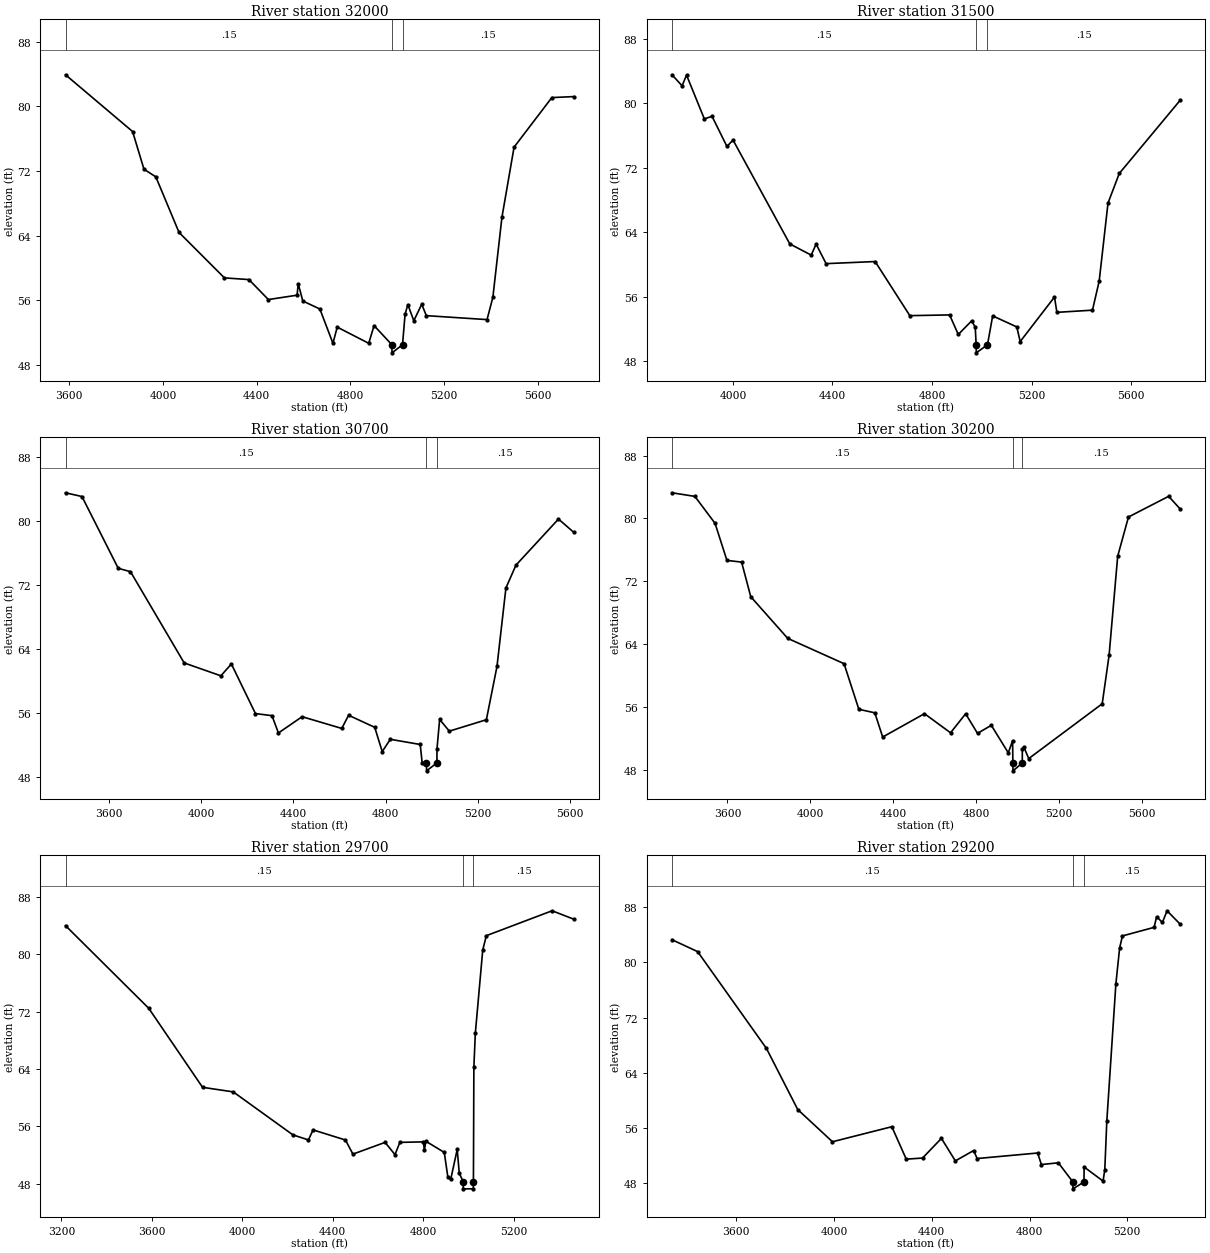
Type RM Length L Ch R = 1 ,32000   ,500,500,500
BEGIN DESCRIPTION:
Willow Creek 58.0
END DESCRIPTION:
XS GIS Cut Line= 3
      2412255.73       823157.51      2413459.57        822411.2
      2414178.76       822188.12
#Sta/Elev= 30
  3583.6   83.91  3870.1   76.89  3918.6   72.23  3969.2   71.29  4068.4   64.41
  4262.2   58.79  4366.9   58.58  4449.8   56.11  4572.5   56.65  4577.4   58.07
  4596.9   55.93  4669.8   54.94  4725.6    50.7  4743.9    52.7  4878.4    50.7
  4901.2   52.89  4977.3   50.52  4977.8   49.52  5022.7   50.52  5033.6    54.3
  5045.5   55.48  5070.9   53.49  5104.7   55.53  5124.4   54.12  5383.6   53.63
  5408.5   56.39  5447.2   66.28    5499   74.96  5660.3   81.09    5753   81.21
#Mann= 3 ,-1,0
  3583.6     .15       0  4977.3     .05       0  5022.7     .15       0
Bank Sta=4977.3,5022.7
XS Rating Curve= 0 ,0
Exp/Cntr=0.3,0.1

Type RM Length L Ch R = 1 ,31500   ,800,800,800
BEGIN DESCRIPTION:
Willow Creek 57.0
END DESCRIPTION:
XS GIS Cut Line= 4
      2412389.67       823307.29      2413521.49       822789.36
       2413622.7        822684.9      2414143.34       822294.49
#Sta/Elev= 30
  3755.3   83.55    3796   82.18  3813.8   83.51  3885.3   78.07  3916.2   78.39
  3976.1   74.65  4000.6   75.44  4228.7   62.54  4314.6   61.15  4334.4   62.52
  4374.4   60.09  4571.5   60.35  4710.8   53.63  4870.6   53.72  4905.5   51.29
  4959.1   52.98  4973.6   52.21  4977.3   50.01  4977.8   49.01  5022.7   50.01
  5043.6    53.6  5140.4   52.23  5154.2   50.41  5291.9   55.94  5301.6   54.04
  5444.5   54.31  5471.5   57.92  5506.9   67.61  5552.2   71.29  5796.2   80.36
#Mann= 3 ,-1,0
  3755.3     .15       0  4977.3     .05       0  5022.7     .15       0
Bank Sta=4977.3,5022.7
XS Rating Curve= 0 ,0
Exp/Cntr=0.3,0.1

Type RM Length L Ch R = 1 ,30700   ,500,500,500
BEGIN DESCRIPTION:
Willow Creek 56.0
END DESCRIPTION:
XS GIS Cut Line= 3
       2412404.6       823420.95      2413883.29       822839.77
      2414369.11       822462.02
#Sta/Elev= 30
  3411.2   83.54  3482.6   83.07    3640   74.08  3693.1   73.66  3926.1   62.23
  4085.3   60.62  4130.9    62.1  4235.3   55.89    4307   55.63  4334.9   53.46
  4437.8    55.5  4609.8   54.03  4639.4   55.68  4752.8   54.17  4785.3   51.13
  4820.4   52.67  4950.2   52.02  4958.5   49.75  4977.3   49.72  4977.8   48.72
  5022.7   49.72  5022.9   51.46  5034.4   55.16  5076.5   53.69  5237.2   55.12
  5283.2   61.79    5322   71.62  5365.6   74.48  5550.1   80.25  5615.4   78.61
#Mann= 3 ,-1,0
  3411.2     .15       0  4977.3     .05       0  5022.7     .15       0
Bank Sta=4977.3,5022.7
XS Rating Curve= 0 ,0
Exp/Cntr=0.3,0.1

Type RM Length L Ch R = 1 ,30200   ,500,500,500
BEGIN DESCRIPTION:
Willow Creek 55.0
END DESCRIPTION:
XS GIS Cut Line= 3
      2412373.54       823581.62      2413978.31       823128.92
      2414742.34       822954.43
#Sta/Elev= 30
  3332.6   83.27  3443.1   82.81  3540.5   79.38  3597.7   74.67  3668.5   74.45
  3712.7   70.05  3891.1   64.75  4162.8   61.53  4234.2   55.73  4311.2   55.28
  4349.2    52.2  4550.8   55.17  4676.6   52.74  4749.4   55.16  4806.7   52.67
  4873.3   53.69  4955.2   50.19    4976   51.74  4977.3    48.9  4977.8    47.9
  5022.7    48.9    5023   50.68  5029.9   50.95  5053.8   49.46  5408.3   56.43
  5441.5   62.59    5483    75.2    5535   80.19  5728.9   82.82  5783.7   81.23
#Mann= 3 ,-1,0
  3332.6     .15       0  4977.3     .05       0  5022.7     .15       0
Bank Sta=4977.3,5022.7
XS Rating Curve= 0 ,0
Exp/Cntr=0.3,0.1

Type RM Length L Ch R = 1 ,29700   ,500,500,500
BEGIN DESCRIPTION:
Willow Creek 54.0
END DESCRIPTION:
XS GIS Cut Line= 3
      2412554.96       824110.32      2414226.25       823492.89
      2414690.49       823457.22
#Sta/Elev= 30
  3218.3   83.98  3586.5   72.45  3824.5   61.43  3960.4   60.79    4224    54.8
  4292.8   54.09  4313.3   55.49  4456.7   54.08  4489.6   52.11    4632   53.75
  4675.7   52.04  4697.3   53.75  4801.4   53.82  4805.7   52.64  4812.2   53.91
  4893.8   52.35  4909.5   48.93  4922.2   48.58    4951   52.77    4960   49.46
  4977.3   48.27  4977.8   47.27  5022.2   47.27  5022.7   48.27  5024.7   64.27
  5031.1   68.95  5063.9   80.58    5080   82.58  5370.7   86.05  5465.6   84.89
#Mann= 3 ,-1,0
  3218.3     .15       0  4977.3     .05       0  5022.7     .15       0
Bank Sta=4977.3,5022.7
XS Rating Curve= 0 ,0
Exp/Cntr=0.3,0.1

Type RM Length L Ch R = 1 ,29200   ,500,500,500
BEGIN DESCRIPTION:
Willow Creek 53.0
END DESCRIPTION:
XS GIS Cut Line= 3
      2412860.75       824483.53      2414416.81       823896.24
      2414794.14       823721.58
#Sta/Elev= 30
  3336.8   83.27  3441.9   81.54  3723.4   67.52  3851.4   58.67  3993.6      54
  4236.5   56.18  4295.5   51.48  4362.2   51.64  4439.4   54.49  4496.4   51.23
  4571.4   52.73  4585.5   51.57  4833.2   52.37  4848.5    50.7    4918   50.95
  4977.3   48.18  4977.8   47.18  5022.7   48.18  5023.5   50.34    5101    48.3
    5108   49.97  5116.2   56.97  5153.4    76.9  5168.7   82.08  5180.3   83.82
  5309.9   85.06    5320    86.6  5343.8   85.77  5362.8   87.46  5415.8   85.54
#Mann= 3 ,-1,0
  3336.8     .15       0  4977.3     .05       0  5022.7     .15       0
Bank Sta=4977.3,5022.7
XS Rating Curve= 0 ,0
Exp/Cntr=0.3,0.1

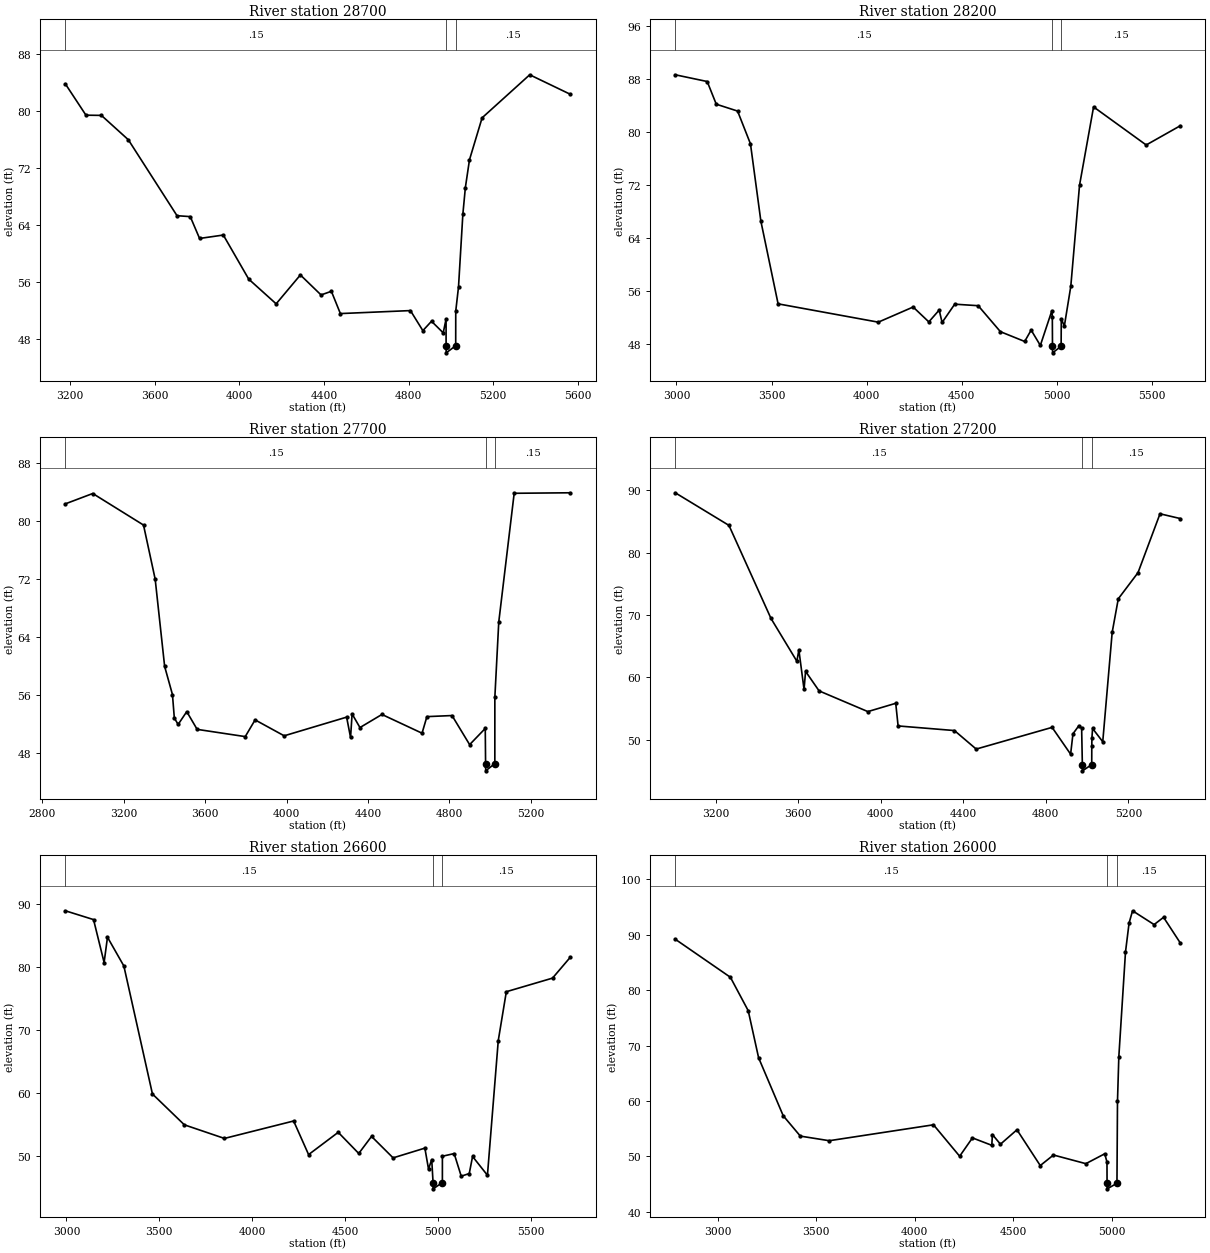
Type RM Length L Ch R = 1 ,28700   ,500,500,500
BEGIN DESCRIPTION:
Willow Creek 52.0
END DESCRIPTION:
XS GIS Cut Line= 3
      2413327.25       825483.92      2414675.99       824258.94
      2414877.09       823731.91
#Sta/Elev= 30
    3178   83.82  3275.4   79.42  3348.4   79.39  3475.5   75.97  3705.7   65.29
  3768.3   65.16  3812.3   62.09  3924.5   62.57  4044.6   56.37  4174.2    52.9
  4288.7   56.96  4386.3   54.15  4435.2   54.66  4477.7   51.53  4808.8   51.95
  4867.5   49.13  4908.4   50.45  4963.7   48.82  4977.2   50.76  4977.3   47.01
  4977.8   46.01  5022.7   47.01  5022.9   51.87    5036   55.29  5056.5   65.49
  5068.4   69.25  5087.9   73.16  5147.5   79.05  5372.5    85.1  5564.1   82.36
#Mann= 3 ,-1,0
    3178     .15       0  4977.3     .05       0  5022.7     .15       0
Bank Sta=4977.3,5022.7
XS Rating Curve= 0 ,0
Exp/Cntr=0.3,0.1

Type RM Length L Ch R = 1 ,28200   ,500,500,500
BEGIN DESCRIPTION:
Willow Creek 51.0
END DESCRIPTION:
XS GIS Cut Line= 3
      2414597.18       826326.18      2415068.91       824376.34
      2415379.85       823807.13
#Sta/Elev= 30
  2993.9   88.68  3161.9   87.66  3209.5   84.23  3321.6   83.19  3389.4   78.23
  3443.9   66.56  3534.6   54.03  4061.5   51.26  4244.6   53.55  4327.1    51.3
  4381.6   53.09  4396.9   51.21  4463.2   53.98  4586.7   53.75  4703.5   49.82
    4831   48.34  4865.1   50.06  4913.4   47.74    4974   52.99  4976.4   52.11
  4977.3   47.62  4977.8   46.62  5022.7   47.62  5023.5   51.78  5039.6   50.66
  5073.5   56.67  5119.5   71.98  5193.3   83.82    5470   78.06  5648.6   80.96
#Mann= 3 ,-1,0
  2993.9     .15       0  4977.3     .05       0  5022.7     .15       0
Bank Sta=4977.3,5022.7
XS Rating Curve= 0 ,0
Exp/Cntr=0.3,0.1

Type RM Length L Ch R = 1 ,27700   ,500,500,500
BEGIN DESCRIPTION:
Willow Creek 50.0
END DESCRIPTION:
XS GIS Cut Line= 3
      2414949.66       826326.17      2415527.76       824321.78
      2415628.67       823941.85
#Sta/Elev= 30
  2913.9   82.42  3048.5   83.85  3297.7   79.49    3355   72.01  3401.4   59.96
  3439.8   56.07    3449   52.82  3467.7   51.94    3510   53.71    3561   51.26
  3797.2   50.26  3845.6   52.57  3988.4   50.37    4295   52.95  4314.3   50.14
  4321.9   53.39  4360.4   51.51  4468.4   53.32  4665.3   50.73  4689.2   53.02
  4812.5   53.17    4899   49.15  4975.7   51.39  4977.3   46.53  4977.8   45.53
  5022.7   46.53  5022.8   55.69    5042   66.09  5117.7   83.88  5393.1   83.95
#Mann= 3 ,-1,0
  2913.9     .15       0  4977.3     .05       0  5022.7     .15       0
Bank Sta=4977.3,5022.7
XS Rating Curve= 0 ,0
Exp/Cntr=0.3,0.1

Type RM Length L Ch R = 1 ,27200   ,600,600,600
BEGIN DESCRIPTION:
Willow Creek 49.0
END DESCRIPTION:
XS GIS Cut Line= 3
      2415571.64       826471.38      2415963.99       824515.24
      2415918.94       824066.29
#Sta/Elev= 30
  3004.9   89.62  3265.1   84.39  3468.7   69.47  3594.2    62.6  3603.8   64.43
  3628.9   58.09  3636.3   60.98  3701.8   57.85    3938   54.53  4073.1   55.86
  4084.6   52.23  4357.5   51.49    4463   48.52  4830.7      52  4920.4    47.7
  4931.8   50.97  4960.6   52.28  4973.8   51.88  4977.3   46.03  4977.8   45.03
  5022.7   46.03    5023   49.04  5023.7   50.33  5026.8   51.82  5076.1    49.7
  5121.8   67.24  5151.4   72.62  5246.9   76.81  5353.5   86.25  5451.2   85.49
#Mann= 3 ,-1,0
  3004.9     .15       0  4977.3     .05       0  5022.7     .15       0
Bank Sta=4977.3,5022.7
XS Rating Curve= 0 ,0
Exp/Cntr=0.3,0.1

Type RM Length L Ch R = 1 ,26600   ,600,600,600
BEGIN DESCRIPTION:
Willow Creek 48.0
END DESCRIPTION:
XS GIS Cut Line= 3
      2416162.55       826574.98      2416301.63       824574.21
      2416375.07        823864.1
#Sta/Elev= 30
  2994.4   88.95  3146.2   87.55  3203.2   80.73  3221.3   84.75  3309.5   80.18
  3463.5   59.84  3635.4   54.94  3851.3   52.78  4223.9   55.55  4304.5   50.21
  4464.1   53.75  4574.7   50.39  4643.5    53.1  4759.7   49.69  4930.8   51.24
  4950.5   47.91  4967.7   49.43  4974.9   45.77  4975.4   44.77  5025.1   45.77
  5025.2   49.95  5088.6   50.37  5126.6   46.78  5169.8    47.2  5187.7   49.91
  5267.8   46.93  5326.1   68.33  5369.5   76.09  5618.3   78.25  5713.9   81.56
#Mann= 3 ,-1,0
  2994.4     .15       0  4974.9     .05       0  5025.1     .15       0
Bank Sta=4974.9,5025.1
XS Rating Curve= 0 ,0
Exp/Cntr=0.3,0.1

Type RM Length L Ch R = 1 ,26000   ,500,500,500
BEGIN DESCRIPTION:
Willow Creek 47.0
END DESCRIPTION:
XS GIS Cut Line= 3
      2416426.91       826590.54      2416757.61       824400.26
      2416727.54       824055.87
#Sta/Elev= 30
  2784.9   89.18  3064.5   82.32    3155   76.29  3207.7   67.79  3332.5   57.34
  3419.3   53.67    3566   52.84  4094.6   55.71  4227.3   50.04  4292.1   53.35
  4390.3   52.01  4393.5   53.95  4434.2   52.21  4517.9   54.81  4636.1   48.36
  4703.1   50.26  4867.4    48.7    4963   50.48  4974.5      49  4974.9   45.16
  4975.4   44.16  5025.1   45.16  5027.8   59.96  5034.6      68  5068.4   86.87
  5086.6    92.1  5104.2   94.31  5213.5   91.82  5261.5   93.13  5345.7   88.54
#Mann= 3 ,-1,0
  2784.9     .15       0  4974.9     .05       0  5025.1     .15       0
Bank Sta=4974.9,5025.1
XS Rating Curve= 0 ,0
Exp/Cntr=0.3,0.1

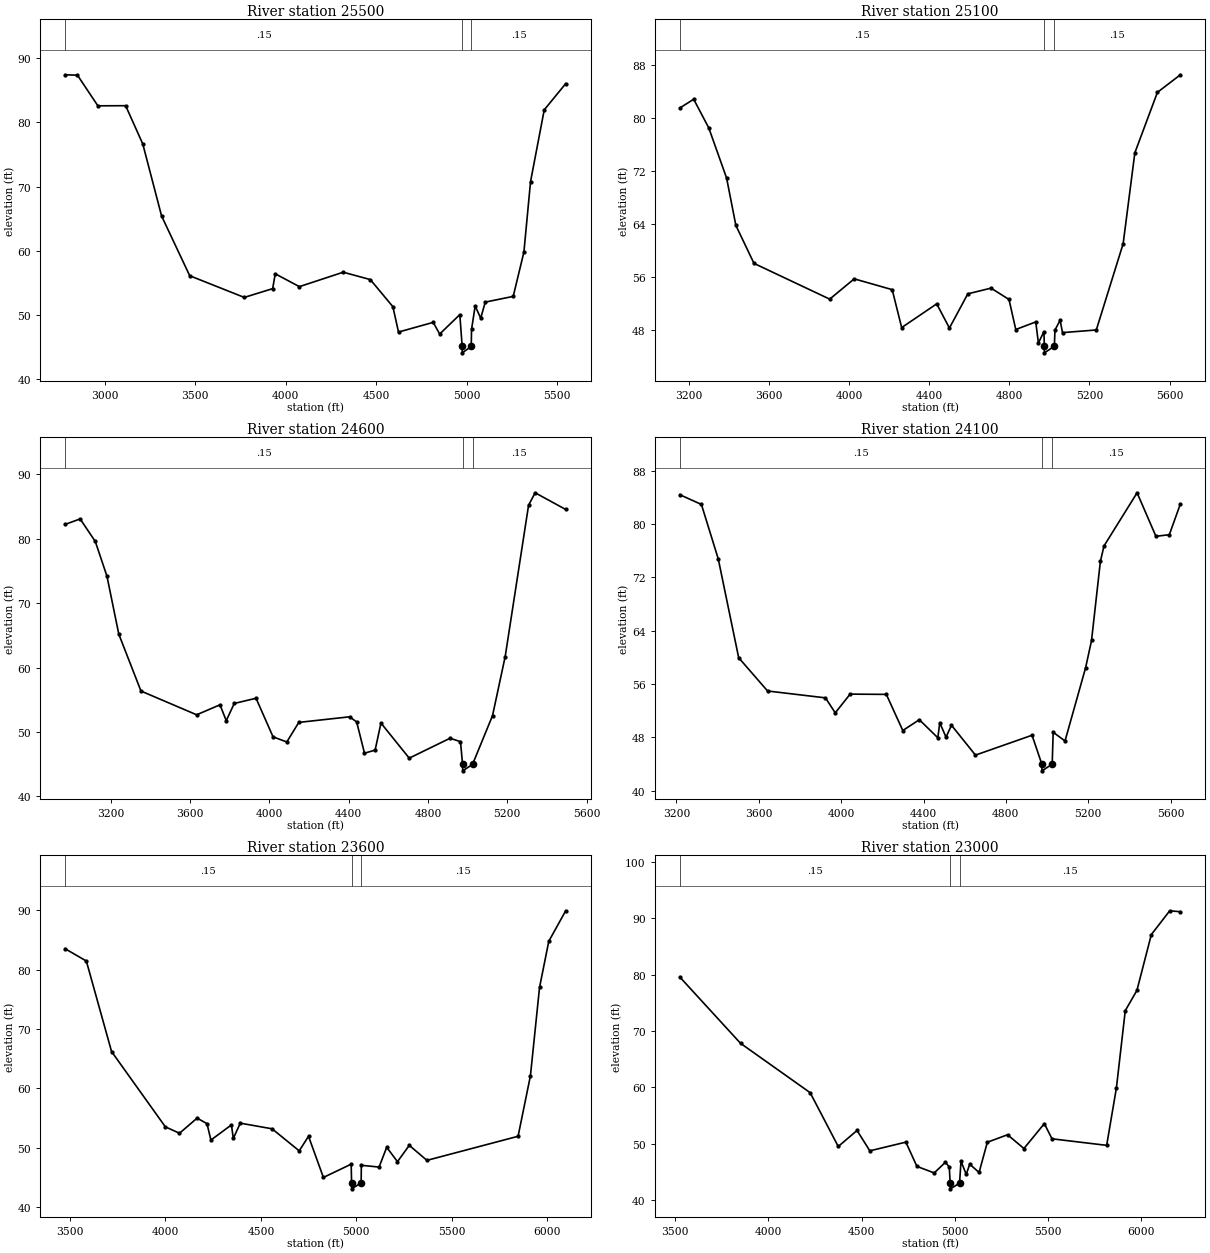
Type RM Length L Ch R = 1 ,25500   ,400,400,400
BEGIN DESCRIPTION:
Willow Creek 46.0
END DESCRIPTION:
XS GIS Cut Line= 3
      2416525.39       826626.84      2417211.88       824517.23
      2417370.26       823993.76
#Sta/Elev= 30
  2781.5   87.43  2849.5   87.37  2962.4   82.59  3115.8   82.61  3210.4   76.65
  3314.4   65.41  3469.8    56.1  3771.2   52.72  3927.9   54.09  3942.4    56.4
  4075.6    54.4  4317.8   56.65  4467.5    55.5  4592.1   51.28  4623.2   47.32
  4814.9   48.83  4850.7   47.01    4962   50.04  4974.9   45.08  4975.4   44.08
  5025.1   45.08  5026.7   47.73  5046.8   51.39  5077.4   49.48  5102.5   51.99
  5256.9   52.88    5316   59.79  5352.7   70.78  5428.3   81.96  5546.9   86.05
#Mann= 3 ,-1,0
  2781.5     .15       0  4974.9     .05       0  5025.1     .15       0
Bank Sta=4974.9,5025.1
XS Rating Curve= 0 ,0
Exp/Cntr=0.3,0.1

Type RM Length L Ch R = 1 ,25100   ,500,500,500
BEGIN DESCRIPTION:
Willow Creek 45.0
END DESCRIPTION:
XS GIS Cut Line= 3
      2417142.21       826460.99      2417443.64       824642.19
      2417448.03       823988.51
#Sta/Elev= 30
  3156.4   81.49  3225.6   82.81  3300.8   78.49  3389.8   70.92    3436   63.78
  3526.5   58.05  3904.2   52.66  4026.5   55.72  4215.9   54.09  4263.2   48.37
    4438   51.95  4501.4    48.3  4593.2   53.46  4708.9   54.32  4798.7   52.61
  4832.4   48.08  4932.1   49.22  4945.4   46.05    4973   47.76  4974.9   45.56
  4975.4   44.56  5025.1   45.56  5027.9   47.99  5053.6   49.48  5065.6   47.61
  5234.2   48.01  5368.2   61.03  5426.5   74.73  5539.1   83.85  5653.7    86.5
#Mann= 3 ,-1,0
  3156.4     .15       0  4974.9     .05       0  5025.1     .15       0
Bank Sta=4974.9,5025.1
XS Rating Curve= 0 ,0
Exp/Cntr=0.3,0.1

Type RM Length L Ch R = 1 ,24600   ,500,500,500
BEGIN DESCRIPTION:
Willow Creek 44.0
END DESCRIPTION:
XS GIS Cut Line= 3
      2417157.76       826481.72      2417804.99        824558.4
      2418090.78       824154.36
#Sta/Elev= 30
  2970.7   82.24  3046.4   83.09  3122.8   79.59  3181.6    74.2  3241.3    65.2
  3353.1   56.37    3634   52.68  3751.5   54.23  3783.2   51.77  3823.5   54.44
  3933.4   55.25  4019.1   49.26  4088.5   48.46    4149    51.5  4405.3   52.37
  4440.8   51.57  4480.3   46.72  4533.9    47.2  4563.3    51.4  4705.9   45.95
  4911.7   49.04  4964.4   48.51  4974.9   44.98  4975.4   43.98  5025.1   44.98
  5125.9   52.55  5189.8   61.73  5307.7   85.21  5340.7   87.15  5494.9   84.56
#Mann= 3 ,-1,0
  2970.7     .15       0  4974.9     .05       0  5025.1     .15       0
Bank Sta=4974.9,5025.1
XS Rating Curve= 0 ,0
Exp/Cntr=0.3,0.1

Type RM Length L Ch R = 1 ,24100   ,500,500,500
BEGIN DESCRIPTION:
Willow Creek 43.0
END DESCRIPTION:
XS GIS Cut Line= 3
      2417249.07       826511.77      2418059.17       824922.64
      2418194.44       824289.12
#Sta/Elev= 30
  3216.3   84.38  3321.2   82.92    3403   74.75  3502.2   59.92  3642.6   54.93
  3923.8    53.9  3971.3   51.65  4043.5   54.46  4219.4   54.42  4299.4      49
  4379.7   50.62  4469.6   47.91    4479   50.16  4509.4      48  4535.9   49.79
  4652.4   45.31  4927.2   48.29  4974.9   43.95  4975.4   42.95  5025.1   43.95
  5029.9   48.74  5087.4   47.43  5187.4   58.42  5216.2   62.51  5259.2   74.37
  5276.7   76.69  5437.5   84.67    5529   78.14  5594.1   78.38  5647.8      83
#Mann= 3 ,-1,0
  3216.3     .15       0  4974.9     .05       0  5025.1     .15       0
Bank Sta=4974.9,5025.1
XS Rating Curve= 0 ,0
Exp/Cntr=0.3,0.1

Type RM Length L Ch R = 1 ,23600   ,600,600,600
BEGIN DESCRIPTION:
Willow Creek 42.0
END DESCRIPTION:
XS GIS Cut Line= 3
      2417322.42       826542.38      2418103.68       825232.23
      2418783.66       824371.91
#Sta/Elev= 30
  3474.6   83.54  3585.7   81.47  3717.8   66.21  3999.6   53.52  4073.6   52.44
  4165.9   54.99  4217.6   54.06  4238.2   51.29  4345.7   53.85  4355.5   51.57
  4392.1   54.14  4558.5   53.19  4700.8   49.47  4749.5   51.93  4827.4   44.99
  4973.1   47.23  4974.9   44.07  4975.4   43.07  5025.1   44.07  5026.2   47.04
    5119   46.74    5159   50.07  5215.4   47.65  5277.3    50.4  5369.7   47.87
  5847.2   51.93  5911.9   62.14  5959.5   77.01    6008    84.8  6096.6   89.94
#Mann= 3 ,-1,0
  3474.6     .15       0  4974.9     .05       0  5025.1     .15       0
Bank Sta=4974.9,5025.1
XS Rating Curve= 0 ,0
Exp/Cntr=0.3,0.1

Type RM Length L Ch R = 1 ,23000   ,500,500,500
BEGIN DESCRIPTION:
Willow Creek 41.0
END DESCRIPTION:
XS GIS Cut Line= 3
      2417780.97       826774.72      2418338.57       825408.64
      2418879.83       824326.67
#Sta/Elev= 30
  3524.5   79.56  3850.3   67.81  4223.7   59.06  4374.4   49.52  4475.2   52.36
  4543.8   48.75  4737.2   50.29  4796.4   45.99  4889.1   44.83  4949.7   46.73
    4970   45.86  4974.9   43.01  4975.4   42.01  5025.1   43.01  5032.9    46.9
    5061   44.58  5079.8   46.38  5129.9   44.91  5174.1   50.27  5282.6    51.6
  5370.5   49.16  5479.9   53.57  5521.1   50.88  5814.3   49.72  5866.6    59.9
  5914.1    73.6  5976.7    77.2  6053.9   87.09  6152.7   91.31  6209.8   91.14
#Mann= 3 ,-1,0
  3524.5     .15       0  4974.9     .05       0  5025.1     .15       0
Bank Sta=4974.9,5025.1
XS Rating Curve= 0 ,0
Exp/Cntr=0.3,0.1

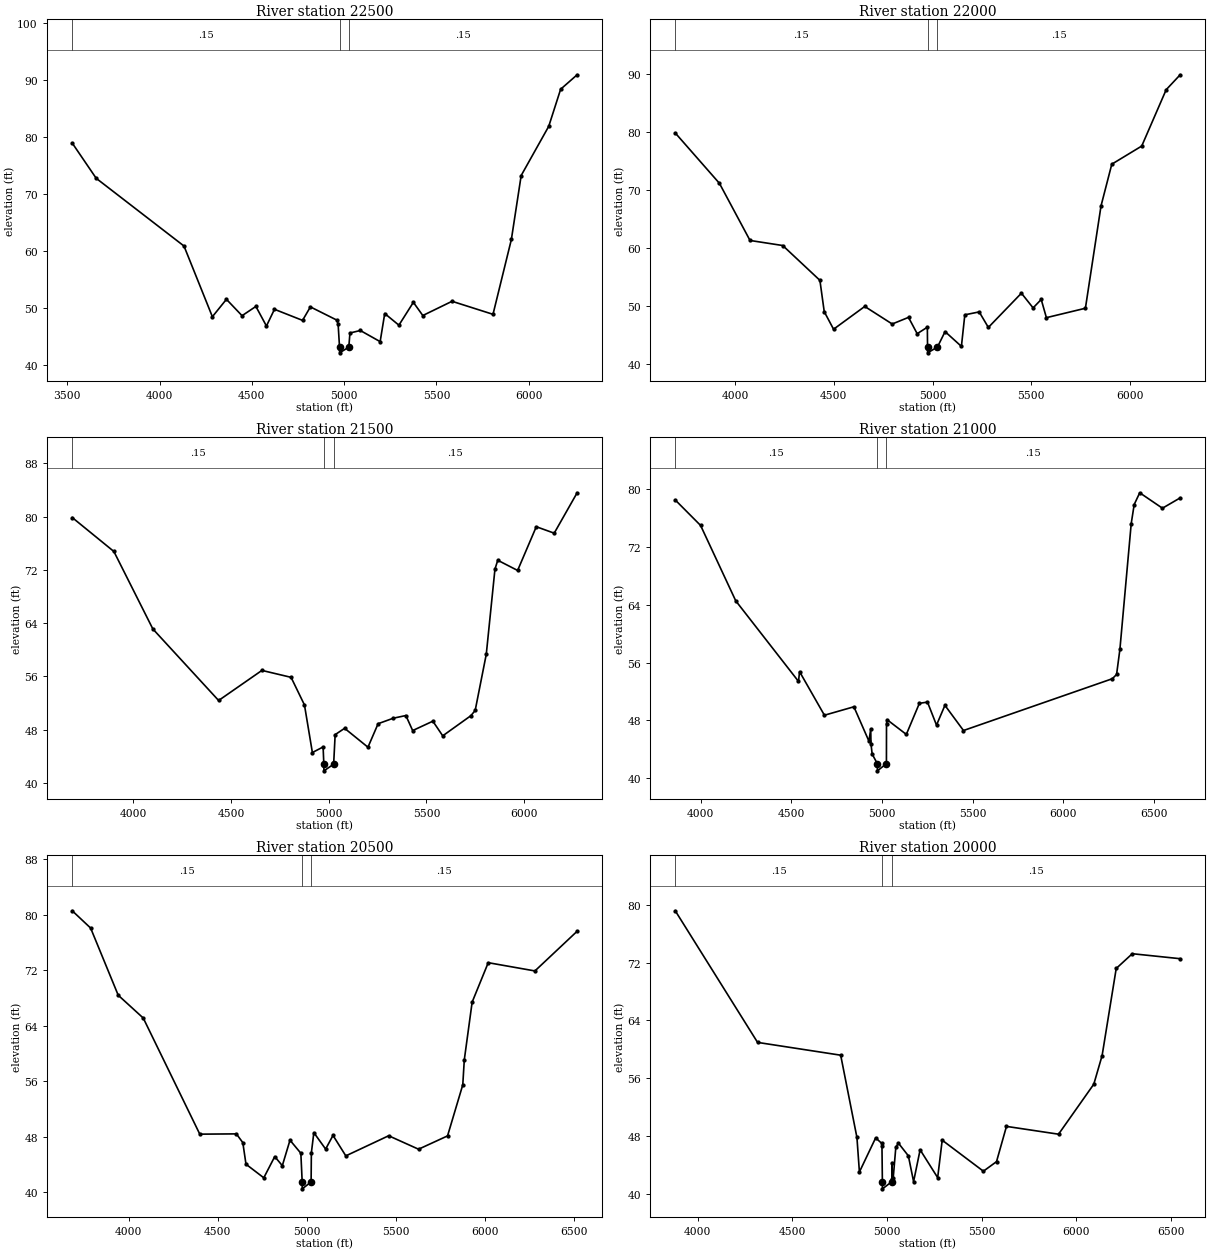
Type RM Length L Ch R = 1 ,22500   ,500,500,500
BEGIN DESCRIPTION:
Willow Creek 40.0
END DESCRIPTION:
XS GIS Cut Line= 3
      2418196.73       827031.51      2418604.23       825615.79
      2418905.97       824390.19
#Sta/Elev= 30
  3526.8   78.92  3656.8   72.75  4132.3    60.9  4286.1   48.53  4362.2   51.58
  4446.8   48.71  4521.8   50.33    4579    46.9  4622.4   49.83  4774.6   47.89
  4817.1   50.25  4959.5   47.95  4967.2    47.3  4974.9   43.21  4975.4   42.21
  5025.1   43.21  5031.4   45.68  5087.5   46.12    5195   44.17  5219.8   49.09
  5296.6   47.05  5374.9   51.05  5426.1   48.74  5584.5   51.23  5806.4   48.95
  5905.9   62.05    5959   73.24  6108.3   81.85  6172.8   88.34  6262.2   90.87
#Mann= 3 ,-1,0
  3526.8     .15       0  4974.9     .05       0  5025.1     .15       0
Bank Sta=4974.9,5025.1
XS Rating Curve= 0 ,0
Exp/Cntr=0.3,0.1

Type RM Length L Ch R = 1 ,22000   ,500,500,500
BEGIN DESCRIPTION:
Willow Creek 39.0
END DESCRIPTION:
XS GIS Cut Line= 3
      2419079.84        826976.7       2418945.3       825680.86
      2418929.84       824426.66
#Sta/Elev= 30
  3697.2   79.81  3920.9   71.15  4075.9   61.32  4241.5   60.45  4429.8   54.46
  4451.7   49.07    4499   46.05  4656.9   49.97  4795.9   46.95  4878.5   48.09
  4922.4   45.28  4973.9    46.4  4974.9   42.99  4975.4   41.99  5025.1   42.99
  5063.7   45.64  5146.4    43.1  5163.7   48.53  5236.5   49.03  5282.9   46.36
  5450.3   52.25  5509.5   49.72  5550.6   51.17  5576.8   48.04  5774.4   49.66
  5853.5   67.27    5908   74.44  6059.6   77.56  6183.4   87.25  6254.3   89.82
#Mann= 3 ,-1,0
  3697.2     .15       0  4974.9     .05       0  5025.1     .15       0
Bank Sta=4974.9,5025.1
XS Rating Curve= 0 ,0
Exp/Cntr=0.3,0.1

Type RM Length L Ch R = 1 ,21500   ,500,500,500
BEGIN DESCRIPTION:
Willow Creek 38.0
END DESCRIPTION:
XS GIS Cut Line= 3
      2419187.21       827000.88      2419297.66       825693.34
      2419193.32       824426.93
#Sta/Elev= 30
  3687.8   79.86  3900.9   74.76  4100.2   63.12  4436.7   52.37  4658.2   56.89
  4807.3   55.85  4875.8    51.7  4916.3   44.55  4971.2   45.39  4974.9    42.8
  4975.4    41.8  5025.1    42.8  5032.8   47.24  5081.2   48.19  5200.6   45.35
  5252.5   48.88  5330.4   49.71  5394.6   50.11  5429.3   47.85  5532.6   49.26
  5583.1   47.06  5726.8   50.08  5749.1   50.87  5805.9   59.32  5850.3   72.11
  5864.6   73.44  5966.2   71.91  6061.7   78.48  6153.4   77.51  6270.7   83.58
#Mann= 3 ,-1,0
  3687.8     .15       0  4974.9     .05       0  5025.1     .15       0
Bank Sta=4974.9,5025.1
XS Rating Curve= 0 ,0
Exp/Cntr=0.3,0.1

Type RM Length L Ch R = 1 ,21000   ,500,500,500
BEGIN DESCRIPTION:
Willow Creek 37.0
END DESCRIPTION:
XS GIS Cut Line= 3
      2419242.24       826961.78      2419706.95       825921.67
       2420055.4       824314.41
#Sta/Elev= 30
  3860.8   78.53  4000.5      75  4194.3   64.55  4540.3   53.38  4546.2   54.73
  4683.2   48.69  4845.7   49.86  4928.7   45.09  4938.6   46.79  4939.9   44.72
  4946.5    43.3  4974.9   41.98  4975.4   40.98  5025.1   41.98  5025.5   47.51
  5028.2   48.08  5134.8   46.03  5206.8   50.34  5251.4   50.51  5301.2   47.32
  5347.6   50.06  5449.9   46.57  6270.5   53.75    6294   54.34  6312.3   57.82
  6374.7   75.26  6391.1    77.9  6421.6   79.53  6546.8   77.39  6644.6   78.82
#Mann= 3 ,-1,0
  3860.8     .15       0  4974.9     .05       0  5025.1     .15       0
Bank Sta=4974.9,5025.1
XS Rating Curve= 0 ,0
Exp/Cntr=0.3,0.1

Type RM Length L Ch R = 1 ,20500   ,500,500,500
BEGIN DESCRIPTION:
Willow Creek 36.0
END DESCRIPTION:
XS GIS Cut Line= 3
      2419346.15       827194.16      2420108.03       826119.42
      2421186.47       825048.12
#Sta/Elev= 30
  3682.6   80.57    3786   78.08  3941.1    68.4  4081.8   65.11  4399.5   48.38
  4605.1   48.42  4641.3   47.16  4659.1   44.05  4759.1   42.09  4820.7   45.15
  4863.3   43.84  4906.4   47.51  4967.4   45.63  4974.9    41.5  4975.4    40.5
  5025.1    41.5  5026.5   45.69  5040.4    48.6  5106.7   46.23  5148.1    48.2
  5220.1   45.25  5460.9   48.15  5628.9   46.21  5791.8   48.13  5877.4   55.49
  5885.9   59.08  5930.1   67.41  6020.5   73.09  6282.8    71.9  6520.1   77.62
#Mann= 3 ,-1,0
  3682.6     .15       0  4974.9     .05       0  5025.1     .15       0
Bank Sta=4974.9,5025.1
XS Rating Curve= 0 ,0
Exp/Cntr=0.3,0.1

Type RM Length L Ch R = 1 ,20000   ,600,600,600
BEGIN DESCRIPTION:
Willow Creek 35.0
END DESCRIPTION:
XS GIS Cut Line= 3
      2419676.32       827426.47      2420363.93       826543.79
      2421143.68        825207.1
#Sta/Elev= 30
  3881.1   79.17  4315.8   60.96  4754.7   59.19  4840.5   47.81  4853.6   43.03
  4939.4   47.75  4971.1      47  4972.7   46.64  4974.9    41.7  4975.4    40.7
  5025.1    41.7  5025.3   44.33    5026   42.06  5032.2   42.24    5046   46.48
    5060   47.01  5112.1   45.27  5139.7    41.7  5174.2    46.1  5266.9   42.25
  5290.8   47.43  5508.3   43.14  5577.6   44.46  5630.2   49.34  5905.2   48.26
  6091.4   55.18  6135.3   59.14  6209.8   71.19  6294.7   73.23  6547.5   72.54
#Mann= 3 ,-1,0
  3881.1     .15       0  4974.9     .05       0  5025.1     .15       0
Bank Sta=4974.9,5025.1
XS Rating Curve= 0 ,0
Exp/Cntr=0.3,0.1

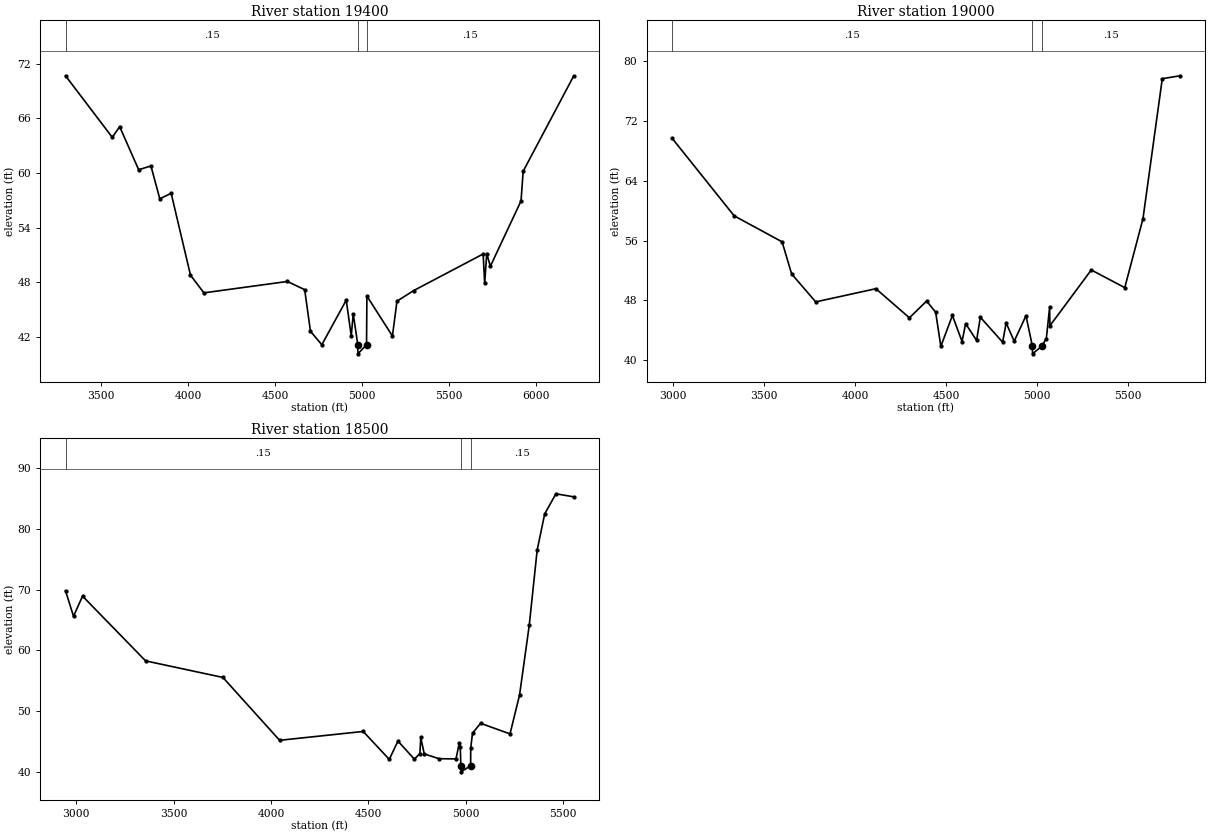
Type RM Length L Ch R = 1 ,19400   ,400,400,400
BEGIN DESCRIPTION:
Willow Creek 34.0
END DESCRIPTION:
XS GIS Cut Line= 4
      2420367.23       828141.77      2420781.44       826626.71
      2420789.18       826492.09      2421180.38       825341.58
#Sta/Elev= 30
  3294.5   70.67  3563.3   63.91    3606   65.08    3715   60.35  3785.7   60.76
  3836.5   57.15  3901.9   57.76  4012.9   48.77    4090   46.82    4570   48.07
  4669.6   47.17  4702.7    42.6    4768   41.12  4908.5   46.02  4937.2   42.09
  4948.7   44.51  4974.9   41.12  4975.4   40.12  5025.1   41.12  5027.2   46.47
  5173.9   42.08  5200.1   45.91  5296.1   47.07  5695.5   51.09  5704.3   47.87
  5716.1   51.14  5736.9   49.74  5913.3   56.92  5925.6   60.18  6215.2   70.62
#Mann= 3 ,-1,0
  3294.5     .15       0  4974.9     .05       0  5025.1     .15       0
Bank Sta=4974.9,5025.1
XS Rating Curve= 0 ,0
Exp/Cntr=0.3,0.1

Type RM Length L Ch R = 1 ,19000   ,500,500,500
BEGIN DESCRIPTION:
Willow Creek 33.0
END DESCRIPTION:
XS GIS Cut Line= 3
      2420465.03       828141.84      2421059.84       826226.78
      2421424.96       825531.08
#Sta/Elev= 30
  2994.7   69.73  3336.4   59.31  3599.7   55.83    3652   51.53  3784.3   47.78
    4115   49.55    4299   45.65  4393.6   47.89  4443.2   46.41  4471.8   41.82
  4535.3   45.96  4588.3   42.47  4607.8   44.86  4668.2   42.62  4688.6   45.73
  4811.3   42.38  4830.5   44.96  4874.7   42.51  4939.5   45.93  4974.9   41.82
  4975.4   40.82  5025.1   41.82  5051.3   42.86  5069.3   47.04  5071.1   44.59
  5298.3   52.06  5482.2   49.69  5582.1   58.91  5688.3   77.69  5785.7   78.08
#Mann= 3 ,-1,0
  2994.7     .15       0  4974.9     .05       0  5025.1     .15       0
Bank Sta=4974.9,5025.1
XS Rating Curve= 0 ,0
Exp/Cntr=0.3,0.1

Type RM Length L Ch R = 1 ,18500   ,500,500,500
BEGIN DESCRIPTION:
Willow Creek 32.0
END DESCRIPTION:
XS GIS Cut Line= 3
      2420538.39        828166.3      2421415.78       826308.57
       2421834.6       825946.85
#Sta/Elev= 30
  2945.5   69.82  2986.6   65.61    3033   68.93  3356.5   58.27  3753.5   55.54
  4044.6   45.19  4473.5   46.65  4607.5   42.05  4652.1   45.06  4736.3   42.09
  4764.7   43.01  4769.1   45.66    4787   42.95  4863.5   42.16  4949.9   42.13
  4966.6   44.69    4972   44.09  4974.9      41  4975.4      40  5025.1      41
  5025.6   43.93  5034.7   46.36  5076.2   47.99  5227.3   46.25  5276.2   52.64
  5325.9    64.1  5366.6   76.49  5405.3   82.47  5462.9   85.78  5553.4   85.28
#Mann= 3 ,-1,0
  2945.5     .15       0  4974.9     .05       0  5025.1     .15       0
Bank Sta=4974.9,5025.1
XS Rating Curve= 0 ,0
Exp/Cntr=0.3,0.1