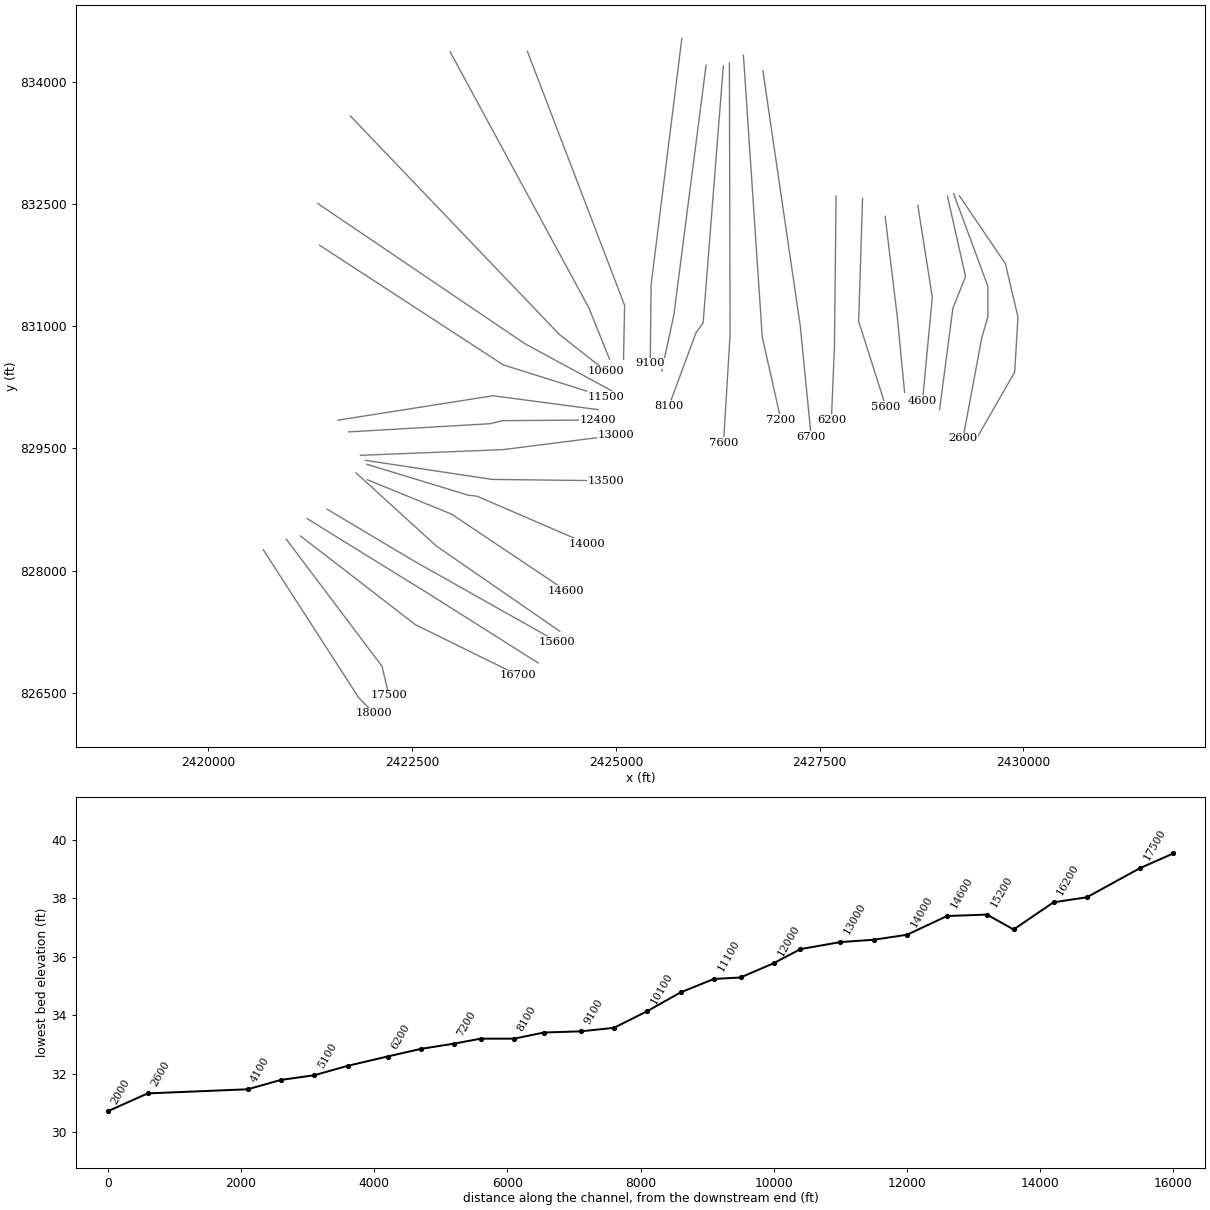
HEC-RAS study WillowCreek.prj: S-21-57 over Willow Creek

--- WillowCreek.g01 (geometry) --- (continued)

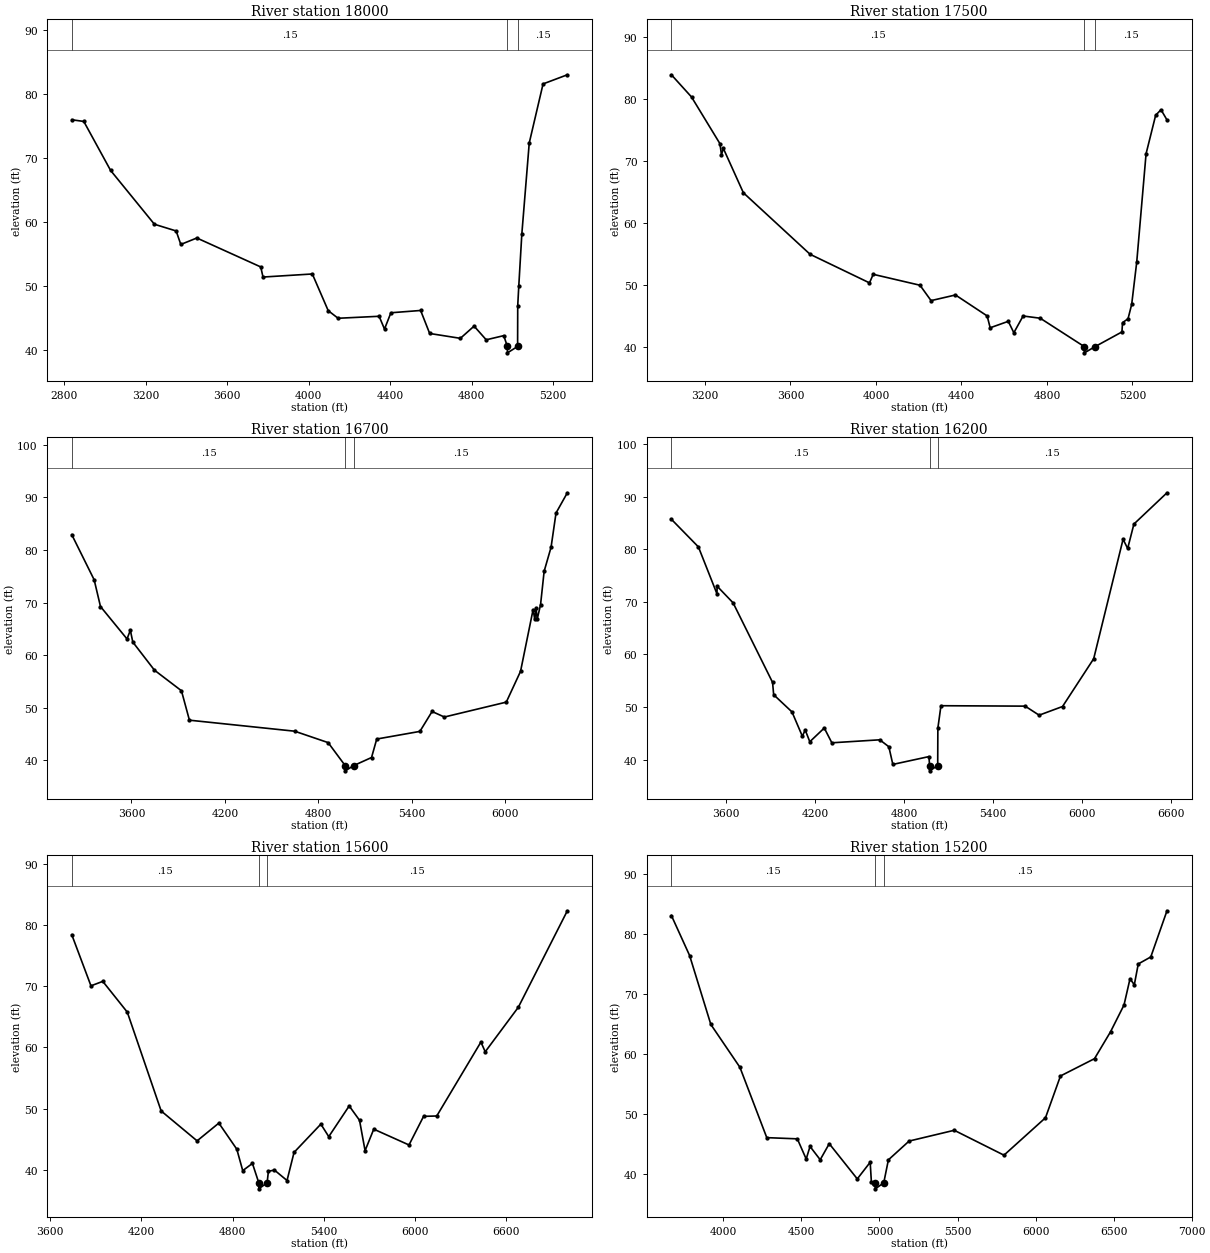
Type RM Length L Ch R = 1 ,18000   ,500,500,500
BEGIN DESCRIPTION:
Willow Creek 31.0
END DESCRIPTION:
XS GIS Cut Line= 3
      2420672.91       828257.98      2421844.89       826441.31
      2422034.15       826250.01
#Sta/Elev= 30
  2838.1      76  2897.1   75.74  3028.7   68.07  3243.6   59.65  3350.2    58.6
    3373   56.49  3451.6    57.5  3765.2   52.97  3776.2   51.39  4018.2   51.87
  4096.1   46.13  4144.6   44.94  4345.8   45.25  4372.2   43.25  4403.6    45.8
  4549.4   46.16  4593.8   42.56  4744.3    41.8  4811.7   43.71  4871.1   41.57
  4957.2   42.22  4974.9   40.53  4975.4   39.53  5025.1   40.53  5025.7    46.9
  5030.9   49.98  5045.8   58.11  5082.2   72.37    5150   81.61  5269.1   83.04
#Mann= 3 ,-1,0
  2838.1     .15       0  4974.9     .05       0  5025.1     .15       0
Bank Sta=4974.9,5025.1
XS Rating Curve= 0 ,0
Exp/Cntr=0.3,0.1

Type RM Length L Ch R = 1 ,17500   ,800,800,800
BEGIN DESCRIPTION:
Willow Creek 30.0
END DESCRIPTION:
XS GIS Cut Line= 3
      2420954.17       828388.81      2422130.99        826825.8
      2422213.82       826473.92
#Sta/Elev= 30
  3043.5   83.86  3137.6   80.28  3270.4   72.76  3277.7   70.98  3286.6   71.98
  3380.1   64.84  3692.1   54.92    3970   50.31  3987.4   51.69  4206.2   49.93
    4258   47.45  4372.1   48.36  4520.4   44.98  4534.5   43.07  4619.2   44.11
  4645.2   42.27  4688.5   44.97  4768.7   44.61  4974.9   40.03  4975.4   39.03
  5025.1   40.03  5150.8    42.4  5153.6    43.9  5179.3   44.52  5196.4   46.85
    5220   53.67  5263.7   71.13  5308.5   77.33  5333.5   78.23  5361.5   76.58
#Mann= 3 ,-1,0
  3043.5     .15       0  4974.9     .05       0  5025.1     .15       0
Bank Sta=4974.9,5025.1
XS Rating Curve= 0 ,0
Exp/Cntr=0.3,0.1

Type RM Length L Ch R = 1 ,16700   ,500,500,500
BEGIN DESCRIPTION:
Willow Creek 29.0
END DESCRIPTION:
XS GIS Cut Line= 3
      2421129.85       828426.65      2422541.39         827337.
      2423797.17       826719.69
#Sta/Elev= 30
  3216.8   82.89  3360.7   74.31  3401.2   69.24  3571.6   63.08  3593.1   64.73
  3608.7   62.49  3747.8   57.15  3921.2   53.24  3972.4   47.65    4648   45.56
  4863.2   43.39  4972.5   39.03    4973   38.03  5027.5   39.03  5141.9   40.56
  5175.3   44.07  5452.4   45.52  5530.7    49.3  5609.5   48.25  6007.2   51.08
  6098.8   56.93  6179.4   68.66  6190.1    66.8  6198.8   68.92  6205.6   66.82
  6227.2   69.57  6250.3   75.93  6294.8    80.5  6326.6      87  6399.3   90.84
#Mann= 3 ,-1,0
  3216.8     .15       0  4972.5     .05       0  5027.5     .15       0
Bank Sta=4972.5,5027.5
XS Rating Curve= 0 ,0
Exp/Cntr=0.3,0.1

Type RM Length L Ch R = 1 ,16200   ,600,600,600
BEGIN DESCRIPTION:
Willow Creek 28.0
END DESCRIPTION:
XS GIS Cut Line= 3
      2421210.98       828639.47      2422715.75       827709.41
      2424046.46       826868.39
#Sta/Elev= 30
    3231   85.68  3413.2   80.43  3538.4   71.51  3539.5   72.96  3647.1    69.8
  3913.4   54.68  3920.9   52.33  4044.5   49.06  4114.4   44.44  4133.7   45.62
  4164.7   43.39  4262.3      46  4313.4   43.19  4636.6   43.76  4697.9   42.44
  4724.8   39.08  4968.6   40.57  4972.5   38.86    4973   37.86  5027.5   38.86
  5028.5   45.96  5049.4   50.24  5617.3   50.16  5711.7   48.44  5869.6   50.09
  6079.7   59.17    6278   81.88    6309   80.13    6351   84.77  6574.2   90.72
#Mann= 3 ,-1,0
    3231     .15       0  4972.5     .05       0  5027.5     .15       0
Bank Sta=4972.5,5027.5
XS Rating Curve= 0 ,0
Exp/Cntr=0.3,0.1

Type RM Length L Ch R = 1 ,15600   ,400,400,400
BEGIN DESCRIPTION:
Willow Creek 27.0
END DESCRIPTION:
XS GIS Cut Line= 3
      2421455.49       828755.67      2422535.62       828111.75
      2424280.21       827129.31
#Sta/Elev= 30
  3742.5   78.41  3868.8   70.06  3946.5   70.79  4107.7   65.77  4330.5   49.64
  4566.9   44.76    4710   47.66  4828.1    43.4  4867.1    39.9  4930.9   41.08
  4972.5   37.93    4973   36.93  5027.5   37.93    5036    39.8  5075.8   39.99
  5158.4   38.29  5204.6   42.88  5380.9   47.49  5432.9   45.45  5567.3   50.46
  5635.3   48.12  5671.8   43.16  5728.9   46.67  5960.7   44.09  6056.6   48.76
  6143.3   48.82  6433.6   60.88  6462.1    59.3  6679.9   66.57  7002.2   82.31
#Mann= 3 ,-1,0
  3742.5     .15       0  4972.5     .05       0  5027.5     .15       0
Bank Sta=4972.5,5027.5
XS Rating Curve= 0 ,0
Exp/Cntr=0.3,0.1

Type RM Length L Ch R = 1 ,15200   ,600,600,600
BEGIN DESCRIPTION:
Willow Creek 26.0
END DESCRIPTION:
XS GIS Cut Line= 3
      2421810.12       829201.99      2422795.24       828304.43
      2424310.81       827257.69
#Sta/Elev= 30
  3667.3   83.09  3783.9   76.41    3920   64.89  4106.2   57.74  4278.3   45.99
    4474   45.79  4530.8   42.42  4555.3   44.52  4620.5    42.3  4678.5   44.98
    4858    39.1  4940.7   41.88  4948.2   38.64  4972.5   38.44    4973   37.44
  5027.5   38.44  5057.3   42.28    5190   45.42  5479.2   47.22  5797.7   43.06
  6063.6   49.31  6159.6   56.29  6377.6   59.18  6480.1   63.66  6566.6   68.14
  6605.1   72.53  6632.6   71.52  6657.9      75  6738.1   76.17  6841.9   83.88
#Mann= 3 ,-1,0
  3667.3     .15       0  4972.5     .05       0  5027.5     .15       0
Bank Sta=4972.5,5027.5
XS Rating Curve= 0 ,0
Exp/Cntr=0.3,0.1

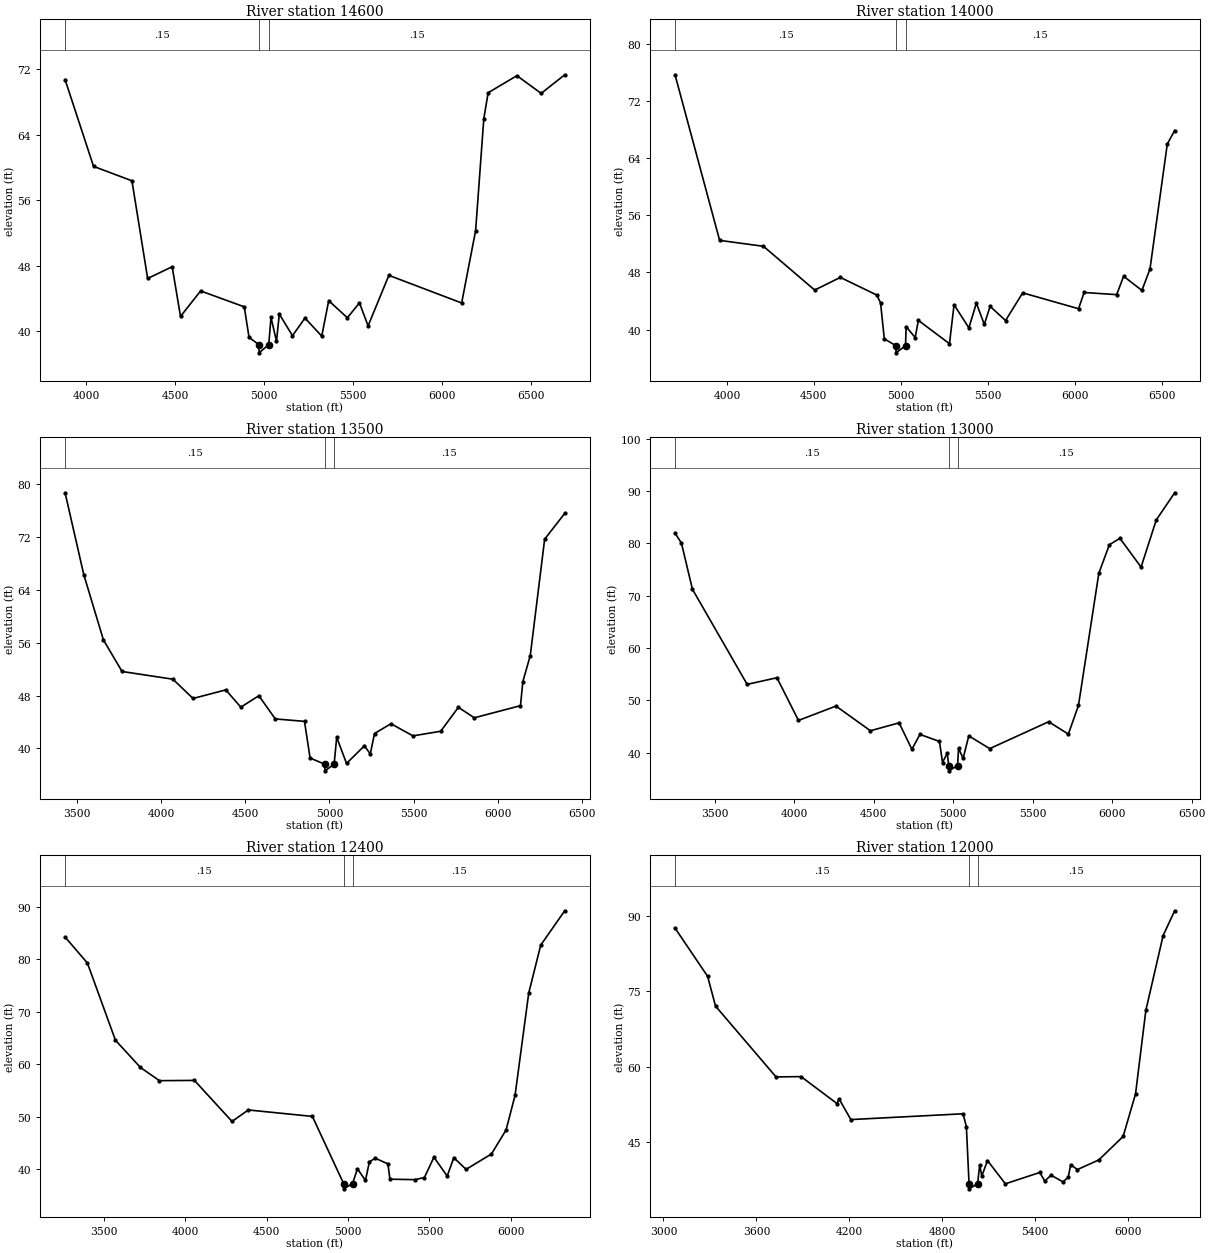
Type RM Length L Ch R = 1 ,14600   ,600,600,600
BEGIN DESCRIPTION:
Willow Creek 25.0
END DESCRIPTION:
XS GIS Cut Line= 3
      2421950.79       829116.37      2422985.01       828693.84
      2424390.29       827752.93
#Sta/Elev= 30
  3882.8   70.71  4042.7   60.13  4258.6   58.37  4346.9   46.46  4484.7   47.89
  4531.7   41.83  4644.6   44.94    4890      43  4916.8   39.27  4972.5   38.39
    4973   37.39  5027.5   38.39  5040.2    41.7  5071.1   38.81    5087   42.12
  5160.8   39.48  5231.2   41.63  5325.4   39.43  5364.6   43.75  5469.4   41.67
  5537.5   43.48    5586   40.68  5702.8   46.84  6111.9   43.47  6190.3   52.29
  6236.3   65.92  6260.7   69.11  6422.5   71.19  6558.9   69.03  6691.2    71.3
#Mann= 3 ,-1,0
  3882.8     .15       0  4972.5     .05       0  5027.5     .15       0
Bank Sta=4972.5,5027.5
XS Rating Curve= 0 ,0
Exp/Cntr=0.3,0.1

Type RM Length L Ch R = 1 ,14000   ,500,500,500
BEGIN DESCRIPTION:
Willow Creek 24.0
END DESCRIPTION:
XS GIS Cut Line= 4
      2421944.66       829305.91      2423186.48       828927.49
      2423297.84       828913.94      2424640.92       828333.79
#Sta/Elev= 30
  3701.8   75.64  3958.3   52.48  4210.5   51.65  4504.9   45.53  4652.5    47.3
  4861.5   44.84  4883.7   43.76  4905.4    38.7  4972.5   37.75    4973   36.75
  5027.5   37.75  5030.9   40.41    5083   38.89  5101.1   41.29  5280.1   38.03
  5306.6   43.48  5391.7   40.24  5434.8    43.7  5480.5   40.72  5513.8   43.25
  5602.7   41.27  5701.2   45.14  6022.3   42.92  6054.7   45.19  6241.7   44.89
  6281.6   47.46  6386.7   45.48  6433.2   48.46  6532.8   65.96  6575.2   67.84
#Mann= 3 ,-1,0
  3701.8     .15       0  4972.5     .05       0  5027.5     .15       0
Bank Sta=4972.5,5027.5
XS Rating Curve= 0 ,0
Exp/Cntr=0.3,0.1

Type RM Length L Ch R = 1 ,13500   ,500,500,500
BEGIN DESCRIPTION:
Willow Creek 23.0
END DESCRIPTION:
XS GIS Cut Line= 3
      2421926.31       829354.83      2423480.83       829120.35
      2424879.34       829104.15
#Sta/Elev= 30
  3427.9   78.73    3539   66.33  3655.8   56.43  3766.7   51.64  4069.1   50.47
  4188.5   47.55  4383.5   48.85  4472.7   46.23  4580.1   47.96  4677.7   44.45
  4851.4   44.08  4884.6   38.52  4972.5   37.58    4973   36.58  5027.5   37.58
  5042.9   41.66  5101.3    37.7  5207.7   40.38  5242.4   39.14  5267.8   42.24
  5365.3   43.72  5496.3   41.88  5661.3   42.58  5766.3   46.21  5861.1   44.62
  6135.5   46.46  6149.7   50.11  6193.8   54.06  6279.3    71.7  6398.6    75.6
#Mann= 3 ,-1,0
  3427.9     .15       0  4972.5     .05       0  5027.5     .15       0
Bank Sta=4972.5,5027.5
XS Rating Curve= 0 ,0
Exp/Cntr=0.3,0.1

Type RM Length L Ch R = 1 ,13000   ,600,600,600
BEGIN DESCRIPTION:
Willow Creek 22.0
END DESCRIPTION:
XS GIS Cut Line= 3
      2421865.19       829415.97      2423613.29       829486.06
      2424995.52       829660.53
#Sta/Elev= 30
  3250.5   81.97  3290.7   80.08  3359.9   71.24  3704.2   53.04  3891.6   54.31
  4026.9   46.14  4262.7   48.89  4479.6   44.17  4659.8   45.68  4740.4   40.62
  4790.9   43.47  4913.8   42.12  4933.1   38.08  4962.4   39.88  4972.5    37.5
    4973    36.5  5027.5    37.5    5034    40.8  5062.5   38.89  5098.3   43.19
    5230   40.75  5600.6   45.89  5724.5   43.53  5788.2   49.01  5916.3    74.3
  5982.4   79.75  6048.9   80.98    6182   75.47  6277.5   84.49  6393.2   89.69
#Mann= 3 ,-1,0
  3250.5     .15       0  4972.5     .05       0  5027.5     .15       0
Bank Sta=4972.5,5027.5
XS Rating Curve= 0 ,0
Exp/Cntr=0.3,0.1

Type RM Length L Ch R = 1 ,12400   ,400,400,400
BEGIN DESCRIPTION:
Willow Creek 21.0
END DESCRIPTION:
XS GIS Cut Line= 4
      2421718.46       829703.33      2423454.75       829803.89
      2423610.47       829841.47      2424781.55       829850.06
#Sta/Elev= 30
  3260.8   84.23  3397.9   79.29  3570.2   64.58  3724.1   59.38  3840.7   56.87
  4055.7   56.92  4286.8    49.1  4386.8   51.29  4780.5   50.06  4972.5   37.26
    4973   36.26  5027.5   37.26  5057.3   40.08  5106.8   37.86  5130.9   41.41
    5167   42.09  5244.7   41.02  5257.2    38.1  5410.7   38.01  5469.2   38.42
  5527.5   42.29    5609   38.69  5649.7   42.19  5725.1   39.97  5881.1    42.9
  5971.1   47.49  6026.1   54.07  6110.2   73.58  6183.8   82.69  6331.3   89.24
#Mann= 3 ,-1,0
  3260.8     .15       0  4972.5     .05       0  5027.5     .15       0
Bank Sta=4972.5,5027.5
XS Rating Curve= 0 ,0
Exp/Cntr=0.3,0.1

Type RM Length L Ch R = 1 ,12000   ,500,500,500
BEGIN DESCRIPTION:
Willow Creek 20.0
END DESCRIPTION:
XS GIS Cut Line= 3
      2421589.99       829847.61      2423491.67         830147.
      2424779.86       829976.66
#Sta/Elev= 30
  3074.9   87.54  3285.1   77.97  3336.2   72.06  3726.7      58  3888.3   58.06
  4119.8   52.72  4134.1   53.61  4209.6   49.53  4933.6   50.68  4955.1   48.15
  4972.5   36.78    4973   35.78  5027.5   36.78  5041.3   40.54  5054.8    38.3
  5091.4    41.4  5206.9   36.78  5429.1   39.03    5461   37.33  5501.4   38.49
  5578.8   37.16  5612.7   38.08  5628.2   40.57    5672   39.61  5809.4   41.51
  5966.8   46.18  6046.9   54.62  6113.6   71.23  6224.9   86.06  6299.4   90.98
#Mann= 3 ,-1,0
  3074.9     .15       0  4972.5     .05       0  5027.5     .15       0
Bank Sta=4972.5,5027.5
XS Rating Curve= 0 ,0
Exp/Cntr=0.3,0.1

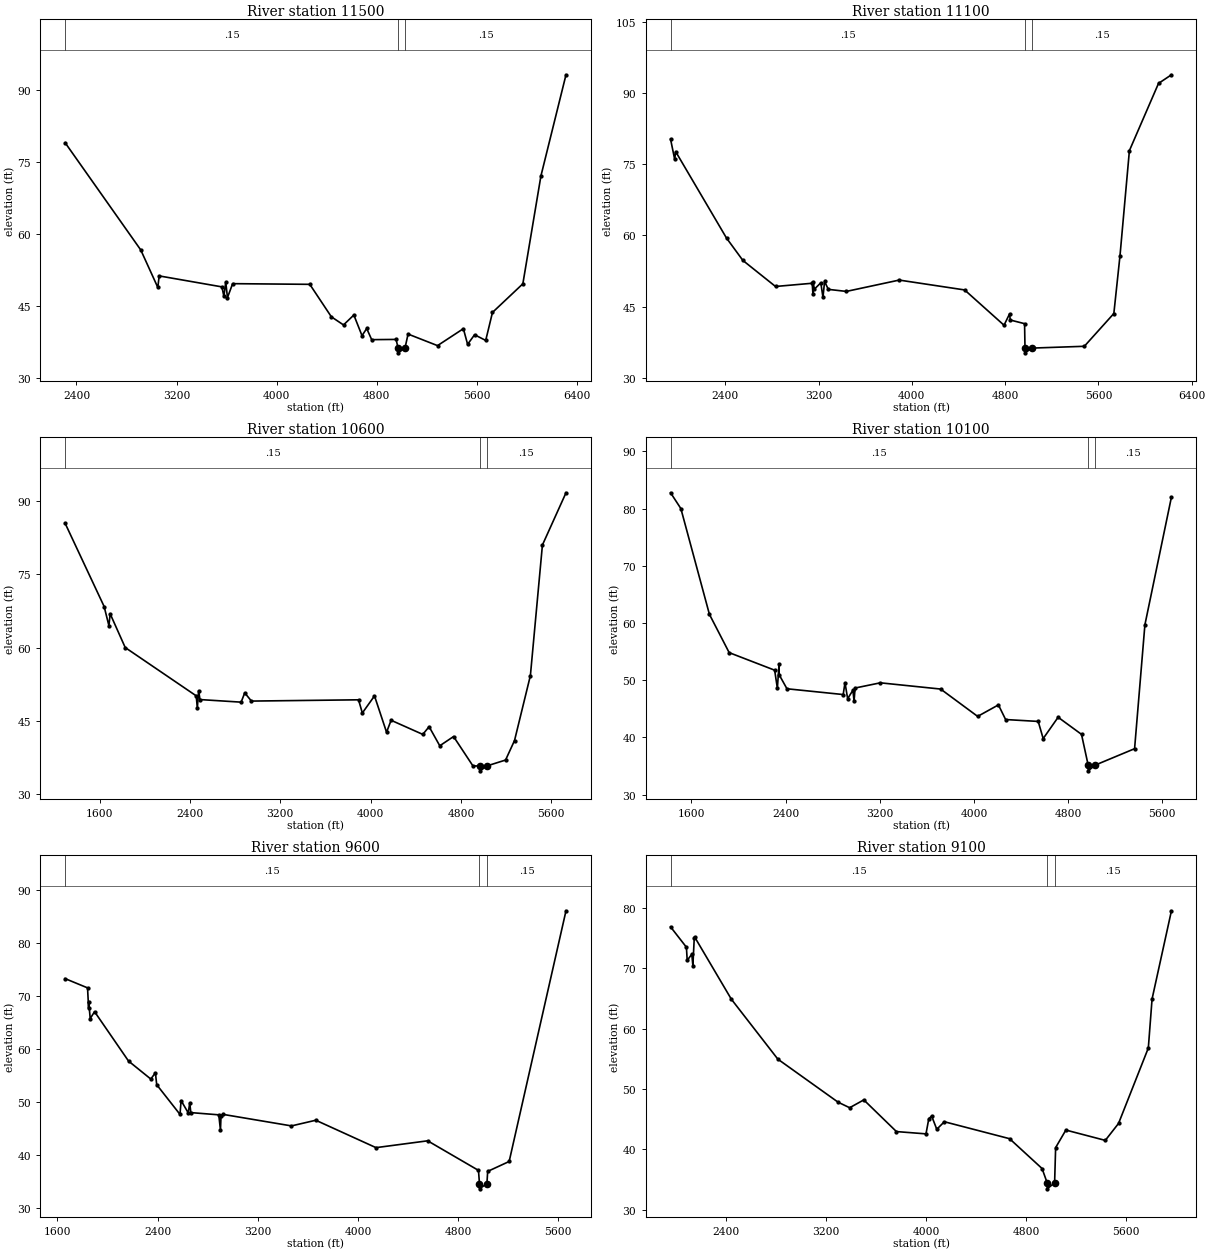
Type RM Length L Ch R = 1 ,11500   ,400,400,400
BEGIN DESCRIPTION:
Willow Creek 19.0
END DESCRIPTION:
XS GIS Cut Line= 3
       2421363.8       831993.65       2423618.5       830525.26
      2424873.31        830131.3
#Sta/Elev= 30
  2309.3   78.96    2914   56.68  3050.4   48.89  3061.4   51.28  3563.2      49
    3579   47.03  3593.8   50.02  3607.5   46.77    3649   49.67  4265.9   49.53
  4438.5   42.78  4535.7   41.09  4618.4   43.15  4683.7   38.86  4721.2   40.35
    4761   38.03  4955.9   38.08  4972.5   36.29    4973   35.29  5027.5   36.29
    5052   39.19  5287.6   36.79  5494.4   40.31  5528.2   37.06    5584   39.05
    5673   37.87  5727.1   43.69  5970.1   49.64  6114.6   72.06  6315.2   93.09
#Mann= 3 ,-1,0
  2309.3     .15       0  4972.5     .05       0  5027.5     .15       0
Bank Sta=4972.5,5027.5
XS Rating Curve= 0 ,0
Exp/Cntr=0.3,0.1

Type RM Length L Ch R = 1 ,11100   ,500,500,500
BEGIN DESCRIPTION:
Willow Creek 18.0
END DESCRIPTION:
XS GIS Cut Line= 3
      2421339.33       832507.24      2423881.01       830786.63
      2424958.87       830202.23
#Sta/Elev= 30
  1930.7   80.26  1965.9   76.04  1974.3   77.66  2410.5   59.43  2550.8   54.72
  2830.6   49.23  3145.3   49.91  3151.7   47.58  3153.4   50.15  3163.6   48.66
    3219      50  3237.6   46.94  3251.4   50.29  3283.5   48.62  3438.4   48.19
  3891.5   50.58  4452.5    48.5  4790.4   41.06  4837.8   43.45  4843.9   42.16
  4966.6   41.39  4970.2   36.24  4970.7   35.24  5029.8   36.24  5479.1   36.62
  5732.2   43.53    5785   55.74  5865.6   77.87  6115.3   92.04  6226.1   93.86
#Mann= 3 ,-1,0
  1930.7     .15       0  4970.2     .05       0  5029.8     .15       0
Bank Sta=4970.2,5029.8
XS Rating Curve= 0 ,0
Exp/Cntr=0.3,0.1

Type RM Length L Ch R = 1 ,10600   ,500,500,500
BEGIN DESCRIPTION:
Willow Creek 17.0
END DESCRIPTION:
XS GIS Cut Line= 3
      2421742.85       833578.43      2424304.58       830900.24
      2424879.41         830448.
#Sta/Elev= 30
  1293.9   85.44  1639.3   68.42  1681.8   64.48  1692.7   66.93  1826.1   60.02
  2455.4   50.13    2465    47.6  2476.5   51.19  2488.7   49.37  2853.1   48.84
    2885   50.74  2944.4   49.06  3893.3   49.32  3926.9   46.62  4034.7   50.12
  4141.6   42.68  4181.8   45.13  4462.5   42.24  4518.5   43.82    4613   39.91
  4735.2    41.8  4907.1   35.78  4970.2   35.78  4970.7   34.78  5029.8   35.78
    5196   36.99  5275.4   40.99  5415.9   54.28  5522.5   81.01  5731.4    91.7
#Mann= 3 ,-1,0
  1293.9     .15       0  4970.2     .05       0  5029.8     .15       0
Bank Sta=4970.2,5029.8
XS Rating Curve= 0 ,0
Exp/Cntr=0.3,0.1

Type RM Length L Ch R = 1 ,10100   ,500,500,500
BEGIN DESCRIPTION:
Willow Creek 16.0
END DESCRIPTION:
XS GIS Cut Line= 3
      2422965.66       834367.16      2424668.89       831222.94
      2424922.17       830594.78
#Sta/Elev= 30
  1424.1   82.76  1511.4      80    1754    61.5  1921.6   54.81  2307.9   51.74
  2330.9   48.57  2345.4   52.83  2345.9   50.95  2412.3   48.49  2889.8   47.48
  2905.2   49.54  2927.7   46.76  2972.5   48.23  2982.2   46.31  2990.8   48.62
  3205.3   49.53  3717.4   48.44  4031.8   43.66  4208.1   45.67  4269.2   43.11
    4546   42.78  4588.1   39.78    4715   43.51  4913.6   40.52  4970.2   35.14
  4970.7   34.14  5029.8   35.14  5364.4   38.01    5452   59.68  5677.3   82.01
#Mann= 3 ,-1,0
  1424.1     .15       0  4970.2     .05       0  5029.8     .15       0
Bank Sta=4970.2,5029.8
XS Rating Curve= 0 ,0
Exp/Cntr=0.3,0.1

Type RM Length L Ch R = 1 ,9600    ,500,500,500
BEGIN DESCRIPTION:
Willow Creek 15.0
END DESCRIPTION:
XS GIS Cut Line= 3
      2423913.37       834373.21      2425106.34       831255.78
      2425093.37       830594.71
#Sta/Elev= 30
  1662.1   73.22  1840.9   71.48  1849.5   67.64  1850.2   68.84  1862.2   65.69
  1896.9   66.99  2168.3   57.67    2346   54.28  2382.7   55.46  2393.2   53.21
  2579.1   47.61  2587.9   50.22  2644.8    47.9    2657   49.76  2665.7   47.95
  2888.7   47.53  2902.2   44.68  2906.9   47.38  2918.9   47.63  3469.1   45.44
  3663.3   46.51  4144.1   41.34  4556.6   42.63  4962.4   37.05  4970.2   34.57
  4970.7   33.57  5029.8   34.57  5035.8   36.86  5207.3   38.73  5661.2   86.02
#Mann= 3 ,-1,0
  1662.1     .15       0  4970.2     .05       0  5029.8     .15       0
Bank Sta=4970.2,5029.8
XS Rating Curve= 0 ,0
Exp/Cntr=0.3,0.1

Type RM Length L Ch R = 1 ,9100    ,550,550,550
BEGIN DESCRIPTION:
Willow Creek 14.0
END DESCRIPTION:
XS GIS Cut Line= 3
      2425808.71       834532.19      2425431.86       831511.31
      2425420.81       830546.37
#Sta/Elev= 30
  1955.7   76.86  2082.5   73.49  2088.7   71.31  2125.5   72.33  2134.2   70.46
  2145.2      75  2150.2   75.12    2442   64.88  2814.5   54.94  3296.6   47.81
  3389.1   46.89  3502.4   48.19  3763.6   42.94  4000.2   42.56  4022.7   45.07
  4045.6   45.51  4086.6   43.32  4147.2   44.57  4669.2   41.76  4929.3   36.82
  4970.2   34.45  4970.7   33.45  5029.8   34.45    5038   40.28  5119.9   43.19
  5435.5   41.48  5541.7   44.29    5780   56.79    5810   64.92    5965   79.53
#Mann= 3 ,-1,0
  1955.7     .15       0  4970.2     .05       0  5029.8     .15       0
Bank Sta=4970.2,5029.8
XS Rating Curve= 0 ,0
Exp/Cntr=0.3,0.1

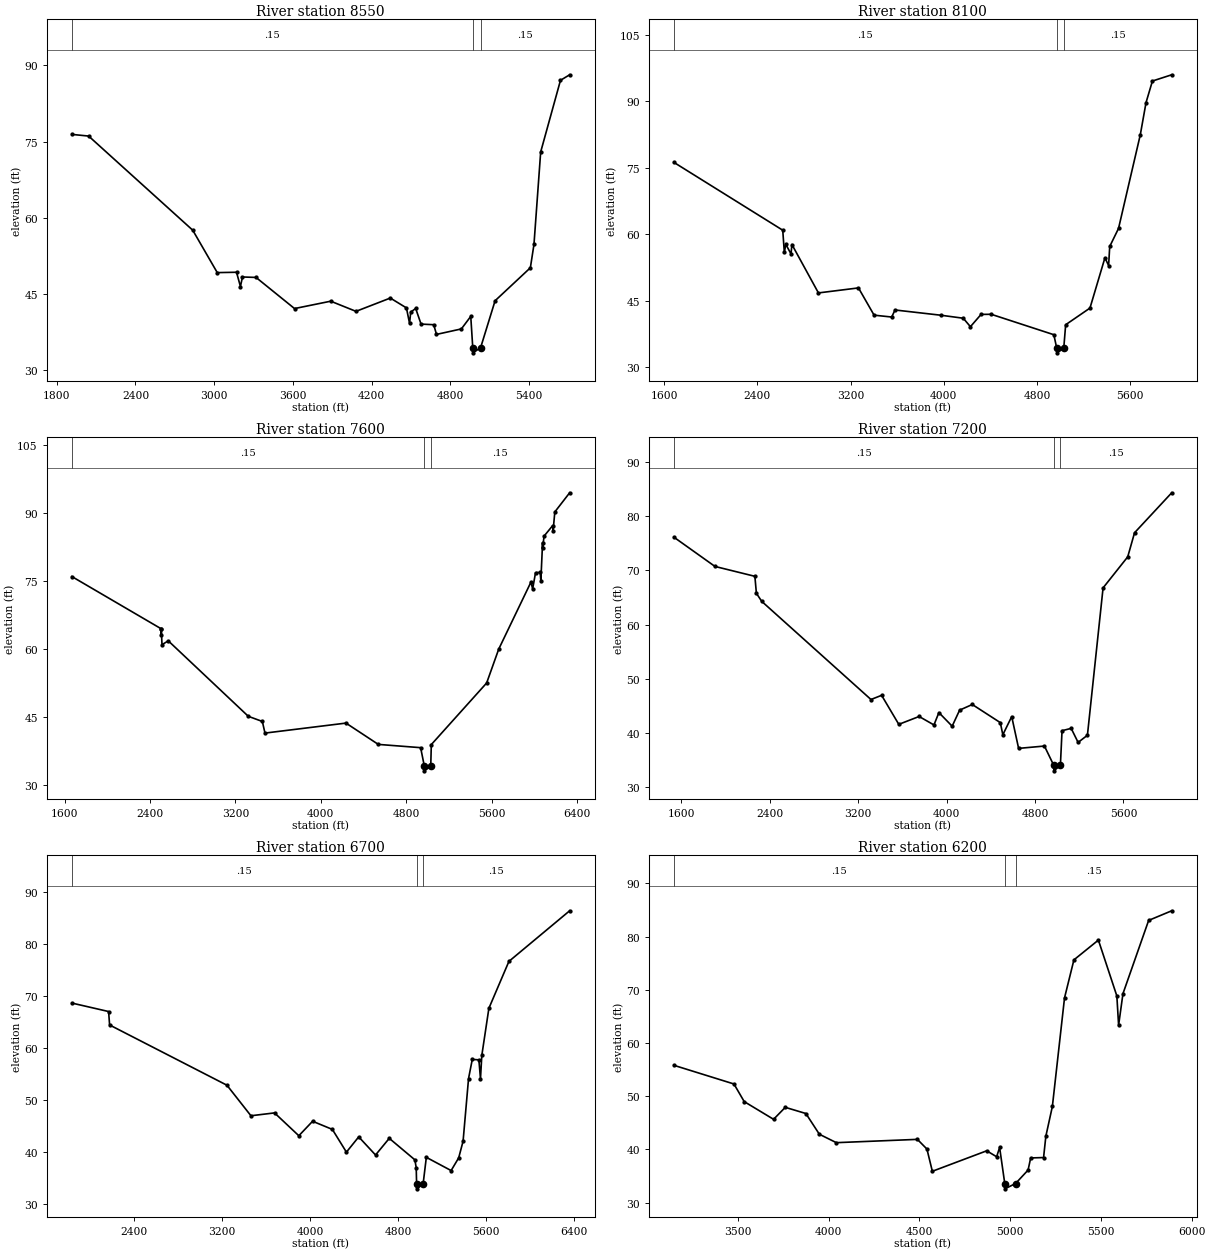
Type RM Length L Ch R = 1 ,8550    ,450,450,450
BEGIN DESCRIPTION:
Willow Creek 13.0
END DESCRIPTION:
XS GIS Cut Line= 3
      2426105.63       834202.08      2425711.52       831142.66
      2425562.12       830450.09
#Sta/Elev= 30
  1915.3   76.43    2043    76.1  2836.4   57.56  3023.2   49.21  3170.1   49.28
  3199.7   46.47  3215.4   48.35  3318.7   48.26    3612   42.13  3887.9   43.58
  4080.4   41.58  4341.9    44.2  4464.7   42.26  4488.5   39.22  4497.5   41.43
  4535.2   42.15  4576.2   39.07  4672.6   38.95  4693.8   37.04  4883.3   38.12
  4954.9   40.59  4970.2   34.41  4970.7   33.41  5029.8   34.41  5140.3   43.67
  5409.1   50.16  5436.6   54.76  5487.7   72.97  5638.6   87.08  5708.5   88.17
#Mann= 3 ,-1,0
  1915.3     .15       0  4970.2     .05       0  5029.8     .15       0
Bank Sta=4970.2,5029.8
XS Rating Curve= 0 ,0
Exp/Cntr=0.3,0.1

Type RM Length L Ch R = 1 ,8100    ,500,500,500
BEGIN DESCRIPTION:
Willow Creek 12.0
END DESCRIPTION:
XS GIS Cut Line= 4
      2426317.86       834195.75      2426069.81       831041.98
      2425981.62       830917.46      2425649.36       830020.42
#Sta/Elev= 30
  1683.9   76.17  2617.9   60.87  2631.5   55.88  2644.4   57.67  2688.9   55.52
  2696.7   57.64  2924.2   46.72  3267.9   47.85    3402    41.7    3553   41.28
  3581.6   42.87  3974.4   41.69  4167.2   41.01  4228.8    39.1  4320.3   41.87
  4407.3    41.9  4944.7   37.29  4970.2    34.2  4970.7    33.2  5029.8    34.2
  5046.3   39.54  5254.9    43.3  5383.4   54.65  5414.9    52.9  5424.5    57.2
  5500.1   61.27  5687.1   82.42  5736.2   89.67  5790.9   94.53  5956.6   95.94
#Mann= 3 ,-1,0
  1683.9     .15       0  4970.2     .05       0  5029.8     .15       0
Bank Sta=4970.2,5029.8
XS Rating Curve= 0 ,0
Exp/Cntr=0.3,0.1

Type RM Length L Ch R = 1 ,7600    ,400,400,400
BEGIN DESCRIPTION:
Willow Creek 11.0
END DESCRIPTION:
XS GIS Cut Line= 3
      2426392.22       834230.72       2426400.6       830899.23
       2426320.1       829570.77
#Sta/Elev= 30
  1668.5   75.97  2505.1   64.47  2505.5    63.1  2505.7   64.39  2512.8   60.97
  2571.4   61.82  3321.3    45.2  3452.6   44.07  3477.2   41.51  4235.9   43.71
  4538.6   39.02  4935.1    38.3  4970.2    34.2  4970.7    33.2  5029.8    34.2
  5035.1   38.98  5553.5   52.54  5666.6      60  5968.4   74.75  5984.4   73.26
  6011.3   76.82  6054.9   76.87    6061   75.01  6077.3   83.44  6077.5   82.15
  6091.1   84.87  6172.5    87.2    6176   86.04  6191.9   90.19  6330.9   94.41
#Mann= 3 ,-1,0
  1668.5     .15       0  4970.2     .05       0  5029.8     .15       0
Bank Sta=4970.2,5029.8
XS Rating Curve= 0 ,0
Exp/Cntr=0.3,0.1

Type RM Length L Ch R = 1 ,7200    ,500,500,500
BEGIN DESCRIPTION:
Willow Creek 10.0
END DESCRIPTION:
XS GIS Cut Line= 3
      2426564.18       834326.21      2426795.53       830867.24
      2427022.73       829855.33
#Sta/Elev= 30
  1533.3    76.1  1904.7   70.71  2265.7   68.89  2279.4   65.76  2327.9   64.27
  3316.1   46.18  3412.3   46.95  3567.9    41.6  3751.7   43.05    3886   41.49
  3930.6   43.77  4050.6   41.26  4118.2   44.22  4232.7   45.26  4486.3   41.92
  4509.1   39.68  4589.5   43.03  4651.9   37.17  4885.6    37.6  4970.2   34.03
  4970.7   33.03  5029.8   34.03  5044.8   40.43  5127.4   40.86  5190.2   38.27
  5274.4   39.59  5416.1   66.76  5639.1   72.48  5700.8   76.92  6037.1   84.29
#Mann= 3 ,-1,0
  1533.3     .15       0  4970.2     .05       0  5029.8     .15       0
Bank Sta=4970.2,5029.8
XS Rating Curve= 0 ,0
Exp/Cntr=0.3,0.1

Type RM Length L Ch R = 1 ,6700    ,500,500,500
BEGIN DESCRIPTION:
Willow Creek 9.0
END DESCRIPTION:
XS GIS Cut Line= 3
        2426803.       834135.21      2427261.87       831001.63
      2427395.31       829645.18
#Sta/Elev= 30
    1833   68.64  2167.3   67.01  2176.4   64.42  3244.4   52.81  3462.5   46.93
  3677.4   47.48  3898.4   43.08  4023.7   45.87  4203.6    44.3  4331.5   39.92
  4443.4   42.86  4596.5   39.37  4721.4   42.58  4954.3   38.44  4966.6   36.94
  4970.2   33.85  4970.7   32.85  5029.8   33.85  5058.7   38.92  5284.3   36.37
  5353.2   38.82  5393.1   42.02  5442.9    54.1  5476.9   57.79    5537    57.7
  5551.5   54.05  5563.6   58.55  5627.9   67.63  5810.3   76.67    6363   86.42
#Mann= 3 ,-1,0
    1833     .15       0  4970.2     .05       0  5029.8     .15       0
Bank Sta=4970.2,5029.8
XS Rating Curve= 0 ,0
Exp/Cntr=0.3,0.1

Type RM Length L Ch R = 1 ,6200    ,600,600,600
BEGIN DESCRIPTION:
Willow Creek 8.0
END DESCRIPTION:
XS GIS Cut Line= 3
      2427701.01       832597.13      2427680.88       830744.64
      2427643.69       829855.32
#Sta/Elev= 30
  3147.4   55.81  3478.2    52.3  3534.6   48.99  3696.4   45.66  3760.9   47.91
  3874.4   46.75  3948.8   42.85  4042.4   41.27  4488.8   41.89  4541.4   40.07
  4571.2   35.89  4870.8   39.74  4925.5   38.62  4941.9   40.37  4970.2   33.59
  4970.7   32.59  5029.8   33.59  5098.7   36.12    5113    38.4  5184.1   38.47
  5196.6   42.48  5232.5   48.07  5299.5   68.48  5351.2   75.63  5486.1   79.35
  5587.8   68.85  5597.5   63.35  5621.5   69.28    5763   83.05  5890.1   84.86
#Mann= 3 ,-1,0
  3147.4     .15       0  4970.2     .05       0  5029.8     .15       0
Bank Sta=4970.2,5029.8
XS Rating Curve= 0 ,0
Exp/Cntr=0.3,0.1

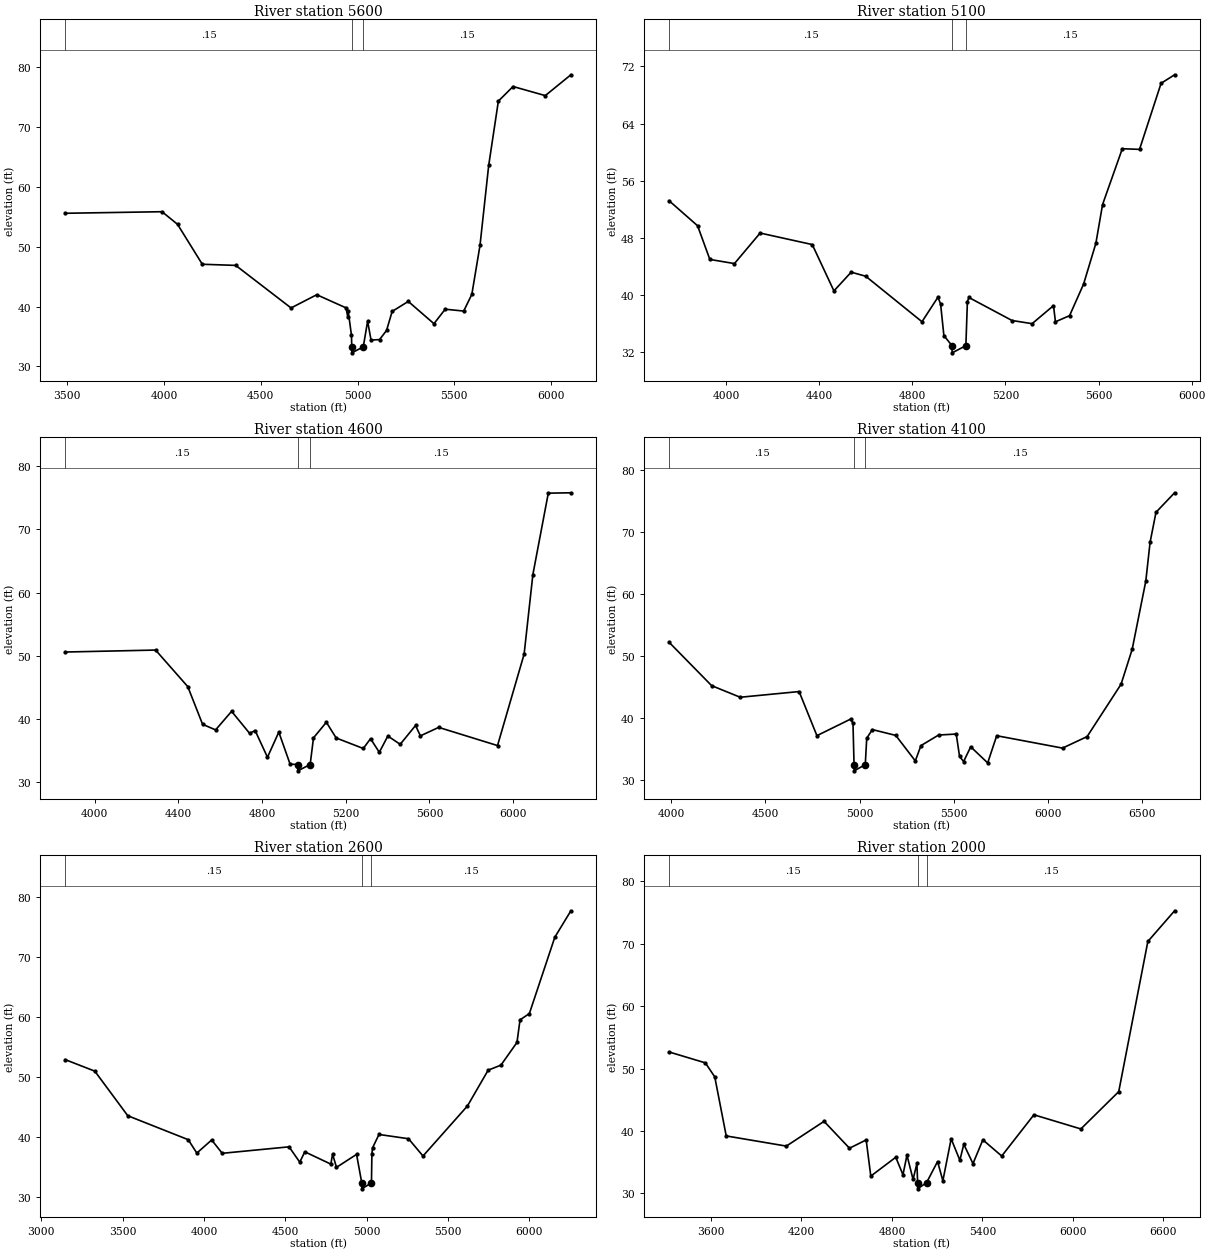
Type RM Length L Ch R = 1 ,5600    ,500,500,500
BEGIN DESCRIPTION:
Willow Creek 7.0
END DESCRIPTION:
XS GIS Cut Line= 3
      2428025.82       832568.46      2427978.38       831059.31
      2428312.41        830008.2
#Sta/Elev= 30
  3490.1   55.59  3989.6   55.85  4069.6   53.75  4197.8   47.07  4370.5   46.88
  4656.5   39.77  4789.3   41.98  4940.9   39.78  4949.7   38.26  4951.8   39.25
  4968.8   35.19  4970.2   33.27  4970.7   32.27  5029.8   33.27  5052.2   37.56
  5069.9   34.41  5113.7   34.48  5150.1   36.01    5179   39.19  5262.4   40.86
  5395.1   37.14  5453.2   39.56  5548.8   39.25  5590.9   42.04  5633.1   50.23
    5678   63.59    5728   74.33    5804   76.77  5970.5   75.25  6102.9   78.73
#Mann= 3 ,-1,0
  3490.1     .15       0  4970.2     .05       0  5029.8     .15       0
Bank Sta=4970.2,5029.8
XS Rating Curve= 0 ,0
Exp/Cntr=0.3,0.1

Type RM Length L Ch R = 1 ,5100    ,500,500,500
BEGIN DESCRIPTION:
Willow Creek 6.0
END DESCRIPTION:
XS GIS Cut Line= 3
      2428302.87       832348.67      2428452.55        831112.1
      2428541.69        830189.7
#Sta/Elev= 30
  3754.4   53.22  3876.9   49.72  3929.6   45.01  4035.3   44.43  4145.7    48.7
  4369.7   47.09  4462.8   40.61    4537   43.23  4599.4   42.66  4841.2    36.3
  4909.6   39.72  4921.1   38.79  4935.3   34.37  4970.2   32.95  4970.7   31.95
  5029.8   32.95  5036.3   39.08  5042.7   39.69  5228.2   36.47  5314.5   36.03
  5406.3   38.55  5414.7   36.29  5475.4   37.15  5535.6   41.56  5588.4   47.26
  5617.2   52.69    5702   60.49    5776    60.4  5868.7   69.64  5926.7   70.83
#Mann= 3 ,-1,0
  3754.4     .15       0  4970.2     .05       0  5029.8     .15       0
Bank Sta=4970.2,5029.8
XS Rating Curve= 0 ,0
Exp/Cntr=0.3,0.1

Type RM Length L Ch R = 1 ,4600    ,500,500,500
BEGIN DESCRIPTION:
Willow Creek 5.0
END DESCRIPTION:
XS GIS Cut Line= 3
      2428704.09       832482.48      2428881.46       831355.66
      2428761.41       830084.62
#Sta/Elev= 30
  3859.3    50.6  4290.7   50.91  4444.6   45.12  4515.4   39.16  4577.6   38.27
  4654.2   41.21  4740.2   37.73  4766.7   38.17  4825.7   33.94  4879.9   37.92
  4933.9   32.85  4970.2   32.79  4970.7   31.79  5029.8   32.79  5045.8   37.01
  5107.3   39.48  5154.3   36.99  5283.8   35.33  5318.6   36.88  5360.5   34.72
  5401.3    37.3  5460.4   35.99  5533.8   38.97    5557   37.33  5644.5   38.67
  5925.8   35.79    6053   50.27  6094.9   62.87  6168.6   75.75  6276.7   75.81
#Mann= 3 ,-1,0
  3859.3     .15       0  4970.2     .05       0  5029.8     .15       0
Bank Sta=4970.2,5029.8
XS Rating Curve= 0 ,0
Exp/Cntr=0.3,0.1

Type RM Length L Ch R = 1 ,4100    ,1500,1500,1500
BEGIN DESCRIPTION:
Willow Creek 4.0
END DESCRIPTION:
XS GIS Cut Line= 4
      2429067.12       832597.09      2429289.27       831610.39
      2429133.99       831221.44      2428971.58       829979.52
#Sta/Elev= 30
  3988.6   52.23  4214.6   45.22  4366.1   43.35  4678.7   44.27  4773.2   37.15
  4951.7   39.82  4964.6   39.14  4970.2   32.47  4970.7   31.47  5029.8   32.47
  5037.6   36.74  5067.6   38.13  5191.7   37.19  5295.4   33.07  5325.1   35.54
  5418.8   37.25  5512.5   37.41  5530.2   33.79  5551.7   32.97  5589.3   35.35
  5679.4   32.75  5727.3   37.14  6076.6   35.14  6207.1      37  6387.2   45.45
  6446.2   51.09  6518.5    62.1  6541.2   68.37  6572.6   73.21  6671.3   76.36
#Mann= 3 ,-1,0
  3988.6     .15       0  4970.2     .05       0  5029.8     .15       0
Bank Sta=4970.2,5029.8
XS Rating Curve= 0 ,0
Exp/Cntr=0.3,0.1

Type RM Length L Ch R = 1 ,2600    ,600,600,600
BEGIN DESCRIPTION:
Willow Creek 3.0
END DESCRIPTION:
XS GIS Cut Line= 5
      2429143.55       832625.73      2429563.88       831488.93
      2429563.88       831116.36       2429488.9        830860.3
      2429258.18       829626.08
#Sta/Elev= 30
  3148.6   52.85  3329.4   50.94  3532.1   43.51  3903.6   39.52  3956.5   37.29
  4047.7   39.47  4112.6   37.25  4523.4   38.33  4589.2   35.77  4620.1    37.5
  4780.1   35.45  4790.7    37.1  4814.9   34.91  4938.2   37.07  4970.2   32.33
  4970.7   31.33  5029.8   32.33  5032.5   37.11  5036.3   38.15  5076.1   40.39
  5257.4   39.68  5346.6    36.8  5619.5   45.13  5747.1    51.1  5825.5   51.94
  5924.1   55.72    5943   59.49  6000.3   60.53  6156.8   73.26  6255.6   77.66
#Mann= 3 ,-1,0
  3148.6     .15       0  4970.2     .05       0  5029.8     .15       0
Bank Sta=4970.2,5029.8
XS Rating Curve= 0 ,0
Exp/Cntr=0.3,0.1

Type RM Length L Ch R = 1 ,2000    ,0,0,0
BEGIN DESCRIPTION:
Willow Creek 2.0
END DESCRIPTION:
XS GIS Cut Line= 5
      2429214.73       832599.32      2429778.59       831766.97
      2429932.49       831112.58      2429892.69       830437.94
      2429395.96       829572.01
#Sta/Elev= 30
  3322.4   52.66  3563.2   50.91  3625.4   48.66  3701.3    39.2  4099.9   37.57
    4350   41.54  4518.6   37.23  4629.2   38.56  4659.9   32.76  4825.4   35.78
  4873.1   32.98  4899.7   36.11  4940.2   32.23  4965.8    34.8  4970.2   31.72
  4970.7   30.72  5029.8   31.72  5102.6    35.1  5137.7   32.01  5192.6   38.74
  5250.4    35.3  5276.5   37.86  5337.3   34.76  5402.9   38.57  5527.9   35.98
  5741.3   42.59  6052.7   40.32  6303.7    46.3  6496.8   70.37  6674.1   75.29
#Mann= 3 ,-1,0
  3322.4     .15       0  4970.2     .05       0  5029.8     .15       0
Bank Sta=4970.2,5029.8
XS Rating Curve= 0 ,0
Exp/Cntr=0.3,0.1
LCMann Table=0

--- WillowCreek.g03 (geometry) ---

Geom Title=Natural Condition
Program Version=6.60

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
River Reach=Willow Creek    ,Reach-1

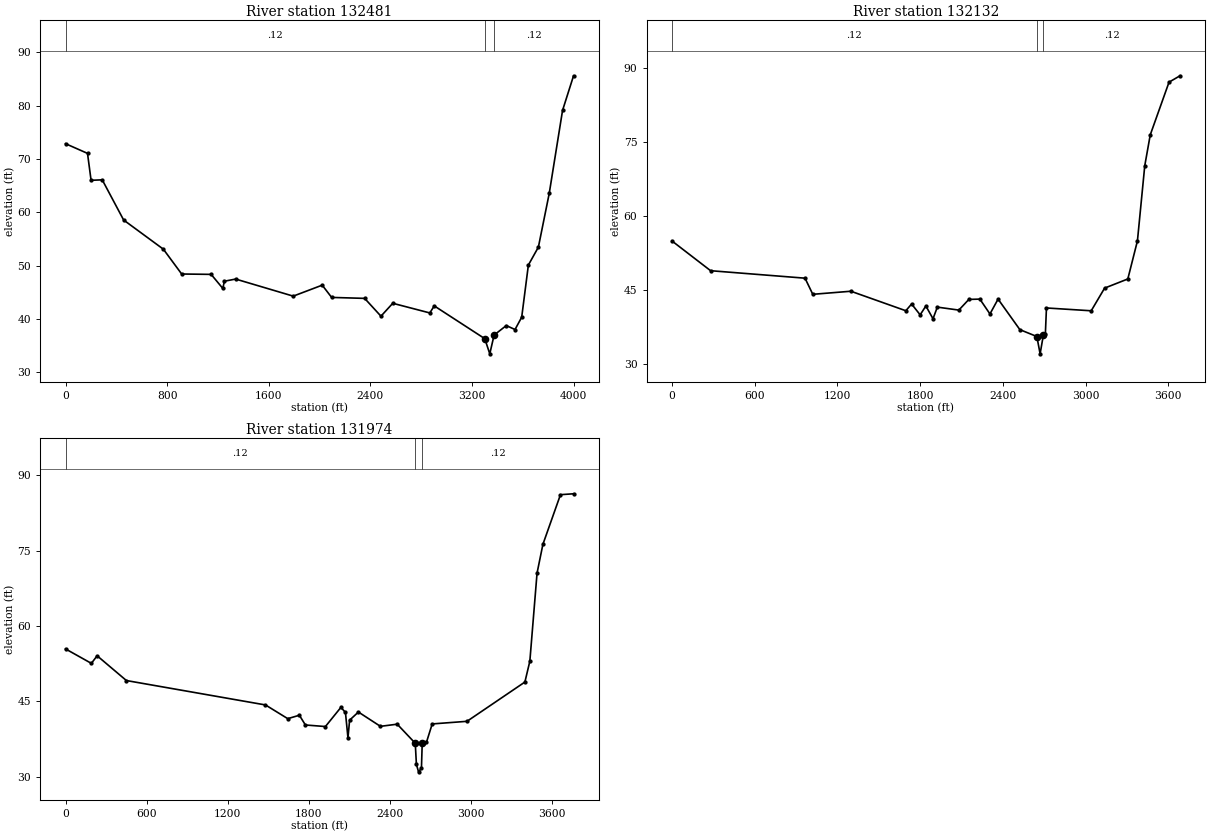
Type RM Length L Ch R = 1 ,132481  ,349.9,349.9,349.9
BEGIN DESCRIPTION:
Willow Creek 15.0
END DESCRIPTION:
XS GIS Cut Line= 3
      2423913.37       834373.21      2425106.34       831255.78
      2425093.37       830594.71
#Sta/Elev= 30
2.31E-11   72.85   173.2   71.03   201.3   65.98   289.1   66.07   457.7   58.53
   770.4   53.06   914.4   48.41  1146.3   48.34  1238.1   45.71  1250.8   47.06
  1339.5   47.46  1792.6   44.26  2020.7   46.32  2094.8   44.02  2354.7   43.84
  2483.1    40.5    2576   42.92  2867.6   41.11  2902.7   42.43  3300.3  36.285
  3339.7   33.44  3373.736.95745  3469.6   38.74  3538.5      38    3591   40.31
  3643.5   50.09  3722.3   53.45  3807.6   63.51  3912.6   79.09  3999.1   85.58
#Mann= 3 ,0,0
2.31E-11     .12       0  3300.3     .04       0  3373.7     .12       0
Bank Sta=3300.3,3373.7
XS Rating Curve= 0 ,0
Exp/Cntr=0.3,0.1

Type RM Length L Ch R = 1 ,132132  ,157.4,157.4,157.4
XS GIS Cut Line= 6
2424368.72477113 833869.458369092424565.91144344833634.789289292
 2424668.7174029 833445.409890292424749.88000247833188.394991645
2425550.68431825830826.5633440922425488.85582631830432.388653409
#Sta/Elev= 30
       0   54.95  280.12   48.94   964.9   47.43 1021.25   44.17 1297.47   44.79
 1695.86   40.85 1737.88   42.21 1799.79   40.02 1841.36   41.81 1893.11   39.23
 1924.51   41.58  2080.4   40.98 2153.15   43.14 2232.83    43.2 2306.06    40.2
 2364.96    43.2 2522.98   37.03 2646.15   35.64 2669.87   32.14 2692.96   35.86
 2708.05   36.23 2715.84   41.41 3040.46   40.84 3137.52   45.42 3305.88   47.27
 3375.62   54.97 3428.75   70.15  3468.6   76.39 3604.76   87.04 3684.42   88.33
#Mann= 3 ,0,0
       0     .12       0 2646.15     .04       0 2692.96     .12       0
Bank Sta=2646.15,2692.96
XS Rating Curve= 0 ,0
Exp/Cntr(USF)=0,0
Exp/Cntr=0.3,0.1

Type RM Length L Ch R = 1 ,131974  ,518.9,518.9,518.9
XS GIS Cut Line= 6
2424514.94662153833929.0353752692424745.31457716833649.314219956
2425022.04600041832826.335992493 2425233.3983525 832144.83248984
2425653.22751447830862.3406662832425570.65001851830402.641947818
#Sta/Elev= 30
       0   55.45  191.47   52.57  234.09   54.08  450.75   49.15 1480.32   44.29
  1645.2   41.56 1731.07   42.24 1775.73    40.3  1923.9   39.99 2038.69   43.81
 2072.15    42.8 2090.81   37.75 2103.07   41.26 2168.06   42.88 2331.16   40.03
 2455.44   40.46 2589.01   36.66 2597.42   32.46  2613.2   30.97 2634.73   31.68
 2640.51   36.69 2672.12   36.87 2714.39   40.51 2971.89   41.03 3400.49   48.85
 3437.16      53 3490.49   70.54 3533.83   76.27 3663.83   86.16 3760.67   86.34
#Mann= 3 ,0,0
       0     .12       0 2589.01     .04       0 2640.51     .12       0
Bank Sta=2589.01,2640.51
XS Rating Curve= 0 ,0
Exp/Cntr(USF)=0,0
Exp/Cntr=0.3,0.1

--- WillowCreek.g07 (geometry) ---

Geom Title=Proposed Condition
Program Version=6.60

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
River Reach=Willow Creek    ,Reach-1