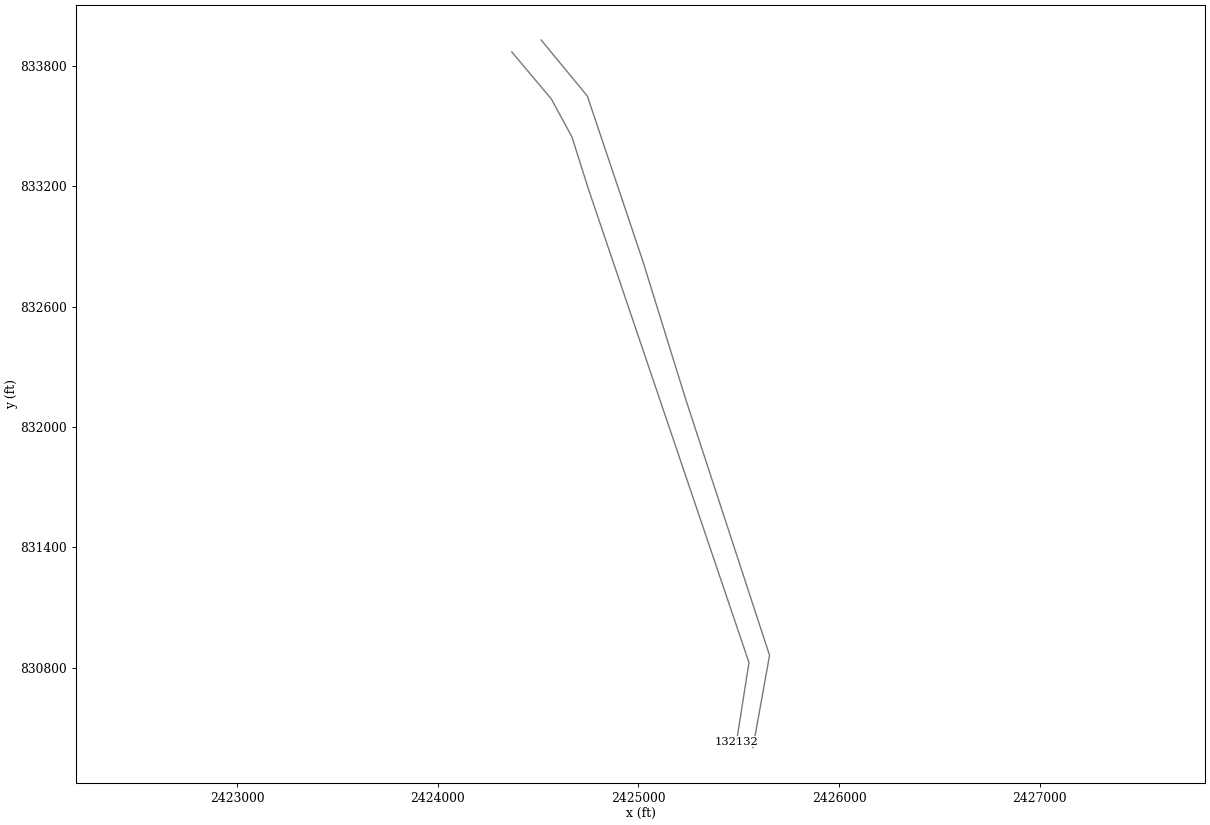
HEC-RAS study WillowCreek.prj: S-21-57 over Willow Creek

--- WillowCreek.g07 (geometry) --- (continued)

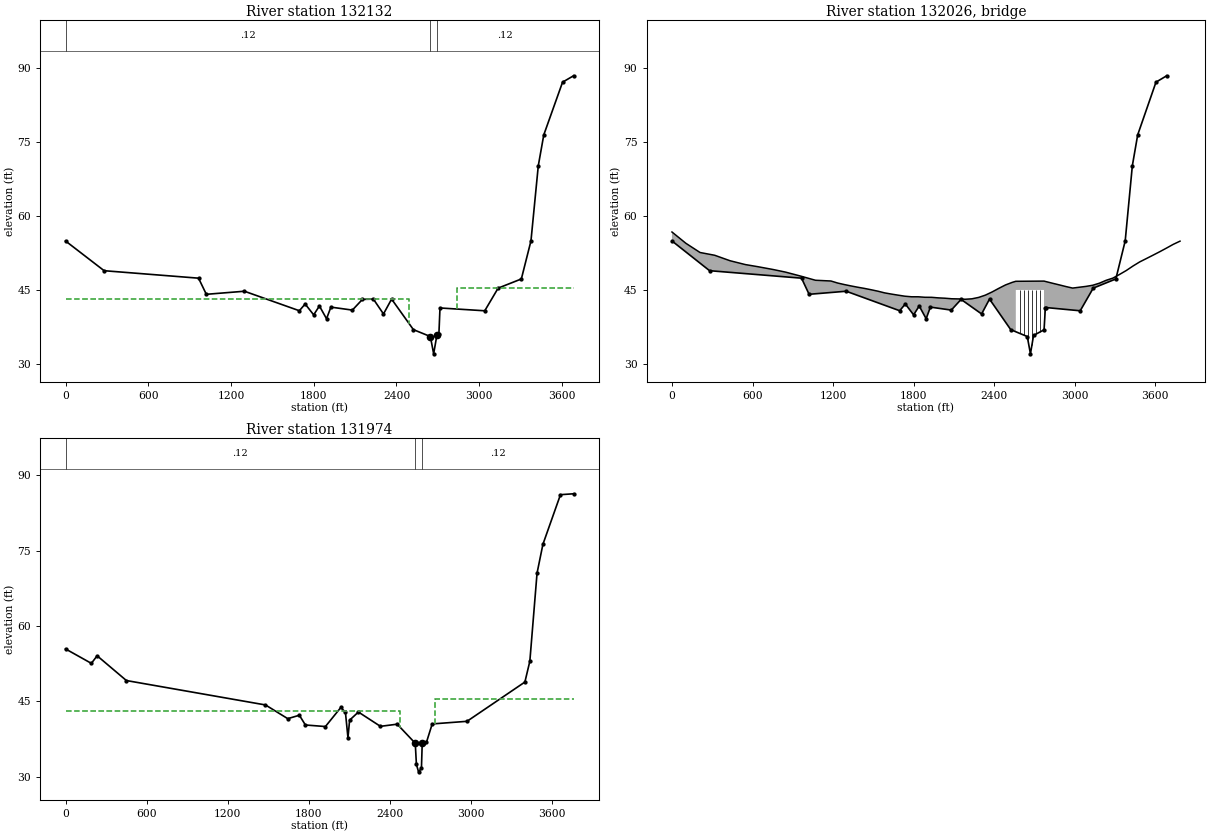
Type RM Length L Ch R = 1 ,132132  ,157.4,157.4,157.4
XS GIS Cut Line= 6
2424368.72477113 833869.458369092424565.91144344833634.789289292
 2424668.7174029 833445.409890292424749.88000247833188.394991645
2425550.68431825830826.5633440922425488.85582631830432.388653409
#Sta/Elev= 30
       0   54.95  280.12   48.94   964.9   47.43 1021.25   44.17 1297.47   44.79
 1695.86   40.85 1737.88   42.21 1799.79   40.02 1841.36   41.81 1893.11   39.23
 1924.51   41.58  2080.4   40.98 2153.15   43.14 2232.83    43.2 2306.06    40.2
 2364.96    43.2 2522.98   37.03 2646.15   35.64 2669.87   32.14 2692.96   35.86
 2708.05   36.23 2715.84   41.41 3040.46   40.84 3137.52   45.42 3305.88   47.27
 3375.62   54.97 3428.75   70.15  3468.6   76.39 3604.76   87.04 3684.42   88.33
#Mann= 3 ,0,0
       0     .12       0 2646.15     .04       0 2692.96     .12       0
#XS Ineff= 2 , 0
        2493.175   43.172838.425           45.43
Permanent Ineff=
       F       F
Bank Sta=2646.15,2692.96
XS Rating Curve= 0 ,0
Exp/Cntr(USF)=0,0
Exp/Cntr=0.5,0.3

Type RM Length L Ch R = 3 ,132026  ,,,
Node Name=N River Rd Bridg
Bridge Culvert-0,0,0,0, 0
Deck Dist Width WeirC Skew NumUp NumDn MinLoCord MaxHiCord MaxSubmerge Is_Ogee
67.625,42.25,2.6,0, 64, 64, , , 0.98, 0, 2,2,,
       0   103.6     209   318.1     433   546.4   641.8   753.6   843.5   954.3
  1068.6  1183.8  1233.8  1283.8  1333.8  1383.8  1433.8  1483.8  1533.8  1583.8
  1633.8  1683.8  1733.8  1783.8  1833.8  1883.8  1933.8  1983.8  2033.8  2083.8
  2133.8  2183.8  2233.8  2283.8  2333.8  2383.8  2433.8  2483.8  2533.8  2560.8
  2560.8  2770.8  2770.8  2783.8  2833.8  2883.8  2933.8  2983.8  3033.8  3083.8
  3133.8  3183.8  3233.8  3283.8  3333.8  3383.8  3433.8  3483.8  3533.8  3583.8
  3633.8  3683.8  3733.8  3783.8
   56.76   54.48   52.62   52.06   50.95   50.18   49.74   49.18   48.67   47.88
   47.01   46.86   46.45   46.14   45.86    45.6   45.36   45.09    44.8   44.46
   44.22      44   43.79   43.67   43.67   43.57   43.56   43.45   43.38   43.27
   43.24   43.17   43.26   43.54      44   44.64   45.37   46.06   46.58    46.8
    46.8   46.84   46.84   46.75   46.41   46.08   45.74   45.43    45.6   45.77
      46   46.42      47   47.44   48.19   48.98   49.89   50.72    51.4   52.09
   52.79   53.52   54.27   54.91
                                                                                
                                                                                
                                                                                
                                                                                
   45.05   45.05
                                                                                
                                
   -58.1    45.5   150.9     260   374.9   488.3   583.7   695.5   785.4   896.2
  1010.5  1125.7  1175.7  1225.7  1275.7  1325.7  1375.7  1425.7  1475.7  1525.7
  1575.7  1625.7  1675.7  1725.7  1775.7  1825.7  1875.7  1925.7  1975.7  2025.7
  2075.7  2125.7  2175.7  2225.7  2275.7  2325.7  2375.7  2425.7  2475.7  2502.7
  2502.7  2712.7  2712.7  2725.7  2775.7  2825.7  2875.7  2925.7  2975.7  3025.7
  3075.7  3125.7  3175.7  3225.7  3275.7  3325.7  3375.7  3425.7  3475.7  3525.7
  3575.7  3625.7  3675.7  3725.7
   56.76   54.48   52.62   52.06   50.95   50.18   49.74   49.18   48.67   47.88
   47.01   46.86   46.45   46.14   45.86    45.6   45.36   45.09    44.8   44.46
   44.22      44   43.79   43.67   43.67   43.57   43.56   43.45   43.38   43.27
   43.24   43.17   43.26   43.54      44   44.64   45.37   46.06   46.58    46.8
    46.8   46.84   46.84   46.75   46.41   46.08   45.74   45.43    45.6   45.77
      46   46.42      47   47.44   48.19   48.98   49.89   50.72    51.4   52.09
   52.79   53.52   54.27   54.91
                                                                                
                                                                                
                                                                                
                                                                                
   45.05   45.05
                                                                                
                                
Pier Skew, UpSta & Num, DnSta & Num=  ,2590.8, 2 ,2532.7, 2 , 0 , 0 , 0 ,,
       2       2
   30.97   46.32
       2       2
   30.97   46.32
Pier Skew, UpSta & Num, DnSta & Num=  ,2620.8, 2 ,2562.7, 2 , 0 , 0 , 0 ,,
       2       2
   30.97   46.32
       2       2
   30.97   46.32
Pier Skew, UpSta & Num, DnSta & Num=  ,2650.8, 2 ,2592.7, 2 , 0 , 0 , 0 ,,
       2       2
   30.97   46.32
       2       2
   30.97   46.32
Pier Skew, UpSta & Num, DnSta & Num=  ,2680.8, 2 ,2622.7, 2 , 0 , 0 , 0 ,,
       2       2
   30.97   46.32
       2       2
   30.97   46.32
Pier Skew, UpSta & Num, DnSta & Num=  ,2710.8, 2 ,2652.7, 2 , 0 , 0 , 0 ,,
       2       2
   30.97   46.32
       2       2
   30.97   46.32
Pier Skew, UpSta & Num, DnSta & Num=  ,2740.8, 2 ,2682.7, 2 , 0 , 0 , 0 ,,
       2       2
   30.97   46.32
       2       2
   30.97   46.32
Abutment Skew #Up #Dn= , 3 , 3
  2560.8  2562.8  2582.8
      43      43      33
  2502.7  2504.7  2524.7
      43      43      33
Abutment Skew #Up #Dn= , 3 , 3
  2748.8  2768.8  2770.8
      33      43      43
  2690.7  2710.7  2712.7
      33      43      43
BR Coef=-1 , 1 , 1 ,0.9, 0 ,,,0.8,0,1.2,0,
WSPro=,,,, 1 ,,,, 0 ,,,, 0 ,,,,-1 ,-1 ,-1 , 0 , 0 , 0 , 0 , 0
BR U #Sta/Elev= 30
       0   54.95  280.12   48.94   964.9   47.43 1021.25   44.17 1297.47   44.79
 1695.86   40.85 1737.88   42.21 1799.79   40.02 1841.36   41.81 1893.11   39.23
 1924.51   41.58  2080.4   40.98 2153.15   43.14 2306.06    40.2 2364.96    43.2
 2522.98   37.03 2646.15   35.64 2669.87   32.14 2692.96   35.86 2771.35      37
 2780.69   41.36 2787.61   41.49 3040.46   40.84 3137.52   45.42 3305.88   47.27
 3375.62   54.97 3428.75   70.15  3468.6   76.39 3604.76   87.04 3684.42   88.33
BR U #Mann= 3
       0     .12 2646.15     .04 2692.96     .12
BR D #Sta/Elev= 30
       0   55.45  191.47   52.57  234.09   54.08  450.75   49.15 1480.32   44.29
  1645.2   41.56 1731.07   42.24 1775.73    40.3  1923.9   39.99 2072.15    42.8
 2090.81   37.75 2103.07   41.26 2168.06   42.88 2175.81   41.47 2331.16   40.03
 2455.44   40.46 2589.01   36.66 2597.42   32.46  2613.2   30.97 2634.73   31.68
 2640.51   36.69    2730      37 2742.79   40.79 2971.89   41.03 3400.49   48.85
 3437.16      53 3490.49   70.54 3533.83   76.27 3663.83   86.16 3760.67   86.34
BR D #Mann= 3
       0     .12 2589.01     .04 2640.51     .12
BC Design=,, 0 ,, 0 ,,6,2590.8,2532.7,30,2
BC Use User HTab Curves=0
BC User HTab FreeFlow(D)= 0

Type RM Length L Ch R = 1 ,131974  ,518.9,518.9,518.9
XS GIS Cut Line= 6
2424514.94662153833929.0353752692424745.31457716833649.314219956
2425022.04600041832826.335992493 2425233.3983525 832144.83248984
2425653.22751447830862.3406662832425570.65001851830402.641947818
#Sta/Elev= 30
       0   55.45  191.47   52.57  234.09   54.08  450.75   49.15 1480.32   44.29
  1645.2   41.56 1731.07   42.24 1775.73    40.3  1923.9   39.99 2038.69   43.81
 2072.15    42.8 2090.81   37.75 2103.07   41.26 2168.06   42.88 2331.16   40.03
 2455.44   40.46 2589.01   36.66 2597.42   32.46  2613.2   30.97 2634.73   31.68
 2640.51   36.69 2672.12   36.87 2714.39   40.51 2971.89   41.03 3400.49   48.85
 3437.16      53 3490.49   70.54 3533.83   76.27 3663.83   86.16 3760.67   86.34
#Mann= 3 ,0,0
       0     .12       0 2589.01     .04       0 2640.51     .12       0
#XS Ineff= 2 , 0
        2478.938   43.172736.462           45.43
Permanent Ineff=
       F       F
Bank Sta=2589.01,2640.51
XS Rating Curve= 0 ,0
Exp/Cntr(USF)=0,0
Exp/Cntr=0.5,0.3