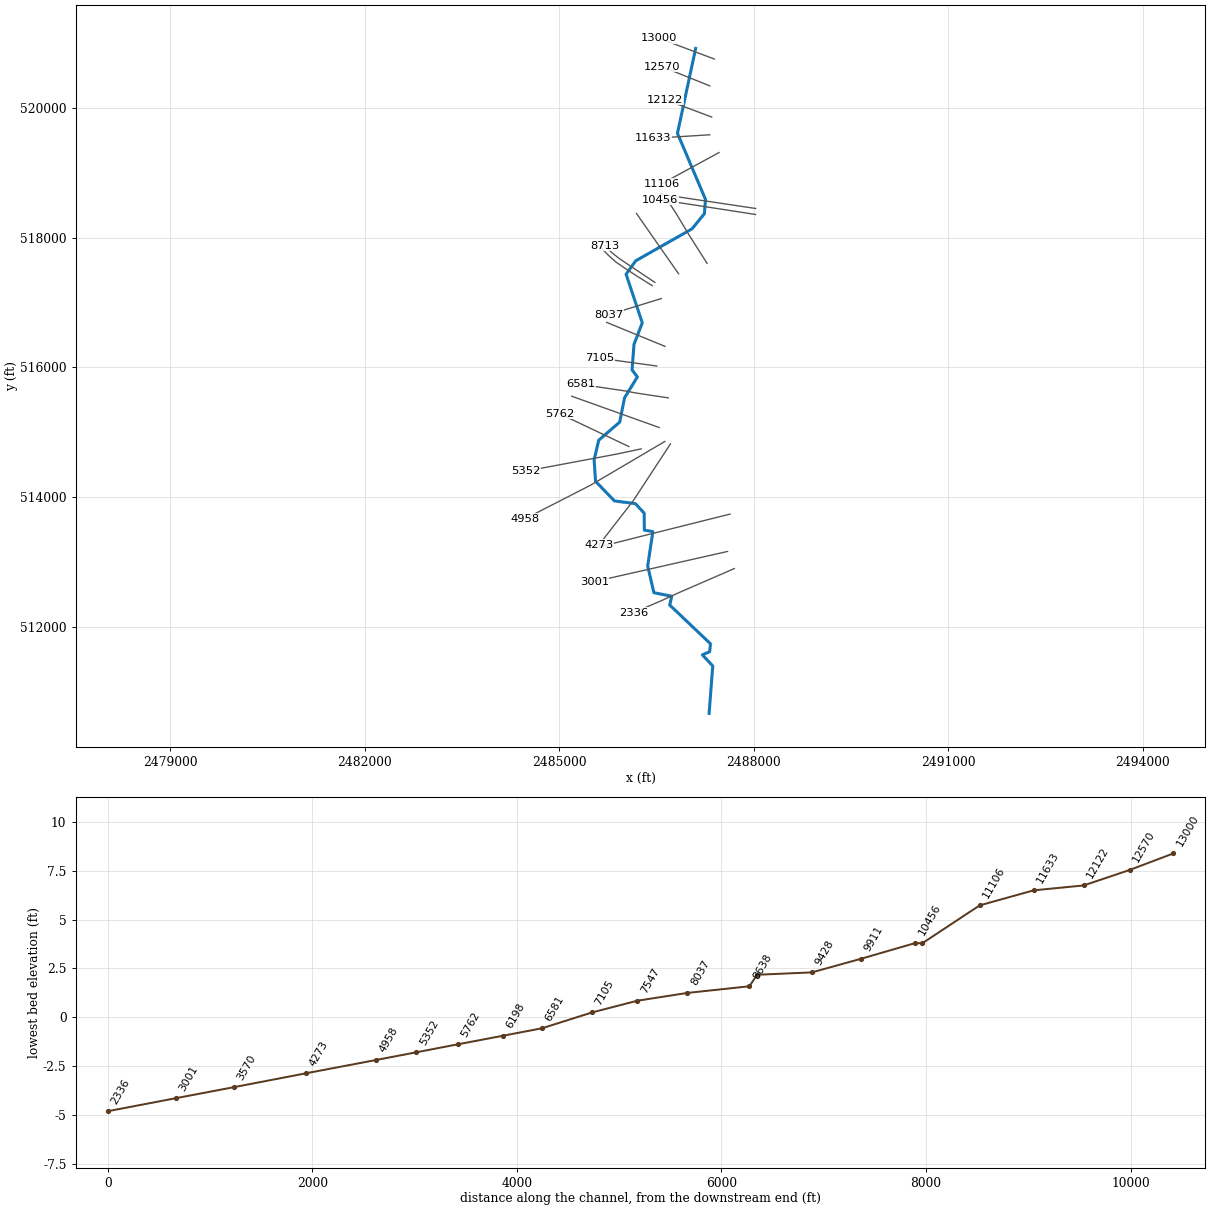
--- PoleSwamp.prj (project) ---

Proj Title=S-22-24 Pole Swamp
Current Plan=p01
Default Exp/Contr=0.3,0.1
English Units
Geom File=g01
Geom File=g04
Geom File=g02
Flow File=f01
Plan File=p01
Plan File=p17
Plan File=p02
Y Axis Title=Elevation
X Axis Title(PF)=Main Channel Distance
X Axis Title(XS)=Station
BEGIN DESCRIPTION:
END DESCRIPTION:
DSS File=dss
DSS Export Rating Curves= 0
DSS Export Rating Curve Sorted= 0
DSS Export Volume Flow Curves= 0
DXF Filename=LaneCreek.
DXF OffsetX= 0
DXF OffsetY= 0
DXF ScaleX= 1
DXF ScaleY= 10

--- PoleSwamp.p01 (plan) ---

Plan Title=Natural
Program Version=6.60
Short Identifier=NAT
Simulation Date=07SEP2025,00:00,09SEP2025,02:00
Geom File=g04
Flow File=f01
Subcritical Flow
K Sum by GR= 0
Std Step Tol= 0.01
Critical Tol= 0.01
Num of Std Step Trials= 20
Max Error Tol= 0.3
Flow Tol Ratio= 0.001
Split Flow NTrial= 30
Split Flow Tol= 0.02
Split Flow Ratio= 0.02
Log Output Level= 0
Friction Slope Method= 1
Unsteady Friction Slope Method= 2
Unsteady Bridges Friction Slope Method= 1
Parabolic Critical Depth
Global Vel Dist= 0 , 0 , 0
Global Log Level= 0
CheckData=True
Encroach Param=-1 ,0,0, 0
Flow Ratio Tolerance=0.1
Flow Ratio Min Ratio=0.5
Flow Ratio Max Ratio=4
Flow Ratio Max Iterations= 10
Computation Interval=5SEC
Output Interval=15MIN
Instantaneous Interval=15MIN
Mapping Interval=15MIN
Computation Time Step Use Courant=        0
Computation Time Step Use Time Series=    0
Computation Time Step Count To Double=0
Computation Time Step Max Doubling=0
Computation Time Step Max Halving=0
Computation Time Step Residence Courant=0
Computation Time Step TS=, 0
Computation Time Step TS=, 0
Computation Time Step TS=, 0
Computation Time Step TS=, 0
Computation Time Step TS=, 0
Computation Time Step TS=, 0
Computation Time Step TS=, 0
Computation Time Step TS=, 0
Computation Time Step TS=, 0
Computation Time Step TS=, 0
Computation Time Step TS=, 0
Computation Time Step TS=, 0
Computation Time Step TS=, 0
Computation Time Step TS=, 0
Computation Time Step TS=, 0
Computation Time Step TS=, 0
Computation Time Step TS=, 0
Computation Time Step TS=, 0
Computation Time Step TS=, 0
Computation Time Step TS=, 0
Computation Time Step TS=, 0
Computation Time Step TS=, 0
Computation Time Step TS=, 0
Computation Time Step TS=, 0
Computation Time Step TS=, 0
Computation Time Step TS=, 0
Computation Time Step TS=, 0
Computation Time Step TS=, 0
Computation Time Step TS=, 0
Computation Time Step TS=, 0
Computation Time Step TS=, 0
Computation Time Step TS=, 0
Computation Time Step TS=, 0
Computation Time Step TS=, 0
Computation Time Step TS=, 0
Computation Time Step TS=, 0
Computation Time Step TS=, 0
Computation Time Step TS=, 0
Computation Time Step TS=, 0
Computation Time Step TS=, 0
Computation Time Step TS=, 0
Computation Time Step TS=, 0
Computation Time Step TS=, 0
Computation Time Step TS=, 0
Computation Time Step TS=, 0
Computation Time Step TS=, 0
Computation Time Step TS=, 0
Computation Time Step TS=, 0
Computation Time Step TS=, 0
Computation Time Step TS=, 0
Run HTab=-1
Run UNet=-1
Run Sediment= 0
Run PostProcess=-1
Run WQNet= 0
Run RASMapper= 0
UNET Theta= 1
UNET Theta Warmup= 1
UNET ZTol= 0.02
UNET ZSATol= 0.02
UNET MxIter= 20
UNET Max Iter WO Improvement= 0
UNET MaxInSteps= 0
UNET DtIC= 0
UNET DtMin= 0
UNET MaxCRTS= 20
UNET WFStab= 2
UNET SFStab= 1
UNET WFX= 1
UNET SFX= 1
UNET Gravity=32.17405
UNET 1D Methodology=Finite Difference
UNET DSS MLevel= 4
UNET Pardiso=0
UNET DZMax Abort= 100
UNET Use Existing IB Tables=-1
UNET Froude Reduction=True
UNET Froude Limit= 0.8
UNET Froude Power= 4
UNET D1 Cores= 0
UNET WindReference=Eulerian
UNET WindDragFormulation=Hsu (1988)
UNET D2 Coriolis=0
UNET D2 Cores= 0
UNET D2 Theta= 1
UNET D2 Theta Warmup= 1
UNET D2 Z Tol= 0.01
UNET D2 Volume Tol= 0.01
UNET D2 Max Iterations= 20
UNET D2 Advanced Convergence=0
UNET D2 WS Max Tol=0.15
UNET D2 WS RMS Tol=0.002
UNET D2 WS Stall Tol=1
UNET D2 Equation= 0
UNET D2 RampUpFraction=0.1
UNET D2 TimeSlices= 1
UNET D2 Turbulence Formulation=None
UNET D2 Eddy Viscosity=0.3
UNET D2 Transverse Eddy Viscosity=0.1
UNET D2 Smagorinsky Mixing=0.05
UNET D2 BCVolumeCheck=0
UNET D2 Cores=0
UNET D2 SolverType=PARDISO (Direct)
UNET D2 Minimum Iterations= 3
UNET D2 Maximum Iterations= 30
UNET D2 Restart Number= 10
UNET D2 Relaxation Coeff=1.3
UNET D2 SOR Precondition Iterations= 10
UNET D2 ILUT Maximum Fill= 8
UNET D2 ILUT Tolerance=1E-08
UNET D2 Convergence Tolerance=0.00001
PS Theta= 1
PS WS Tol= 0.01
PS Volume Tol= 0.01
PS Max Iterations= 20
PS Equation= 0
PS Advance Time Step=-1
PS Target Courant=0.9
PS Time Slices= 1
PS Iterate With 2D=0
PS Project Initial WSE from DS=-1
PS Ramp Up Initial WSE from US=-1
PS Cores=0
UNET D1D2 MaxIter= 0
UNET D1D2 ZTol=0.01
UNET D1D2 QTol=0.1
UNET D1D2 MinQTol=1
DSS File=dss
Write IC File= 0
Write IC File at Fixed DateTime=0
Write IC File at Sim End=0
Echo Input=False
Echo Parameters=False
Echo Output=False
Write Detailed= 0
HDF Write Warmup=0
HDF Write Time Slices=0
HDF Flush=0
HDF Compression= 1
HDF Chunk Size= 1
HDF Spatial Parts= 1
HDF Use Max Rows=0
HDF Fixed Rows= 1
Calibration Method= 0
Calibration Iterations= 20
Calibration Max Change=0.05
Calibration Tolerance=0.2
Calibration Maximum=1.5
Calibration Minimum=0.5
Calibration Optimization Method= 1
WQ AD Non Conservative
WQ ULTIMATE=-1
WQ Max Comp Step=1HOUR
WQ Output Interval=15MIN
WQ Output Selected Increments= 0
WQ Create Restart=0
WQ Fixed Restart=0
WQ System Summary=0
WQ Write To DSS=0
Sorting and Armoring Iterations= 10
XS Update Threshold= 0.02
Bed Roughness Predictor= 0
Processes Affected by Predictor=Sediment Only
Hydraulics Update Threshold= 0.02
Energy Slope Method= 1
Volume Change Method= 1
Sediment Retention Method= 0
Sediment TS Multiplier= 1
Warm Up Method= 0
XS Weighting Method= 0
Number of US Weighted Cross Sections= 1
Number of DS Weighted Cross Sections= 1
Upstream XS Weight=0
Main XS Weight=1
Downstream XS Weight=0
Number of DS XS's Weighted with US Boundary= 1
Upstream Boundary Weight= 1
Weight of XSs Associated with US Boundary= 0
Number of US XS's Weighted with DS Boundary= 1
Downstream Boundary Weight= 0.5
Weight of XSs Associated with DS Boundary= 0.5
Percentile Method= 0
Sediment Output Level= 3
Mass or Volume Output= 0
Output Increment Type= 1
Profile and TS Output Increment= 1
Transport Output Increment 1
XS Output Flag= 0
XS Output Increment= 10
Read HDF5 Sediment Hotstart= 0
Sediment Hotstart Type= 0
Write Gradation File= 0
Read Gradation Hotstart= 0
Write HDF5 File= 1
Write Binary Output= 1
Write DSS Sediment File= 0
DSS Sediment Output Type= 1
SV Curve= 0
Specific Gage Flag= 0
Subcell Erosion Methods= 0
Subcell Deposition Methods= 0
Advection Scheme= 1
Matrix Solver= 0
Implicit Weighting Factor= 1
Maximum Outer Loop Convergence Iterations= 5
Convergence Maximum Absolute= 0.001
Convergence RMSE= 0.0001
Grain Fractions Max Abs Error= 0.001
Max Subgrid Regions= 1
Max Subgrid Length Scale= 3.402823E+38
Initial Layer Thickness= 3
Min Layer Thickness= 0.1
Max Layer Thickness= 6
Number of Layers= 5

--- PoleSwamp.p02 (plan) ---

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Plan Title=Proposed
Short Identifier=PROP
Geom File=g02
Flow File=f01

--- PoleSwamp.p17 (plan) ---

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Plan Title=Existing
Short Identifier=EX
Geom File=g01
Flow File=f01

--- PoleSwamp.f01 (steady flow) ---

Flow Title=USGS Regression Flowrates
Program Version=6.60
Number of Profiles= 5
Profile Names=10-year,25-year,50-year,100-year,500-year
River Rch & RM=Pole Branch,Reach 1         ,13000
     137     199     257     317     471
Boundary for River Rch & Prof#=Pole Branch,Reach 1         , 1
Up Type= 0
Dn Type= 1
Dn Known WS=6.18
Boundary for River Rch & Prof#=Pole Branch,Reach 1         , 2
Up Type= 0
Dn Type= 1
Dn Known WS=8.46
Boundary for River Rch & Prof#=Pole Branch,Reach 1         , 3
Up Type= 0
Dn Type= 1
Dn Known WS=8.46
Boundary for River Rch & Prof#=Pole Branch,Reach 1         , 4
Up Type= 0
Dn Type= 1
Dn Known WS=10.91
Boundary for River Rch & Prof#=Pole Branch,Reach 1         , 5
Up Type= 0
Dn Type= 1
Dn Known WS=14.94
DSS Import GetInterval= 0
DSS Import GetPeak= 0
DSS Import FillOption= 0

--- PoleSwamp.g04 (geometry) ---

Geom Title=Natural Conditions
Program Version=6.60

River Reach=Pole Branch     ,Reach 1
Reach XY= 30
2487103.72760481520920.8647252122486823.21861145519612.111188033
2487255.72552856  518592.11423322487238.20068154518371.596125456
2487046.41745136518137.0660307142486179.56083996517645.224527705
2486031.06498953517437.9209287712486281.00046708516688.304492676
 2486153.1990834516355.7786175982486123.63203509515961.578500213
2486205.28874689515853.6584892932486007.22688687515530.823714399
2485932.70548941515156.0050644982485609.52245771514877.719597683
2485538.65628761 514574.872716922485560.04970744514243.287416417
2485852.83522467513939.7984387872486175.00373642513898.914109884
2486309.98062787513751.6741417022486312.37508154513490.615945239
 2486444.2951828513466.6304722822486364.16189815 512937.85981847
2486459.64969694512525.1999496082486734.63466467 512470.08181731
2486704.34997659512333.8007209662487331.84871354511737.192365862
2487320.34053207511614.8422260342487207.35791646511565.796712537
2487367.58464547511394.3696968382487311.10202409510662.794092707

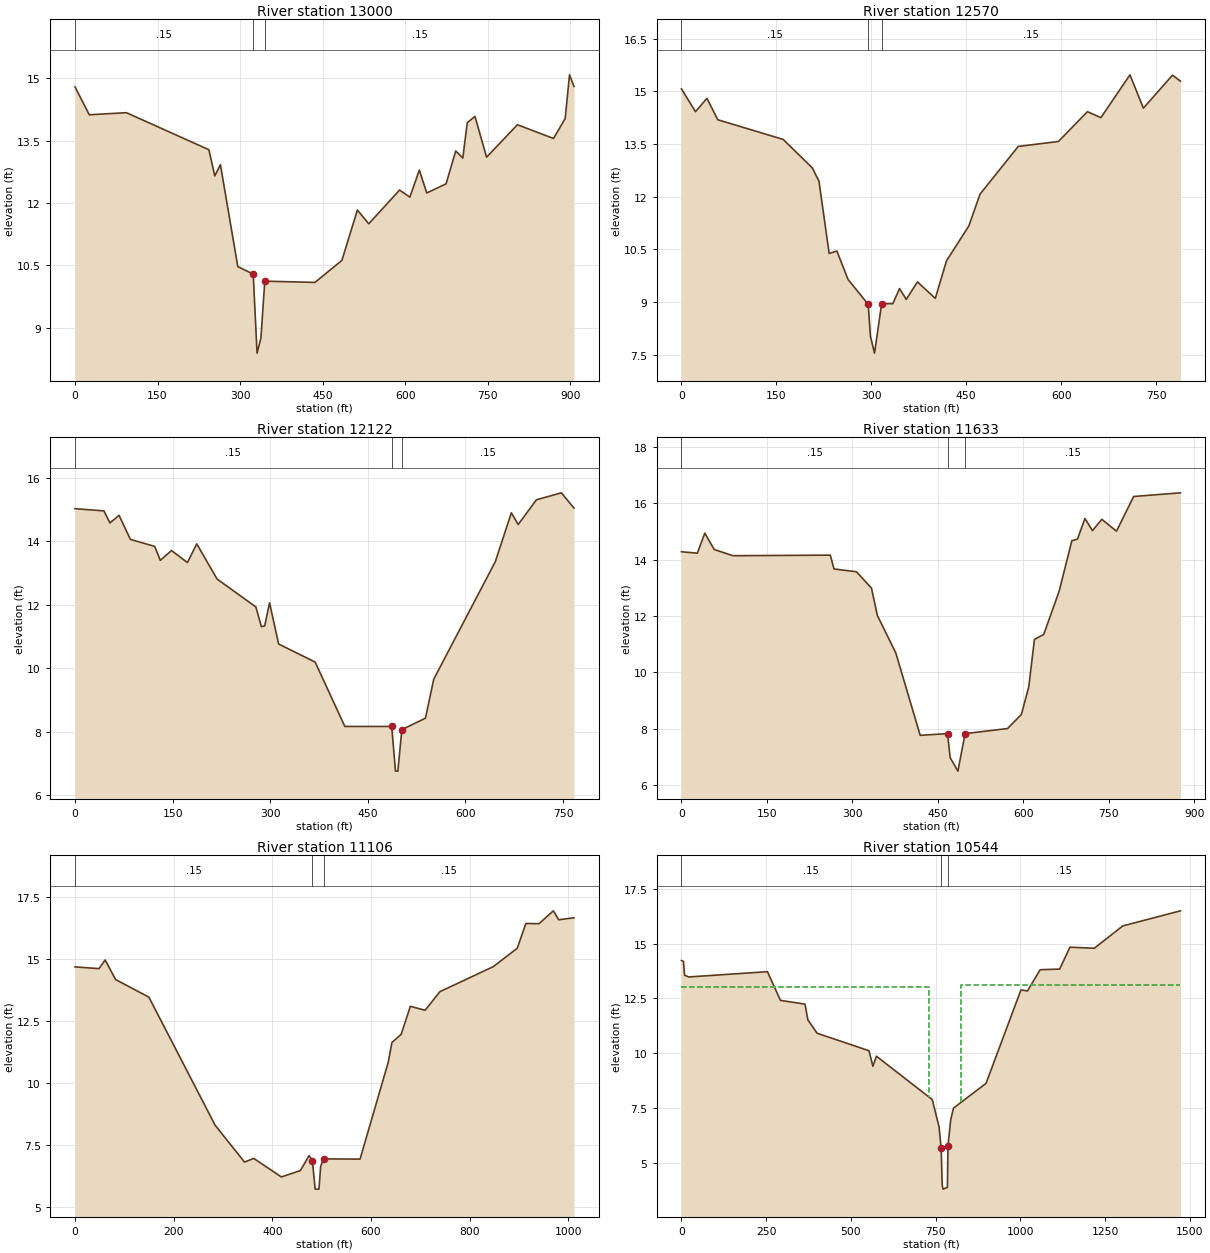
Type RM Length L Ch R = 1 ,13000   ,429.5,429.5,429.5
XS GIS Cut Line= 2
2487390.42992342 520758.661613522486541.50292589521077.595513148
#Sta/Elev= 30
       0   14.79      26   14.12    93.4   14.17   243.3   13.28   254.1   12.65
   264.3   12.92   295.9   10.47   323.9   10.29   330.9    8.39   337.9    8.75
   344.9   10.12   436.1   10.09   485.1   10.62   513.2   11.83   533.9    11.5
   589.9   12.31   608.5   12.14   625.8   12.79   639.3   12.24   674.4   12.46
   691.9   13.25   704.8   13.08   712.9   13.93   726.9   14.08     748    13.1
     804   13.88   869.7   13.55   890.8   14.03   898.7   15.08906.8605    14.8
#Mann= 3 ,-1,0
       0     .15       0   323.9     .05       0   344.9     .15       0
Bank Sta=323.9,344.9
XS Rating Curve= 0 ,0
Exp/Cntr(USF)=0,0
Exp/Cntr=0.3,0.1

Type RM Length L Ch R = 1 ,12570   ,448,448,448
XS GIS Cut Line= 2
 2487321.6402588520344.3602242992486589.96837142520638.279700426
#Sta/Elev= 30
       0   15.07    22.2   14.42    40.3    14.8    57.4   14.19   160.7   13.63
   206.7   12.82   217.3   12.44   233.4   10.38   245.6   10.45   263.2    9.64
   295.1    8.93   298.6    8.02   305.1    7.54   316.3    8.95     334    8.95
   344.6    9.38   355.2    9.07   372.9    9.57   401.1     9.1   418.8   10.17
     454   11.16   471.8   12.07   532.2   13.43   595.6   13.57   641.5   14.42
   662.8   14.25   708.7   15.47   729.9   14.52   775.9   15.46788.5001   15.29
#Mann= 3 ,0,0
       0     .15       0   295.1     .05       0   316.3     .15       0
Bank Sta=295.1,316.3
XS Rating Curve= 0 ,0
Exp/Cntr(USF)=0,0
Exp/Cntr=0.3,0.1

Type RM Length L Ch R = 1 ,12122   ,488.7,488.7,488.7
XS GIS Cut Line= 2
2487350.66423486 519863.308874122486632.92928988520133.380849603
#Sta/Elev= 30
       0   15.03    44.5   14.96    53.7   14.58    67.7   14.82    85.2   14.06
   122.5   13.84   131.1    13.4   148.3   13.71   172.8   13.33   187.1   13.92
   218.4   12.81     278   11.93   286.4   11.31   291.5   11.33     299   12.06
     313   10.76   369.1   10.19   414.7    8.16  486.77    8.16  492.52    6.75
  496.18    6.75   502.3    8.06   538.6    8.42   551.3    9.65     646   13.36
   670.6    14.9   681.1   14.53   709.1   15.31   747.4   15.53766.8652   15.05
#Mann= 3 ,0,0
       0     .15       0  486.77     .05       0   502.3     .15       0
Bank Sta=486.77,502.3
XS Rating Curve= 0 ,0
Exp/Cntr(USF)=0,0
Exp/Cntr=0.3,0.1

Type RM Length L Ch R = 1 ,11633   ,527.7,527.7,527.7
XS GIS Cut Line= 2
2487321.72289463519589.6154403432486447.47308397519534.821797315
#Sta/Elev= 30
       0   14.28    27.9   14.23      41   14.94    57.5   14.36    90.3   14.14
   261.3   14.16   267.8   13.67   307.3   13.57   333.6   12.99   343.9   12.02
   376.3   10.69   419.1    7.77  467.04    7.83   471.7    6.98  485.29     6.5
   497.9    7.83  572.39    8.01   596.7    8.51   609.7    9.49   619.6   11.17
     636   11.35     663   12.88   685.3   14.67   695.2   14.73   708.3   15.46
   721.5   15.03   737.9   15.43   763.7   15.01   793.8   16.24875.9652   16.37
#Mann= 3 ,0,0
       0     .15       0  467.04     .05       0   497.9     .15       0
Bank Sta=467.04,497.9
XS Rating Curve= 0 ,0
Exp/Cntr(USF)=0,0
Exp/Cntr=0.3,0.1

Type RM Length L Ch R = 1 ,11106   ,561.5,561.5,561.5
XS GIS Cut Line= 2
 2487464.5711369519315.6239032792486576.07013757518832.020293943
#Sta/Elev= 30
       0   14.69    48.7   14.62    61.1   14.97    82.3   14.18   149.8   13.47
     284    8.31   343.7    6.82   362.4    6.97   418.4    6.22     457    6.48
   474.5    7.08   481.2    6.88  486.95    5.73   494.6    5.73   498.1    6.66
   504.3    6.95   577.9    6.94   635.1   10.85   642.5   11.64   661.2   11.97
   679.9    13.1   709.8   12.94   739.7   13.69     848    14.7   896.5   15.44
   914.1   16.44   940.7   16.43   969.7   16.95   980.7   16.59  1011.6   16.67
#Mann= 3 ,0,0
       0     .15       0   481.2     .05       0   504.3     .15       0
Bank Sta=481.2,504.3
XS Rating Curve= 0 ,0
Exp/Cntr(USF)=0,0
Exp/Cntr=0.5,0.3

Type RM Length L Ch R = 1 ,10544   ,69.4,69.4,69.4
XS GIS Cut Line= 2
2488028.75582348518452.7326327252486572.26588662518670.416810395
#Sta/Elev= 30
       0   14.23       6   14.19     9.2   13.56    21.2   13.48   253.8   13.72
   292.2   12.41   364.6   12.24   373.1   11.52   400.4   10.91   553.5   10.11
     565     9.4   575.5    9.86   740.2    7.88   760.3    6.63   766.4    5.66
  769.55    3.98  771.89    3.79  784.83    3.87   786.6    5.77   794.7    6.97
   802.8    7.49   898.9    8.62    1002   12.89  1021.2   12.84  1058.6   13.81
  1116.2   13.84  1146.6   14.84  1218.4   14.79  1302.3   15.81  1472.7    16.5
#Mann= 3 ,0,0
       0     .15       0   766.4     .05       0   786.6     .15       0
#XS Ineff= 2 , 0
       0     730   13.03     825       0   13.12
Permanent Ineff=
       F       F
Bank Sta=766.4,786.6
XS Rating Curve= 0 ,0
Exp/Cntr(USF)=0,0
Exp/Cntr=0.5,0.3

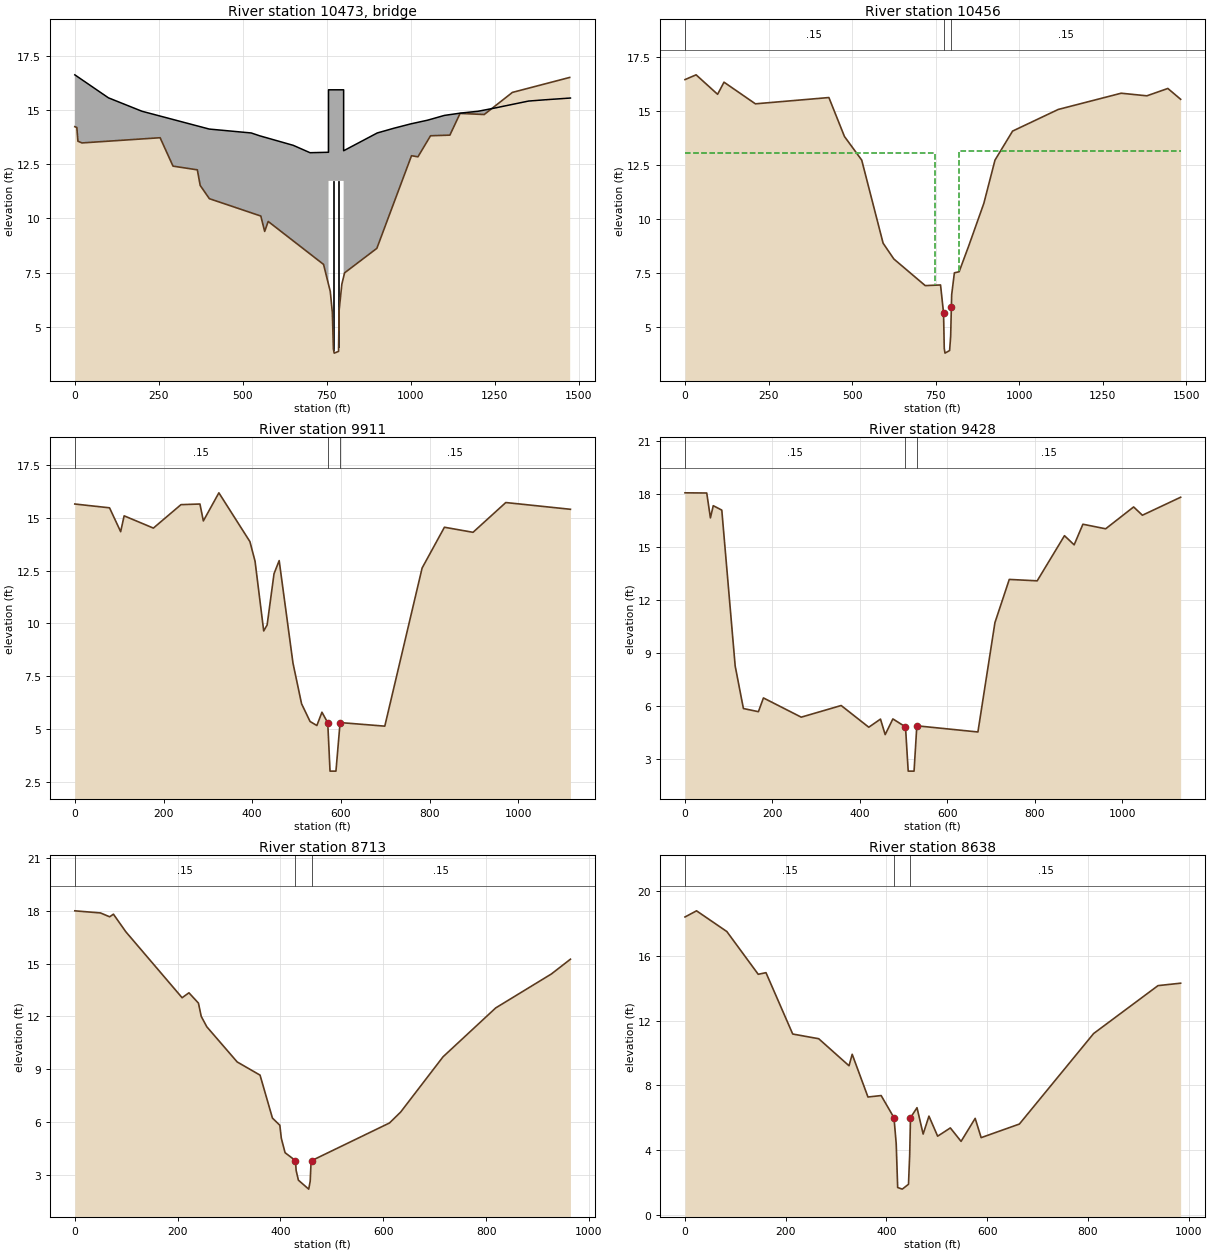
Type RM Length L Ch R = 3 ,10473   ,,,
Node Name=S-22-31 over Lan
Bridge Culvert-0,0,0,0, 0
Deck Dist Width WeirC Skew NumUp NumDn MinLoCord MaxHiCord MaxSubmerge Is_Ogee
20,28,3,0, 23, 23, , , 0.98, 0, 2,2,,
       0     100     200     400     525     550     650     700     755     755
     800     800     900     950    1000    1050    1100    1150    1200    1250
    1350    1400    1475
   16.62   15.56   14.94   14.12   13.94   13.81   13.37   13.03   13.05   15.93
   15.93   13.12   13.94   14.16   14.36   14.53   14.75   14.86   14.94   15.09
   15.41   15.47   15.55
                                                                           11.73
   11.73
                        
       0     100     200     400     525     550     650     700     762     762
     807     807     900     950    1000    1050    1100    1150    1200    1250
    1350    1400    1475
   16.62   15.56   14.94   14.12   13.94   13.81   13.37   13.03   13.05   15.93
   15.93   13.12   13.94   14.16   14.36   14.53   14.75   14.86   14.94   15.09
   15.41   15.47   15.55
                                                                           11.73
   11.73
                        
Pier Skew, UpSta & Num, DnSta & Num=  ,770, 2 ,777, 2 , 0 , 0 , 0 ,,
       1       1
       0   11.73
       1       1
       0   11.73
Pier Skew, UpSta & Num, DnSta & Num=  ,785, 2 ,792, 2 , 0 , 0 , 0 ,,
       1       1
       0   11.73
       1       1
       0   11.73
Abutment Skew #Up #Dn= , 2 , 2
     755   765.4
    11.6       6
     762   770.4
    11.6       8
Abutment Skew #Up #Dn= , 2 , 2
     788     800
    5.79    11.6
     797     807
    5.79    11.6
BR Coef=-1 , 0 , 0 ,, 0 ,,,0.8,0,,0,
WSPro=,,,, 1 ,,,, 0 ,,,, 0 ,,,,-1 ,-1 ,-1 , 0 , 0 , 0 , 0 , 0
BC Design=,, 0 ,, 0 ,,,,,,
BC HTab HWMax=20.93
BC Use User HTab Curves=0
BC User HTab FreeFlow(D)= 0

Type RM Length L Ch R = 1 ,10456   ,527.2,527.2,527.2
XS GIS Cut Line= 2
2488026.09080109518360.1633519022486561.01535596518587.263893491
#Sta/Elev= 30
       0   16.44    33.2   16.66    97.5   15.76   116.7   16.32   210.6   15.32
   430.4   15.61     477   13.81   528.6   12.72   592.6    8.88   624.7    8.15
   718.6    6.92  764.39    6.95   773.4    5.66   775.5    4.02  777.76     3.8
  791.55    3.92   794.7    4.59   796.8    5.95   797.7     6.5   805.8    7.51
     820    7.56   849.3    8.78   893.9   10.72   927.3   12.72   979.9   14.06
  1116.5   15.06  1304.7   15.81  1381.6   15.69  1444.4   16.03  1482.6   15.53
#Mann= 3 ,0,0
       0     .15       0   773.4     .05       0   796.8     .15       0
#XS Ineff= 2 , 0
       0     748   13.03     821       0   13.12
Permanent Ineff=
       F       F
Bank Sta=773.4,796.8
XS Rating Curve= 0 ,0
Exp/Cntr(USF)=0,0
Exp/Cntr=0.5,0.3

Type RM Length L Ch R = 1 ,9911    ,482.5,482.5,482.5
XS GIS Cut Line= 4
2487280.26256008517605.2741643312487007.90043863518034.190891016
2486793.44207529518390.1917741662486687.64976465518552.965671943
#Sta/Elev= 30
       0   15.65    78.3   15.47   103.4   14.34   111.2   15.09   177.2   14.51
   239.4   15.62   282.2   15.65   289.9   14.85   324.9   16.18   394.9   13.87
   406.5   12.94     426    9.64   433.7    9.92   449.3   12.35   460.9   12.97
     492    8.12   511.4    6.19   530.6    5.35   545.9    5.16   557.4    5.79
  570.45    5.29   575.6       3  588.95       3  598.28     5.3   699.1    5.13
   783.3   12.62   833.6   14.55   898.1   14.31     972   15.721117.824    15.4
#Mann= 3 ,0,0
       0     .15       0  570.45     .05       0  598.28     .15       0
Bank Sta=570.45,598.28
XS Rating Curve= 0 ,0
Exp/Cntr(USF)=0,0
Exp/Cntr=0.3,0.1

Type RM Length L Ch R = 1 ,9428    ,534.8,534.8,534.8
XS GIS Cut Line= 2
2486840.35942608517445.1468862852486192.21859464518374.466460771
#Sta/Elev= 30
       0   18.08    49.7   18.07    58.1   16.66    64.6   17.35    84.1    17.1
   114.7    8.26   133.5    5.85   167.8    5.67   179.3    6.45   265.7    5.36
     357    6.02   420.1    4.79   446.9    5.25   457.6    4.37   475.2    5.26
  504.04    4.81  510.23     2.3  523.62     2.3  529.98    4.87   669.6    4.52
   708.5   10.72   741.3   13.17   805.1   13.09   867.5   15.65   889.6   15.13
   909.6    16.3   961.6   16.04  1025.6   17.28  1045.6   16.811133.014   17.83
#Mann= 3 ,0,0
       0     .15       0  504.04     .05       0  529.98     .15       0
Bank Sta=504.04,529.98
XS Rating Curve= 0 ,0
Exp/Cntr(USF)=0,0
Exp/Cntr=0.3,0.1

Type RM Length L Ch R = 1 ,8713    ,75.4,75.4,75.4
XS GIS Cut Line= 5
2486475.67499602517312.0289722652486025.16383505517613.371183726
2485921.82201055517683.4372398442485816.46120685517767.337042368
2485699.87730714517880.622782793
#Sta/Elev= 30
       0      18    49.9   17.88    67.8   17.66    75.1   17.81    99.2   16.81
   208.7   13.06     222   13.34   238.7   12.81   240.5   12.75   245.9      12
   256.7   11.41   315.8    9.41   360.3    8.66   384.4    6.22   398.8    5.81
  401.69    5.07  409.01    4.25  429.25     3.8  430.52    3.24   434.9    2.69
  454.95    2.18  457.87    2.63  459.46    3.66  460.75     3.8   612.1    5.94
   633.8    6.56   716.2     9.7   818.7   12.48     927   14.41   964.1   15.25
#Mann= 3 ,0,0
       0     .15       0  429.25     .05       0  460.75     .15       0
Bank Sta=429.25,460.75
XS Rating Curve= 0 ,0
Exp/Cntr(USF)=0,0
Exp/Cntr=0.3,0.1

Type RM Length L Ch R = 1 ,8638    ,606,606,606
XS GIS Cut Line= 6
2486434.42239804517261.5771611622486214.94788033517399.359387984
2486018.43390436517527.228070975 2485873.0674016517627.504038162
 2485755.9666077517732.4909568282485646.86592787517845.022660153
#Sta/Elev= 30
       0    18.4    22.9   18.78    83.1    17.5   145.4   14.86   160.8   14.96
   213.9   11.17   265.5   10.88   325.7    9.21     332    9.92   363.3    7.28
   389.5    7.37     415       6   419.4    4.39   422.3    1.69  431.47    1.59
   443.8    1.89   446.2    3.73  447.74       6   460.7    6.62   472.9    4.99
   484.4     6.1   501.7    4.86   526.9    5.37   548.2    4.54   576.2    5.96
   588.1    4.77     664    5.61   811.4    11.2   939.3   14.16   984.2   14.31
#Mann= 3 ,0,0
       0     .15       0     415     .05       0  447.74     .15       0
Bank Sta=415,447.74
XS Rating Curve= 0 ,0
Exp/Cntr(USF)=0,0
Exp/Cntr=0.3,0.1

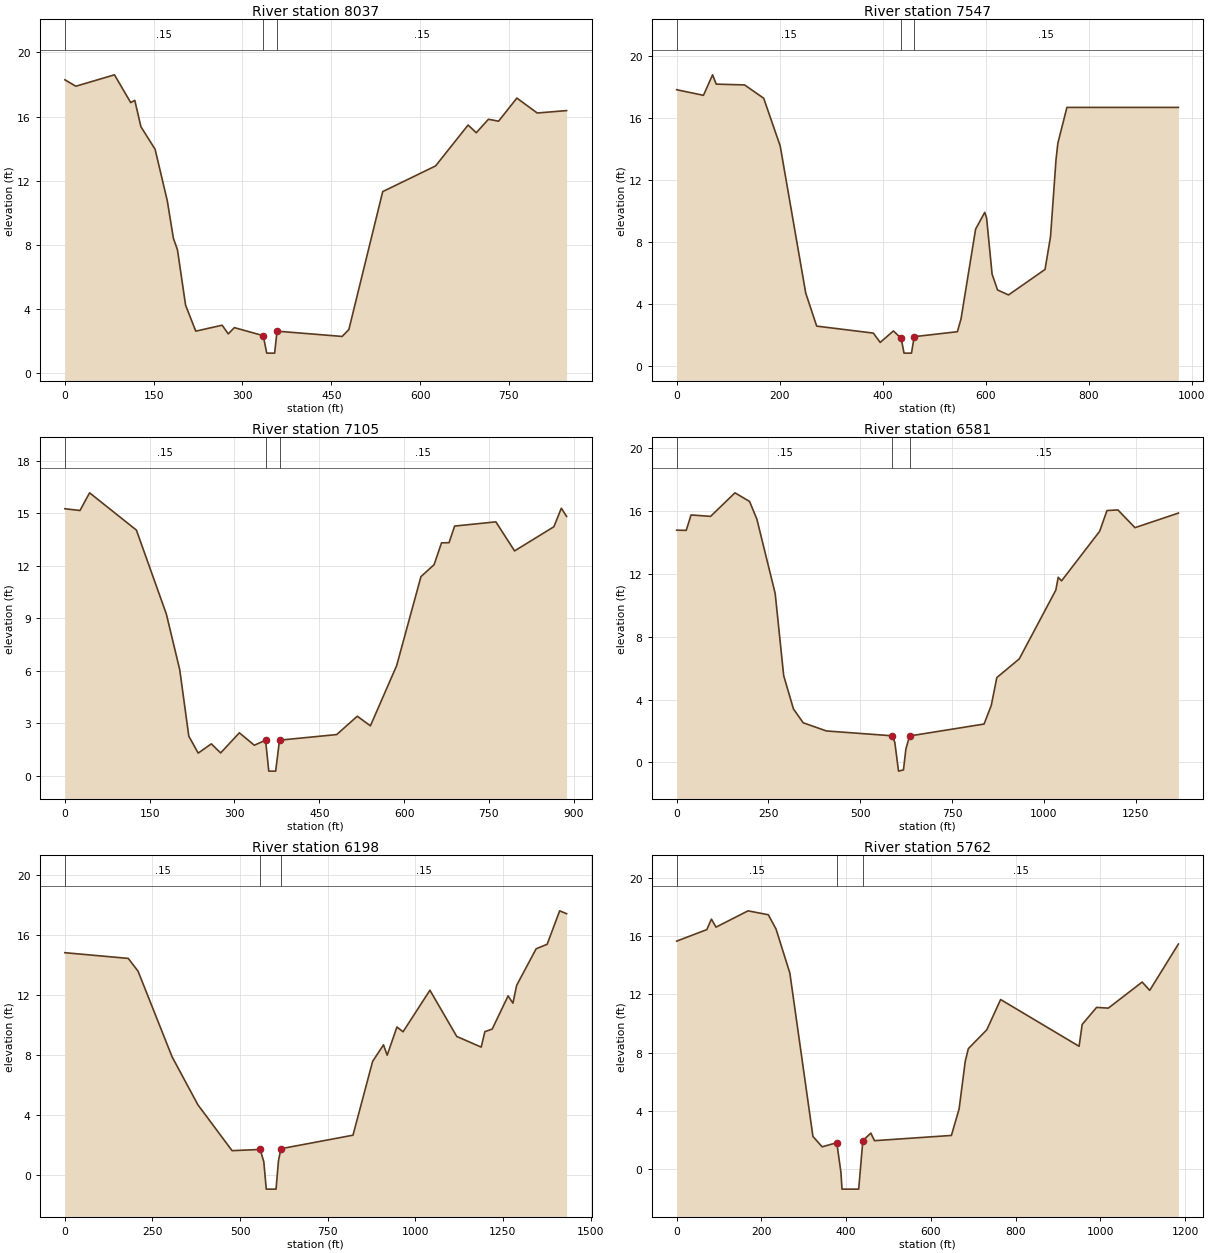
Type RM Length L Ch R = 1 ,8037    ,490.3,490.3,490.3
XS GIS Cut Line= 2
2486575.10066564517062.9221442292485765.18938975516813.250247151
#Sta/Elev= 30
       0   18.29    18.5   17.89    83.8    18.6   111.2   16.87   118.1   17.01
   128.4   15.37   152.4   13.96     173   10.75   183.3    8.41   190.2    7.69
   203.9    4.24   221.1    2.62   265.7    2.99     276    2.45   286.3    2.84
     335    2.34     341    1.25  354.34    1.25   358.4    2.62   468.4    2.29
   479.7    2.72   536.9   11.32   626.2   12.92   681.1   15.47   694.9   14.99
   715.5   15.83   732.6   15.71   763.5   17.15   797.9   16.22   847.5   16.37
#Mann= 3 ,0,0
       0     .15       0     335     .05       0   358.4     .15       0
Bank Sta=335,358.4
XS Rating Curve= 0 ,0
Exp/Cntr(USF)=0,0
Exp/Cntr=0.3,0.1

Type RM Length L Ch R = 1 ,7547    ,442.2,442.2,442.2
XS GIS Cut Line= 2
2486631.69056973 516325.069535042485730.62125125516695.685358506
#Sta/Elev= 30
       0   17.82      52   17.46    69.7   18.78    76.8   18.18   131.9   18.13
     169   17.27     201    14.2   250.6    4.72   271.9    2.59   381.9    2.14
   395.2    1.54   420.9    2.28     436     1.8  441.45     .85     456     .85
   461.2    1.91   545.1    2.23   552.2    3.06   580.5    8.84   598.3    9.92
   601.8    9.57   612.5    5.94   623.1    4.92   644.4     4.6   715.3    6.24
     726    8.36   736.6    13.3   740.2   14.37   757.8   16.68   974.3   16.68
#Mann= 3 ,0,0
       0     .15       0     436     .05       0   461.2     .15       0
Bank Sta=436,461.2
XS Rating Curve= 0 ,0
Exp/Cntr(USF)=0,0
Exp/Cntr=0.3,0.1

Type RM Length L Ch R = 1 ,7105    ,488.9,488.9,488.9
XS GIS Cut Line= 2
2486505.55728047516021.9154288322485626.27799076516142.012112304
#Sta/Elev= 30
       0   15.25    26.7   15.15    43.7   16.16   126.5   14.03   179.5    9.23
   203.2    6.04   219.2    2.25   235.8    1.28     259    1.81   275.5    1.29
   308.6    2.44   335.1    1.73  354.98    2.02  360.65     .25  372.82     .25
  379.63    2.02   480.8    2.34   517.2    3.39   540.4    2.84   586.8    6.28
   629.8   11.37     653   12.05   666.2    13.3   679.5   13.31   689.4   14.26
   762.3    14.5   795.4   12.84   864.9   14.22   878.1   15.28   887.4   14.81
#Mann= 3 ,0,0
       0     .15       0  354.98     .05       0  379.63     .15       0
Bank Sta=354.98,379.63
XS Rating Curve= 0 ,0
Exp/Cntr(USF)=0,0
Exp/Cntr=0.3,0.1

Type RM Length L Ch R = 1 ,6581    ,383.2,383.2,383.2
XS GIS Cut Line= 4
2486681.46067437515530.3265502632486162.25504659515609.121984289
2486043.24057543515633.4776043042485331.52132952  515738.8667871
#Sta/Elev= 30
       0   14.79      26   14.78    39.2   15.76    92.3   15.67   158.7   17.17
   198.5   16.62   218.4   15.49   268.2   10.76   291.4    5.52     318     3.4
   344.5    2.52   407.6       2   587.3    1.69     594    1.26   604.1    -.56
   617.5    -.48   624.1     .85   634.2    1.68     837    2.44   856.5    3.62
   871.7     5.4   932.8    6.59  1032.3   10.97  1038.9   11.79  1047.9   11.56
  1151.7   14.72  1171.6   16.04  1201.4   16.08  1247.9   14.95  1366.1   15.88
#Mann= 3 ,0,0
       0     .15       0   587.3     .05       0   634.2     .15       0
Bank Sta=587.3,634.2
XS Rating Curve= 0 ,0
Exp/Cntr(USF)=0,0
Exp/Cntr=0.3,0.1

Type RM Length L Ch R = 1 ,6198    ,435.7,435.7,435.7
XS GIS Cut Line= 2
2486540.67683071 515073.393535222485192.85782574515556.168369707
#Sta/Elev= 30
       0   14.81   180.9   14.43   208.8   13.58     306    7.87   379.5    4.68
   477.1    1.62   557.3     1.7   567.7     .87   574.7   -.943   602.6   -.943
   609.5     .94   616.5    1.75   822.1    2.65   878.2    7.57   909.2    8.67
   919.7    7.98   947.6    9.86     965    9.54  1041.7   12.31  1118.3    9.23
    1188    8.52  1198.5    9.55  1219.4    9.72  1264.7   11.93  1278.6   11.45
  1289.1   12.63  1344.8   15.07  1376.2   15.37  1411.9    17.6  1431.7   17.41
#Mann= 3 ,0,0
       0     .15       0   557.3     .05       0   616.5     .15       0
Bank Sta=557.3,616.5
XS Rating Curve= 0 ,0
Exp/Cntr(USF)=0,0
Exp/Cntr=0.3,0.1

Type RM Length L Ch R = 1 ,5762    ,410.1,410.1,410.1
XS GIS Cut Line= 2
  2486073.703455514779.7451813452485003.79450899515287.296641258
#Sta/Elev= 30
       0   15.65    71.1   16.44      82   17.16    92.9   16.61   168.5   17.73
   216.3   17.46   234.5   16.48   267.1   13.46   321.6    2.24   343.4    1.53
   377.9    1.81   387.7    -.23   390.2  -1.376   429.6  -1.376   439.4    1.95
   458.2    2.47   466.9    1.95   648.4    2.31   666.6    4.13   681.1     7.4
   688.4    8.27   731.9    9.56   764.6   11.64   949.8    8.43   957.1    9.93
   991.1    11.1  1018.8   11.05  1098.7   12.84  1116.5   12.271184.193   15.45
#Mann= 3 ,0,0
       0     .15       0   377.9     .05       0   439.4     .15       0
Bank Sta=377.9,439.4
XS Rating Curve= 0 ,0
Exp/Cntr(USF)=0,0
Exp/Cntr=0.3,0.1

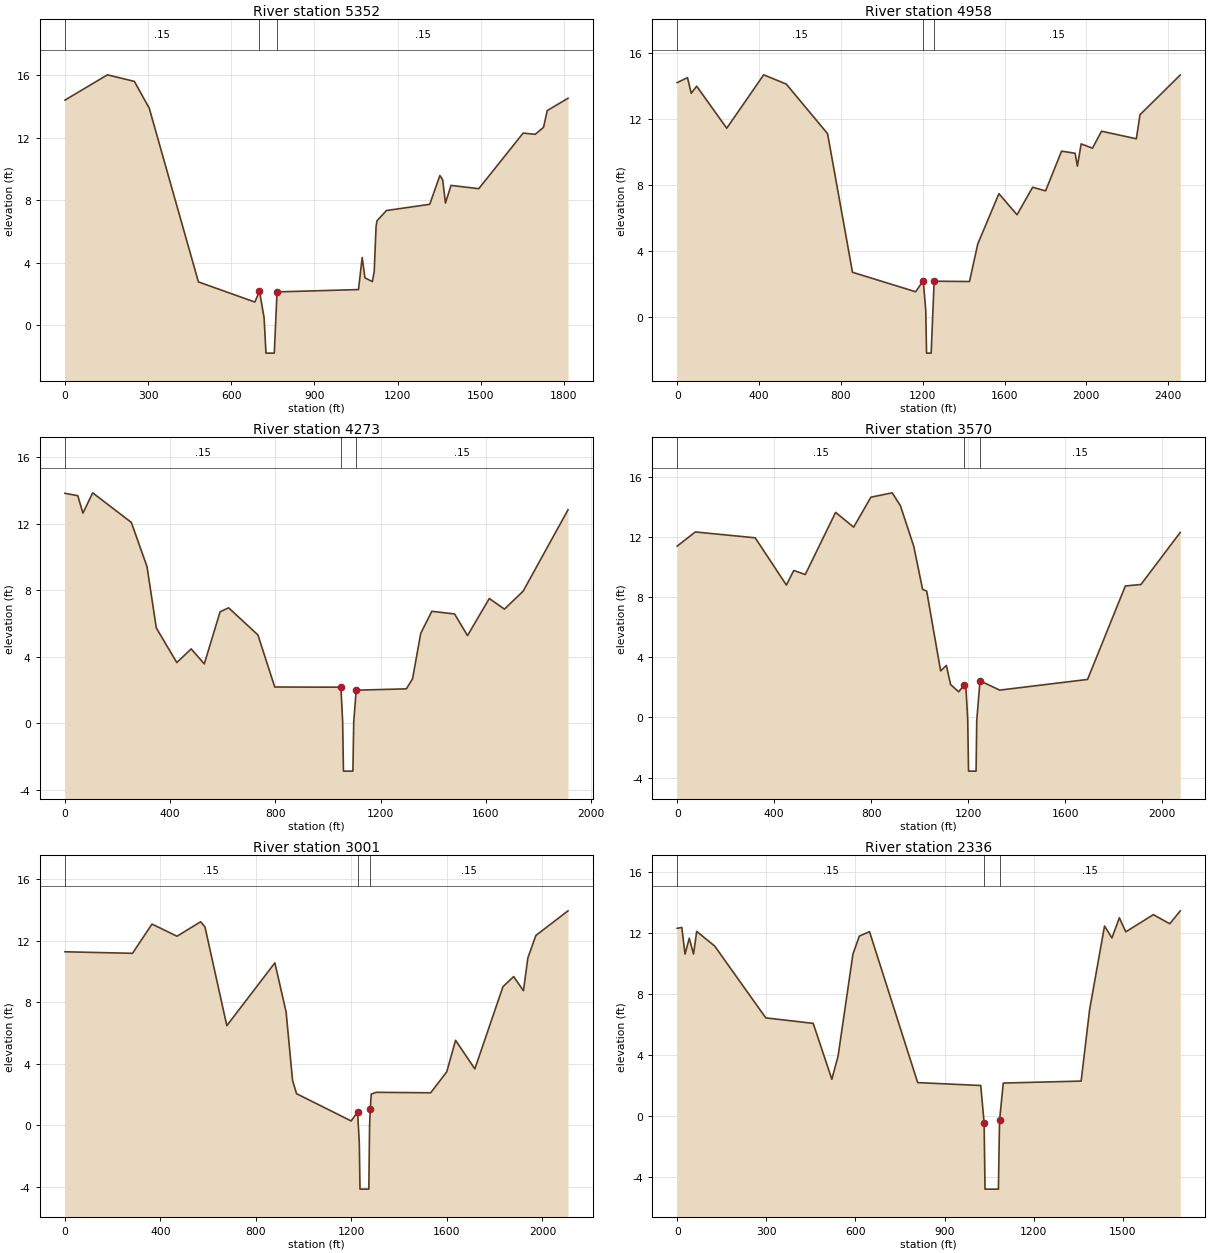
Type RM Length L Ch R = 1 ,5352    ,393.9,393.9,393.9
XS GIS Cut Line= 3
2486264.39814074514743.5825250772485878.51547585514661.783350034
2484482.44719248514399.922809542
#Sta/Elev= 30
       0   14.41   153.3   16.03   250.5   15.61   304.2   13.89   481.5    2.77
   685.1    1.48   701.8    2.18   718.5     .47   725.2   -1.79   755.2   -1.79
   765.2    2.13    1059    2.28  1072.3    4.33  1082.3    3.03    1109    2.79
  1115.7    3.43  1122.4    6.31  1125.7    6.68  1159.7    7.34    1316    7.74
  1352.7    9.58  1362.7    9.31  1372.7    7.82  1392.8    8.95  1492.9    8.74
  1653.1    12.3  1696.5   12.22  1726.6   12.67  1739.9   13.74  1814.9   14.53
#Mann= 3 ,0,0
       0     .15       0   701.8     .05       0   765.2     .15       0
Bank Sta=701.8,765.2
XS Rating Curve= 0 ,0
Exp/Cntr(USF)=0,0
Exp/Cntr=0.3,0.1

Type RM Length L Ch R = 1 ,4958    ,685.4,685.4,685.4
XS GIS Cut Line= 3
2486629.52253072514858.3479529692485486.27338469514184.555472451
2484479.51868403513668.103385752
#Sta/Elev= 30
       0   14.23    50.5   14.53    68.5   13.58    95.2   14.01   242.2   11.46
   422.7    14.7   533.1   14.14   734.9   11.13   856.8    2.72  1165.3    1.54
  1202.5    2.21  1214.8     .41  1218.6  -2.184  1241.2  -2.184  1255.7    2.18
  1428.5    2.16    1469    4.44  1572.3    7.49  1660.8    6.21    1737    7.88
  1800.4    7.66  1878.5   10.07  1944.7    9.94  1955.8    9.16  1974.2   10.51
  2029.4   10.25  2073.8   11.28  2243.9   10.82  2261.8   12.282458.526   14.69
#Mann= 3 ,0,0
       0     .15       0  1202.5     .05       0  1255.7     .15       0
Bank Sta=1202.5,1255.7
XS Rating Curve= 0 ,0
Exp/Cntr(USF)=0,0
Exp/Cntr=0.3,0.1

Type RM Length L Ch R = 1 ,4273    ,702.3,702.3,702.3
XS GIS Cut Line= 3
2486715.05082058514820.1591343622486147.09063956 513951.69223464
2485611.61838361513259.911477382
#Sta/Elev= 30
       0   13.83    48.8   13.69    68.4   12.64   105.5   13.86   252.5   12.08
   312.1    9.42   347.3    5.74   425.2    3.66     480    4.48   529.8    3.58
   589.8    6.71   622.2    6.95   733.6    5.32   797.6    2.19  1049.1    2.18
  1055.7     .13  1058.8  -2.865  1094.7  -2.865  1097.8     .06  1107.2       2
    1298    2.08  1321.4    2.68  1352.7    5.42  1394.8    6.74  1481.3    6.58
  1530.4    5.28  1613.3    7.51  1670.7    6.87  1741.9    7.95  1912.5   12.84
#Mann= 3 ,0,0
       0     .15       0  1049.1     .05       0  1107.2     .15       0
Bank Sta=1049.1,1107.2
XS Rating Curve= 0 ,0
Exp/Cntr(USF)=0,0
Exp/Cntr=0.3,0.1

Type RM Length L Ch R = 1 ,3570    ,569.5,569.5,569.5
XS GIS Cut Line= 3
2487633.72801891513737.383455748  2486317.361452513407.813556947
2485622.71263932513231.862931212
#Sta/Elev= 30
       0   11.38    74.7   12.32   321.6   11.93   450.1    8.79   480.5    9.76
   527.9    9.49     653   13.62   727.4   12.64   798.4   14.63   886.4   14.92
   920.2   14.06   975.1   11.37  1011.5    8.51  1028.4    8.39  1085.9    3.09
  1109.6    3.45  1126.9    2.18  1160.3     1.7    1184    2.17  1190.7    1.82
  1197.5    -.13  1200.9  -3.573    1232  -3.573  1234.7    -.22  1248.2    2.43
  1329.4    1.81  1691.5    2.52  1847.2    8.73  1911.5    8.832073.582   12.29
#Mann= 3 ,0,0
       0     .15       0    1184     .05       0  1248.2     .15       0
Bank Sta=1184,1248.2
XS Rating Curve= 0 ,0
Exp/Cntr(USF)=0,0
Exp/Cntr=0.3,0.1

Type RM Length L Ch R = 1 ,3001    ,665.3,665.3,665.3
XS GIS Cut Line= 2
2487595.41886734513161.1098337192485540.30032815512696.020476818
#Sta/Elev= 30
       0   11.28     283   11.18   364.6   13.08   469.5   12.29   568.3   13.23
   586.6   12.89     678    6.48   879.3   10.56   926.4    7.36   953.3    2.93
   970.1    2.06  1198.8     .29  1225.7     .86 1232.95   -1.16  1235.8  -4.139
  1272.8  -4.139  1275.9    -.06  1278.7    1.05  1282.9    2.03  1303.4    2.15
  1531.8    2.12  1599.1    3.48  1636.1    5.53  1716.8    3.67  1834.6    9.01
  1879.4    9.67  1920.5    8.75  1938.9   10.88  1972.5   12.342107.088   13.94
#Mann= 3 ,0,0
       0     .15       0  1225.7     .05       0  1278.7     .15       0
Bank Sta=1225.7,1278.7
XS Rating Curve= 0 ,0
Exp/Cntr(USF)=0,0
Exp/Cntr=0.3,0.1

Type RM Length L Ch R = 1 ,2336    ,623.1,623.1,623.1
XS GIS Cut Line= 4
 2487700.2747667512896.8843137272486826.85863502512517.322019554
2486615.54438259512419.1510161372486149.49662902512217.592922881
#Sta/Elev= 30
       0   12.32    15.6   12.38    26.4   10.63    40.7   11.67      55   10.63
    65.7   12.12   126.5   11.15   298.2    6.44   457.8    6.08   520.5    2.41
   541.5    3.93   591.5   10.63     613   11.81   647.3    12.1   809.4    2.19
  1021.6       2    1033    -.46    1036  -4.805  1081.1  -4.805  1084.9    -.29
  1097.5    2.16  1359.5    2.29  1388.1    6.99  1438.2   12.47  1463.2   11.69
  1488.2   13.01  1509.6   12.09  1602.6   13.22  1657.8   12.62  1693.1   13.47
#Mann= 3 ,0,0
       0     .15       0    1033     .05       0  1084.9     .15       0
Bank Sta=1033,1084.9
XS Rating Curve= 0 ,0
Exp/Cntr(USF)=0,0
Exp/Cntr=0.3,0.1