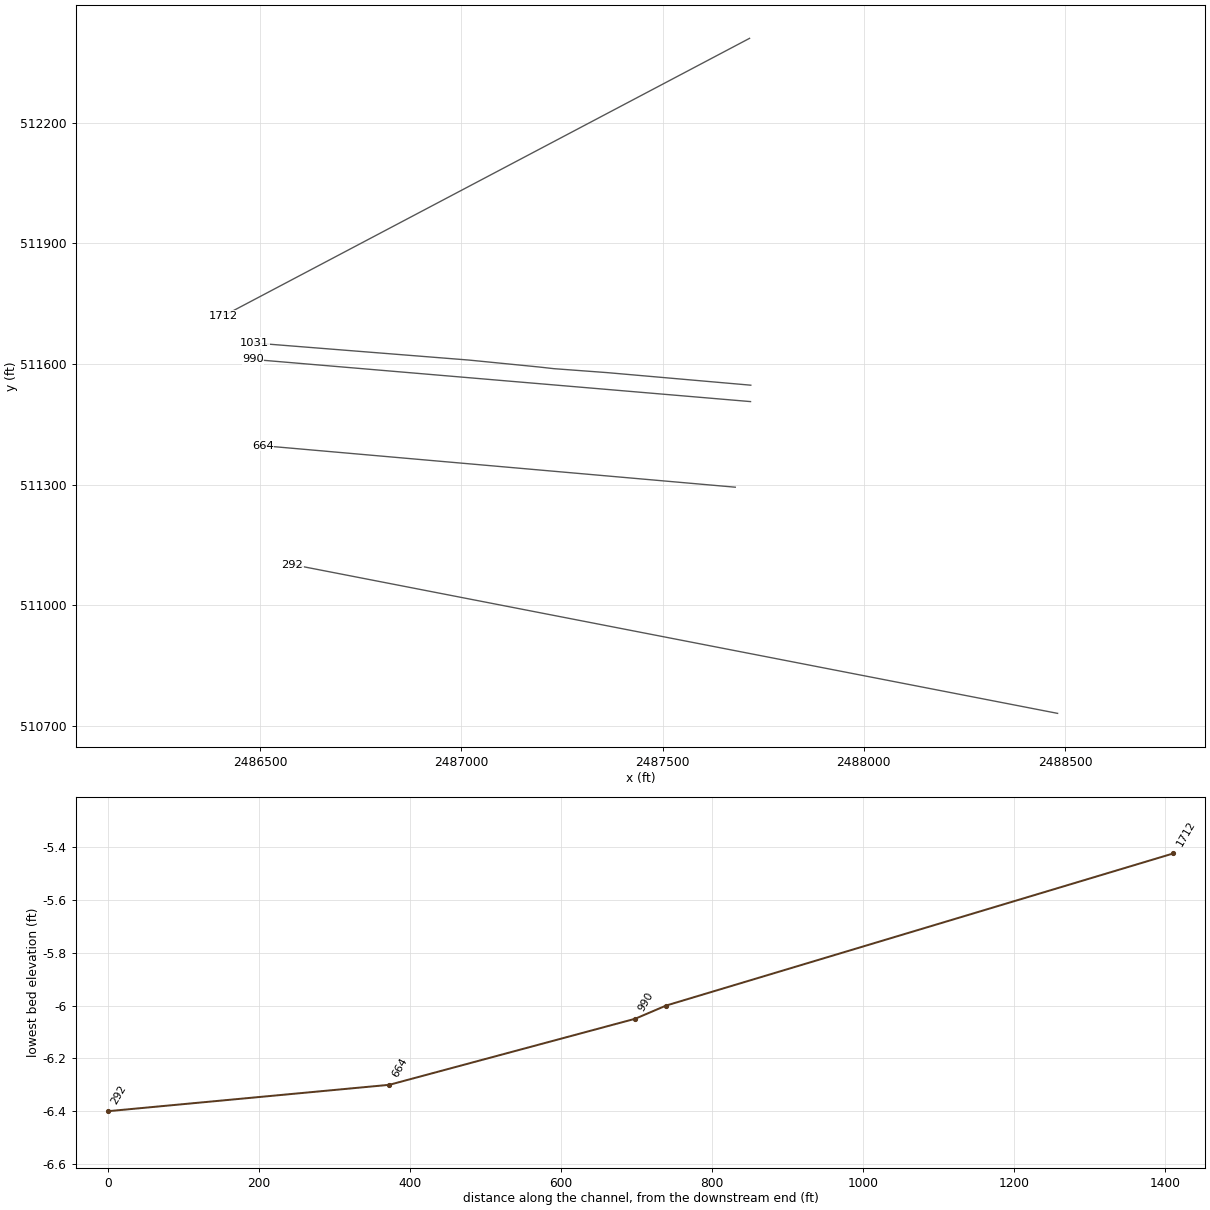
HEC-RAS study PoleSwamp.prj: S-22-24 Pole Swamp

--- PoleSwamp.g04 (geometry) --- (continued)

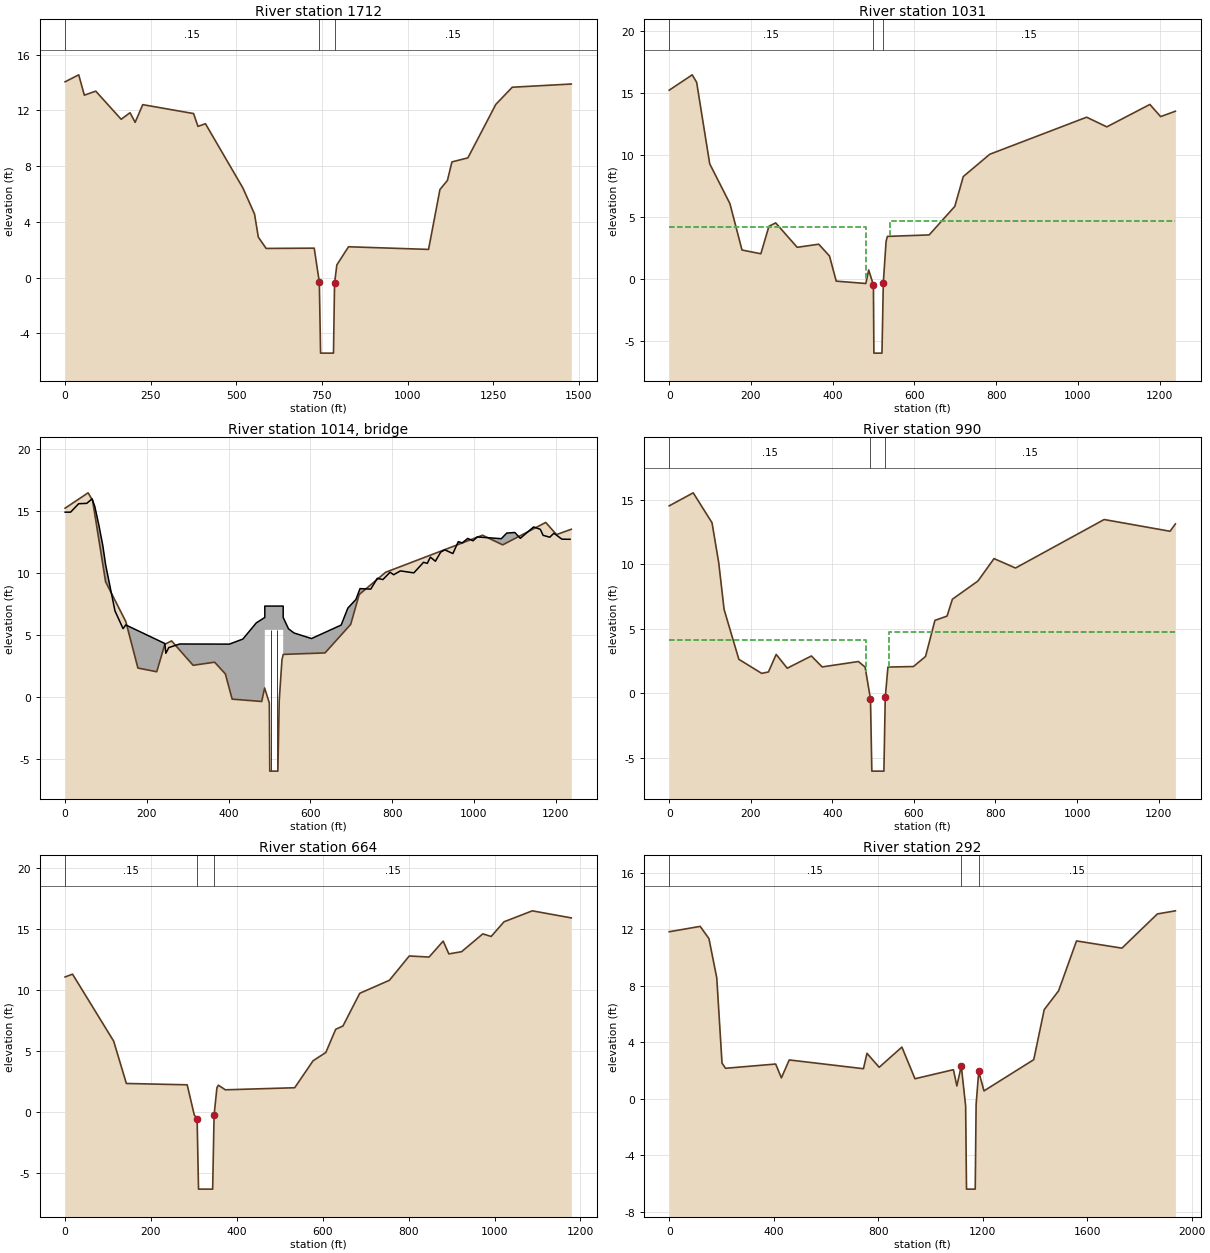
Type RM Length L Ch R = 1 ,1712    ,671.9,671.9,671.9
XS GIS Cut Line= 2
2487715.94070833512409.4554444842486408.46707111511719.763100854
#Sta/Elev= 30
       0   14.05    39.8   14.55    56.2   13.09    89.5   13.38   163.7   11.36
   189.7   11.83   204.5   11.14   226.8   12.41   375.2   11.77     388   10.85
   409.9   11.04   519.2    6.43   553.2    4.56   564.3     2.9   587.1    2.09
   727.5    2.11   742.4    -.32   746.1  -5.424   783.8  -5.424   786.9    -.42
   793.6     .91   827.7    2.21  1061.4    2.02  1094.7    6.32  1116.5    6.97
  1129.7     8.3  1176.3    8.59  1257.9   12.43  1305.9   13.66  1478.2   13.89
#Mann= 3 ,0,0
       0     .15       0   742.4     .05       0   786.9     .15       0
Bank Sta=742.4,786.9
XS Rating Curve= 0 ,0
Exp/Cntr(USF)=0,0
Exp/Cntr=0.5,0.3

Type RM Length L Ch R = 1 ,1031    ,41,41,41
XS GIS Cut Line= 6
2487719.03749652511547.4110224472487362.22491947511578.645933423
2487229.57411857511588.4816872382487192.13871377 511592.68695481
2487018.58202176511609.8420645142486485.34718058511652.252592143
#Sta/Elev= 30
       0   15.22    56.3   16.46    67.2   15.85    99.1    9.28   148.5    6.07
   178.1    2.32   224.2    2.02     244    4.24   260.5    4.51   313.1    2.54
   365.8    2.79   392.1    1.84   408.6    -.19     481    -.38  488.01     .71
  499.59     -.5   500.7      -6   520.5      -6   523.8    -.31   530.5       3
   533.7    3.42   635.9    3.54   698.6    5.84   719.4    8.25   784.2   10.05
  1021.1   13.04  1070.5   12.26  1175.8   14.07  1202.1   13.09  1238.2   13.52
#Mann= 3 ,0,0
       0     .15       0  499.59     .05       0   523.8     .15       0
#XS Ineff= 2 , 0
           482.5     4.2   539.5             4.7
Permanent Ineff=
       F       F
Bank Sta=499.59,523.8
XS Rating Curve= 0 ,0
Exp/Cntr(USF)=0,0
Exp/Cntr=0.5,0.3

Type RM Length L Ch R = 3 ,1014    ,,,
BEGIN DESCRIPTION:
S-22-744 over Tributary to N Santee River. Bridge Data taken from Inspection Reports.
END DESCRIPTION:
Node Name=C-22-744 Trib to
Bridge Culvert-0,0,0,0, 0
Deck Dist Width WeirC Skew NumUp NumDn MinLoCord MaxHiCord MaxSubmerge Is_Ogee
5.975623,23,3,0, 60, 60, , , 0.98, 0, 2,2,,
       0    13.4    33.1    52.9      66    72.6    82.5    92.4      99     122
   141.8   148.4     244   246.4   253.7   280.1   401.9   434.9   467.8   488.5
   488.5   533.5   533.5   546.4     560   602.8   675.3   691.7   711.5   721.4
   747.7   763.7   777.3   794.9   803.7   820.2   853.1   876.7     886   893.5
   905.8   918.9   928.8   948.6   961.8   971.6   984.8     998  1007.9  1067.1
  1080.3  1100.1  1113.5  1146.2  1162.6  1169.2  1185.7  1195.6  1215.3  1235.2
    14.9    14.9   15.58   15.61   15.97   15.37   13.87   12.18   10.68    6.93
     5.5     5.8     4.3    3.51    3.97    4.26    4.25    4.66    5.97     6.4
    7.32    7.32     6.4    5.49    5.15     4.7    5.79    7.16    7.86    8.73
    8.69    9.56    9.46   10.05    9.85   10.16      10   10.85   10.77   11.27
   10.94   11.68   11.86   11.56   12.52   12.42   12.78   12.59    12.9   12.76
   13.21   13.26   12.79   13.71   13.51   13.03   12.88    13.2   12.72   12.71
                                                                                
                                                                                
     5.4     5.4
                                                                                
                                                                                
                                                                                
       0    13.4    33.1    52.9      66    72.6    82.5    92.4      99     122
   148.4     155     257   280.1   336.1   401.9   434.9   467.8   488.5   488.5
   533.5   533.5   546.4     560   602.8   675.3   691.7   711.5   721.4   747.7
   763.7   777.3   794.9   803.7   820.2   853.1   876.7     886   893.5   905.8
   918.9   928.8   948.6   961.8   971.6   984.8     998  1007.9  1014.4  1067.1
  1080.3  1100.1  1113.5  1146.2  1162.6  1169.2  1185.7  1195.6  1215.3  1235.2
    14.9    14.9   15.58   15.61   15.97   15.37   13.87   12.18   10.68    6.93
    4.89    4.54    3.95    4.26    4.07    4.25    4.66    5.97     6.4    7.32
    7.32     6.4    5.49    5.15     4.7    5.79    7.16    7.86    8.73    8.69
    9.56    9.46   10.05    9.85   10.16      10   10.85   10.77   11.27   10.94
   11.68   11.86   11.56   12.52   12.42   12.78   12.59    12.9    12.7   12.76
   13.21   13.26   12.79   13.71   13.51   13.03   12.88    13.2   12.72   12.71
                                                                                
                                                                             5.4
     5.4
                                                                                
                                                                                
                                                                                
Pier Skew, UpSta & Num, DnSta & Num=  ,503.5, 2 ,503.5, 2 , 0 , 0 , 0 ,,
     .83     .83
       0     5.4
     .83     .83
       0     5.4
Pier Skew, UpSta & Num, DnSta & Num=  ,518.5, 2 ,518.5, 2 , 0 , 0 , 0 ,,
     .83     .83
       0     5.4
     .83     .83
       0     5.4
BR Coef=-1 ,-1 ,-1 ,0.9, 0 ,,,0.8,0,1.2,0,
WSPro=,,,, 1 ,,,, 0 ,,,, 0 ,,,,-1 ,-1 ,-1 , 0 , 0 , 0 , 0 , 0
BC Design=,, 0 ,, 0 ,,,,,,
BC HTab HWMax=12.32
BC Use User HTab Curves=0
BC User HTab FreeFlow(D)= 0

Type RM Length L Ch R = 1 ,990     ,325.6,325.6,325.6
XS GIS Cut Line= 2
2487718.36977016511506.643670259 2486481.7739274511611.497879967
#Sta/Elev= 30
       0   14.52    58.9   15.53     105   13.21   121.4   10.12   134.6    6.49
   170.8    2.62   226.8    1.53   243.3    1.64   262.3       3   289.4    1.93
   348.6    2.88     375    2.03   463.9    2.45   480.3    2.02   493.5    -.45
   496.8   -6.05   526.4   -6.05   529.7    -.34   536.3    2.02   598.8    2.06
   628.5    2.84   651.5    5.64   681.2    5.97   694.3    7.28   756.9    8.69
   796.4   10.43   849.1     9.7  1066.4   13.46    1228   12.55    1241   13.12
#Mann= 3 ,0,0
       0     .15       0   493.5     .05       0   529.7     .15       0
#XS Ineff= 2 , 0
           482.5     4.1   539.5             4.7
Permanent Ineff=
       F       F
Bank Sta=493.5,529.7
XS Rating Curve= 0 ,0
Exp/Cntr(USF)=0,0
Exp/Cntr=0.5,0.3

Type RM Length L Ch R = 1 ,664     ,373,373,373
XS GIS Cut Line= 2
2487680.46472387511293.8843865692486506.35022082511397.068883508
#Sta/Elev= 30
       0   11.09    17.3   11.32   113.1    5.83   142.7    2.36   284.3    2.25
   300.8    -.22   307.4    -.53   310.7    -6.3   343.6    -6.3   346.9    -.25
   353.5       2   356.8    2.22   373.2    1.84   534.6    2.01   577.4    4.22
   607.1     4.9   630.1     6.8     647    7.07   686.1    9.75   755.3   10.82
   801.4   12.81   847.5   12.72   880.4   14.03   893.6   12.98   923.2   13.16
   972.6   14.62   992.1   14.41    1022   15.61  1087.9   16.51 1178.64   15.93
#Mann= 3 ,0,0
       0     .15       0   307.4     .05       0   346.9     .15       0
Bank Sta=307.4,346.9
XS Rating Curve= 0 ,0
Exp/Cntr(USF)=0,0
Exp/Cntr=0.3,0.1

Type RM Length L Ch R = 1 ,292     ,,,
XS GIS Cut Line= 2
2488481.52424986510731.7818341692486579.64780858511101.604967219
#Sta/Elev= 30
       0   11.81   118.6   12.19   152.1   11.33   182.1    8.55   202.2    2.52
   215.6    2.15   407.6    2.45   429.5    1.47   459.5    2.74   743.6    2.12
     757    3.21   803.8    2.22   890.7    3.65   940.8    1.41  1087.9    2.05
  1101.2      .9    1118    2.32  1134.7    -.51    1138    -6.4  1171.4    -6.4
  1174.8    -.42  1184.8    1.93  1204.9     .55  1395.4    2.76  1435.5     6.3
  1490.5    7.63  1559.1   11.16  1732.9   10.65  1868.6   13.071937.499   13.29
#Mann= 3 ,0,0
       0     .15       0    1118     .05       0  1184.8     .15       0
Bank Sta=1118,1184.8
XS Rating Curve= 0 ,0
Exp/Cntr(USF)=0,0
Exp/Cntr=0.3,0.1
LCMann Table=0

Chan Stop Cuts=-1
Use User Specified Reach Order=0
Composite Channel Slope=5

--- PoleSwamp.g01 (geometry) ---

Geom Title=Existing Conditions
Program Version=6.60

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
River Reach=Pole Branch     ,Reach 1

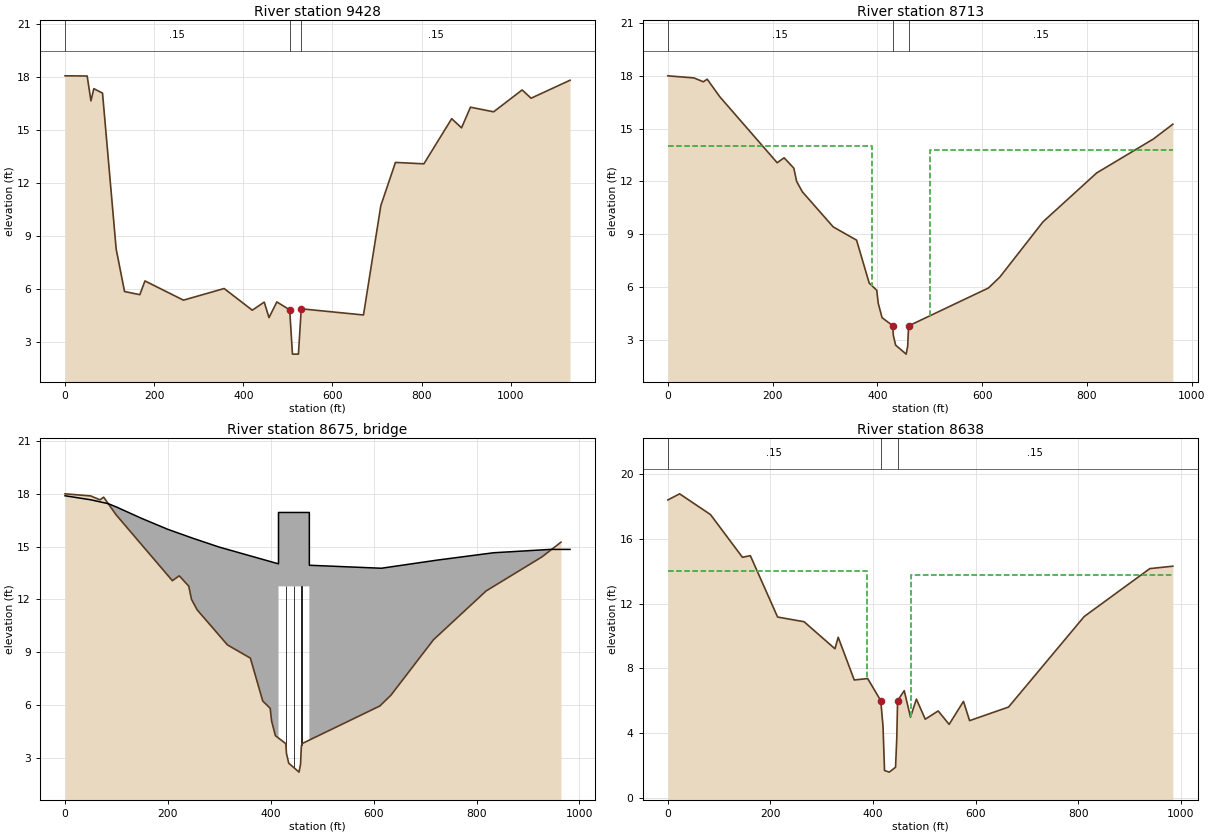
Type RM Length L Ch R = 1 ,9428    ,534.8,534.8,534.8
XS GIS Cut Line= 2
2486840.35942608517445.1468862852486192.21859464518374.466460771
#Sta/Elev= 30
       0   18.08    49.7   18.07    58.1   16.66    64.6   17.35    84.1    17.1
   114.7    8.26   133.5    5.85   167.8    5.67   179.3    6.45   265.7    5.36
     357    6.02   420.1    4.79   446.9    5.25   457.6    4.37   475.2    5.26
  504.04    4.81  510.23     2.3  523.62     2.3  529.98    4.87   669.6    4.52
   708.5   10.72   741.3   13.17   805.1   13.09   867.5   15.65   889.6   15.13
   909.6    16.3   961.6   16.04  1025.6   17.28  1045.6   16.811133.014   17.83
#Mann= 3 ,0,0
       0     .15       0  504.04     .05       0  529.98     .15       0
Bank Sta=504.04,529.98
XS Rating Curve= 0 ,0
Exp/Cntr(USF)=0,0
Exp/Cntr=0.5,0.3

Type RM Length L Ch R = 1 ,8713    ,75.4,75.4,75.4
XS GIS Cut Line= 5
2486475.67499602517312.0289722652486025.16383505517613.371183726
2485921.82201055517683.4372398442485816.46120685517767.337042368
2485699.87730714517880.622782793
#Sta/Elev= 30
       0      18    49.9   17.88    67.8   17.66    75.1   17.81    99.2   16.81
   208.7   13.06     222   13.34   238.7   12.81   240.5   12.75   245.9      12
   256.7   11.41   315.8    9.41   360.3    8.66   384.4    6.22   398.8    5.81
  401.69    5.07  409.01    4.25  429.25     3.8  430.52    3.24   434.9    2.69
  454.95    2.18  457.87    2.63  459.46    3.66  460.75     3.8   612.1    5.94
   633.8    6.56   716.2     9.7   818.7   12.48     927   14.41   964.1   15.25
#Mann= 3 ,0,0
       0     .15       0  429.25     .05       0  460.75     .15       0
#XS Ineff= 2 , 0
       0     390   14.02     500       0   13.77
Permanent Ineff=
       F       F
Bank Sta=429.25,460.75
XS Rating Curve= 0 ,0
Exp/Cntr(USF)=0,0
Exp/Cntr=0.5,0.3

Type RM Length L Ch R = 3 ,8675    ,,,
Node Name=S-22-24 over Pol
Bridge Culvert-0,0,0,0, 0
Deck Dist Width WeirC Skew NumUp NumDn MinLoCord MaxHiCord MaxSubmerge Is_Ogee
23.63031,28,3,0, 17, 17, , , 0.98, 0, 2,2,,
       0      50      84     100     150     200     250     300     415     415
     475     475     615     723     833     943   981.8
   17.89   17.66   17.44   17.25   16.59   15.98   15.46   14.97   14.02   16.94
   16.94   13.94   13.77   14.23   14.65   14.84   14.84
                                                                           12.74
   12.74
       0      50      84     100     150     200     250     300     401     401
     461     461     615     723     833     943   984.2
   17.89   17.66   17.44   17.25   16.59   15.98   15.46   14.97   14.02   16.94
   16.94   13.94   13.77   14.23   14.65   14.84   14.84
                                                                           12.74
   12.74
Pier Skew, UpSta & Num, DnSta & Num=  ,430, 2 ,416, 2 , 0 , 0 , 0 ,,
       1       1
       0   12.91
       1       1
       0   12.91
Pier Skew, UpSta & Num, DnSta & Num=  ,445, 2 ,431, 2 , 0 , 0 , 0 ,,
       1       1
       0   12.91
       1       1
       0   12.91
Pier Skew, UpSta & Num, DnSta & Num=  ,460, 2 ,446, 2 , 0 , 0 , 0 ,,
       1       1
       0   12.91
       1       1
       0   12.91
Abutment Skew #Up #Dn= , 2 , 2
     415  429.25
      12     4.5
     401   412.4
      12       6
Abutment Skew #Up #Dn= , 2 , 2
  460.75     475
     4.5      12
   449.6     461
       6      12
BR Coef=-1 , 0 , 0 ,, 0 ,,,0.8,0,,0,
WSPro=,,,, 1 ,,,, 0 ,,,, 0 ,,,,-1 ,-1 ,-1 , 0 , 0 , 0 , 0 , 0
BC Design=,, 0 ,, 0 ,,,,,,
BC HTab HWMax=22.11
BC Use User HTab Curves=0
BC User HTab FreeFlow(D)= 0

Type RM Length L Ch R = 1 ,8638    ,606,606,606
XS GIS Cut Line= 6
2486434.42239804517261.5771611622486214.94788033517399.359387984
2486018.43390436517527.228070975 2485873.0674016517627.504038162
 2485755.9666077517732.4909568282485646.86592787517845.022660153
#Sta/Elev= 30
       0    18.4    22.9   18.78    83.1    17.5   145.4   14.86   160.8   14.96
   213.9   11.17   265.5   10.88   325.7    9.21     332    9.92   363.3    7.28
   389.5    7.37     415       6   419.4    4.39   422.3    1.69  431.47    1.59
   443.8    1.89   446.2    3.73  447.74       6   460.7    6.62   472.9    4.99
   484.4     6.1   501.7    4.86   526.9    5.37   548.2    4.54   576.2    5.96
   588.1    4.77     664    5.61   811.4    11.2   939.3   14.16   984.2   14.31
#Mann= 3 ,0,0
       0     .15       0     415     .05       0  447.74     .15       0
#XS Ineff= 2 , 0
       0     389   14.02     473       0   13.77
Permanent Ineff=
       F       F
Bank Sta=415,447.74
XS Rating Curve= 0 ,0
Exp/Cntr(USF)=0,0
Exp/Cntr=0.5,0.3

--- PoleSwamp.g02 (geometry) ---

Geom Title=Proposed Conditions
Program Version=6.60

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
River Reach=Pole Branch     ,Reach 1

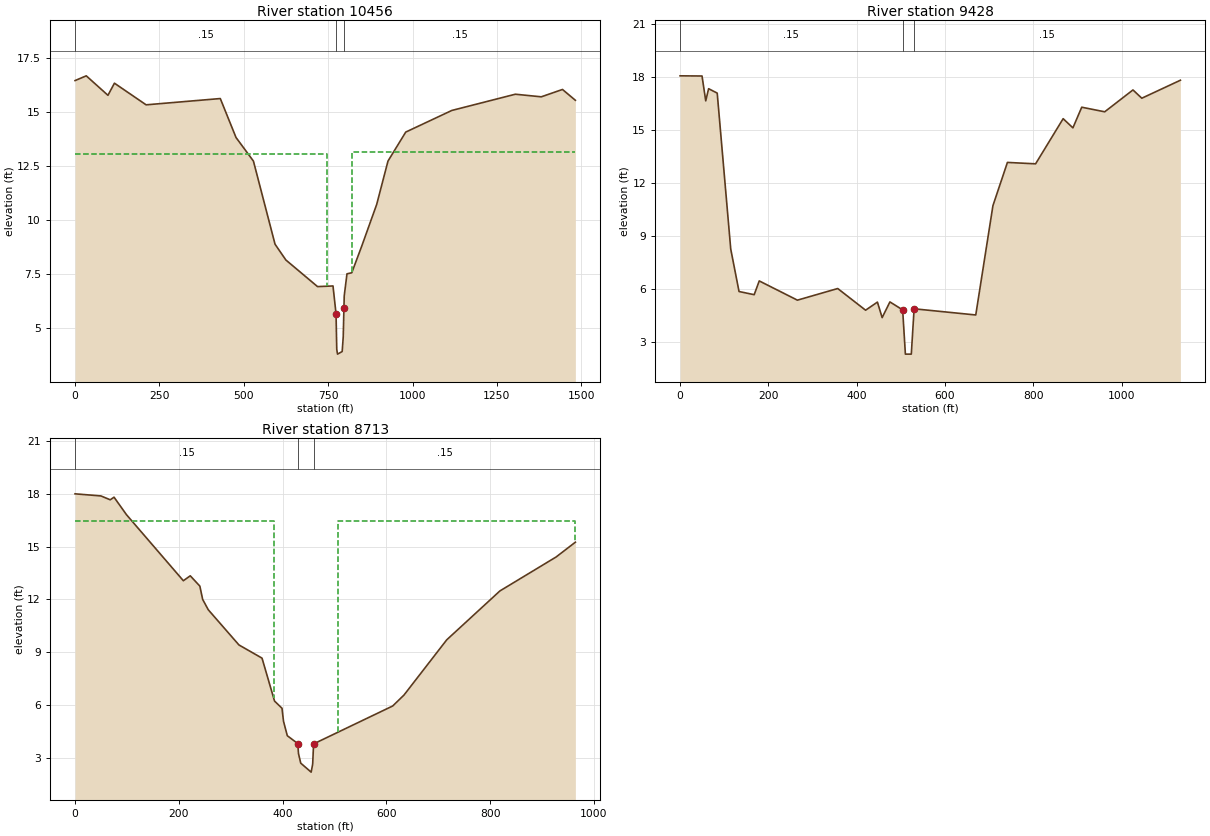
Type RM Length L Ch R = 1 ,10456   ,527.2,527.2,527.2
XS GIS Cut Line= 2
2488026.09080109518360.1633519022486561.01535596518587.263893491
#Sta/Elev= 30
       0   16.44    33.2   16.66    97.5   15.76   116.7   16.32   210.6   15.32
   430.4   15.61     477   13.81   528.6   12.72   592.6    8.88   624.7    8.15
   718.6    6.92  764.39    6.95   773.4    5.66   775.5    4.02  777.76     3.8
  791.55    3.92   794.7    4.59   796.8    5.95   797.7     6.5   805.8    7.51
     820    7.56   849.3    8.78   893.9   10.72   927.3   12.72   979.9   14.06
  1116.5   15.06  1304.7   15.81  1381.6   15.69  1444.4   16.03  1482.6   15.53
#Mann= 3 ,0,0
       0     .15       0   773.4     .05       0   796.8     .15       0
#XS Ineff= 2 , 0
             748   13.05     821           13.12
Permanent Ineff=
       F       F
Bank Sta=773.4,796.8
XS Rating Curve= 0 ,0
Exp/Cntr(USF)=0,0
Exp/Cntr=0.5,0.3

Type RM Length L Ch R = 1 ,9428    ,534.8,534.8,534.8
XS GIS Cut Line= 2
2486840.35942608517445.1468862852486192.21859464518374.466460771
#Sta/Elev= 30
       0   18.08    49.7   18.07    58.1   16.66    64.6   17.35    84.1    17.1
   114.7    8.26   133.5    5.85   167.8    5.67   179.3    6.45   265.7    5.36
     357    6.02   420.1    4.79   446.9    5.25   457.6    4.37   475.2    5.26
  504.04    4.81  510.23     2.3  523.62     2.3  529.98    4.87   669.6    4.52
   708.5   10.72   741.3   13.17   805.1   13.09   867.5   15.65   889.6   15.13
   909.6    16.3   961.6   16.04  1025.6   17.28  1045.6   16.811133.014   17.83
#Mann= 3 ,0,0
       0     .15       0  504.04     .05       0  529.98     .15       0
Bank Sta=504.04,529.98
XS Rating Curve= 0 ,0
Exp/Cntr(USF)=0,0
Exp/Cntr=0.5,0.3

Type RM Length L Ch R = 1 ,8713    ,75.4,75.4,75.4
XS GIS Cut Line= 5
2486475.67499602517312.0289722652486025.16383505517613.371183726
2485921.82201055517683.4372398442485816.46120685517767.337042368
2485699.87730714517880.622782793
#Sta/Elev= 30
       0      18    49.9   17.88    67.8   17.66    75.1   17.81    99.2   16.81
   208.7   13.06     222   13.34   238.7   12.81   240.5   12.75   245.9      12
   256.7   11.41   315.8    9.41   360.3    8.66   384.4    6.22   398.8    5.81
  401.69    5.07  409.01    4.25  429.25     3.8  430.52    3.24   434.9    2.69
  454.95    2.18  457.87    2.63  459.46    3.66  460.75     3.8   612.1    5.94
   633.8    6.56   716.2     9.7   818.7   12.48     927   14.41   964.1   15.25
#Mann= 3 ,0,0
       0     .15       0  429.25     .05       0  460.75     .15       0
#XS Ineff= 2 , 0
           382.5   16.46   507.5           16.46
Permanent Ineff=
       F       F
Bank Sta=429.25,460.75
XS Rating Curve= 0 ,0
Exp/Cntr(USF)=0,0
Exp/Cntr=0.5,0.3