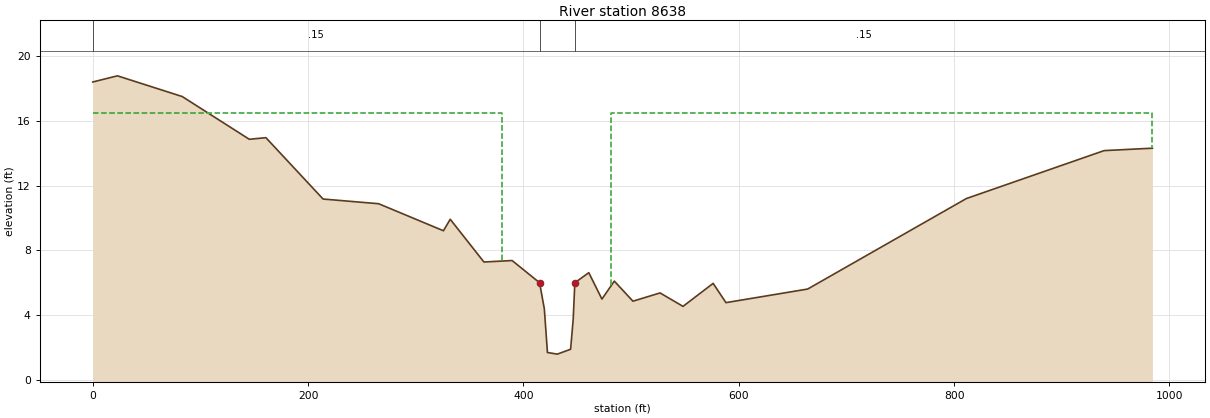
HEC-RAS study PoleSwamp.prj: S-22-24 Pole Swamp

--- PoleSwamp.g02 (geometry) --- (continued)

Type RM Length L Ch R = 3 ,8675    ,,,
Node Name=S-22-24 over Pol
Bridge Culvert-0,0,0,0, 0
Deck Dist Width WeirC Skew NumUp NumDn MinLoCord MaxHiCord MaxSubmerge Is_Ogee
21.13031,33,3,0, 6, 6, , , 0.98, 0, 2,2,,
       0  404.99     405     485  485.01   981.8
   16.46   16.46   16.46   16.46   16.46   16.46
                   13.13   13.13
       0  390.99     391     471  471.01   984.2
   16.46   16.46   16.46   16.46   16.46   16.46
                   13.13   13.13
Abutment Skew #Up #Dn= , 3 , 3
     405     407     427
   11.13   11.13    1.13
     391     393     413
   11.13   11.13    1.13
Abutment Skew #Up #Dn= , 3 , 3
     463     483     485
    1.13   11.13   11.13
     449     469     471
    1.13   11.13   11.13
BR Coef=-1 , 0 , 0 ,, 0 ,,,0.8,0,,0,
WSPro=,,,, 1 ,,,, 0 ,,,, 0 ,,,,-1 ,-1 ,-1 , 0 , 0 , 0 , 0 , 0
BC Design=,, 0 ,, 0 ,,,,,,
BC HTab HWMax=22.11
BC Use User HTab Curves=0
BC User HTab FreeFlow(D)= 0

Type RM Length L Ch R = 1 ,8638    ,606,606,606
XS GIS Cut Line= 6
2486434.42239804517261.5771611622486214.94788033517399.359387984
2486018.43390436517527.228070975 2485873.0674016517627.504038162
 2485755.9666077517732.4909568282485646.86592787517845.022660153
#Sta/Elev= 30
       0    18.4    22.9   18.78    83.1    17.5   145.4   14.86   160.8   14.96
   213.9   11.17   265.5   10.88   325.7    9.21     332    9.92   363.3    7.28
   389.5    7.37     415       6   419.4    4.39   422.3    1.69  431.47    1.59
   443.8    1.89   446.2    3.73  447.74       6   460.7    6.62   472.9    4.99
   484.4     6.1   501.7    4.86   526.9    5.37   548.2    4.54   576.2    5.96
   588.1    4.77     664    5.61   811.4    11.2   939.3   14.16   984.2   14.31
#Mann= 3 ,0,0
       0     .15       0     415     .05       0  447.74     .15       0
#XS Ineff= 2 , 0
          380.25   16.46  481.75           16.46
Permanent Ineff=
       F       F
Bank Sta=415,447.74
XS Rating Curve= 0 ,0
Exp/Cntr(USF)=0,0
Exp/Cntr=0.5,0.3