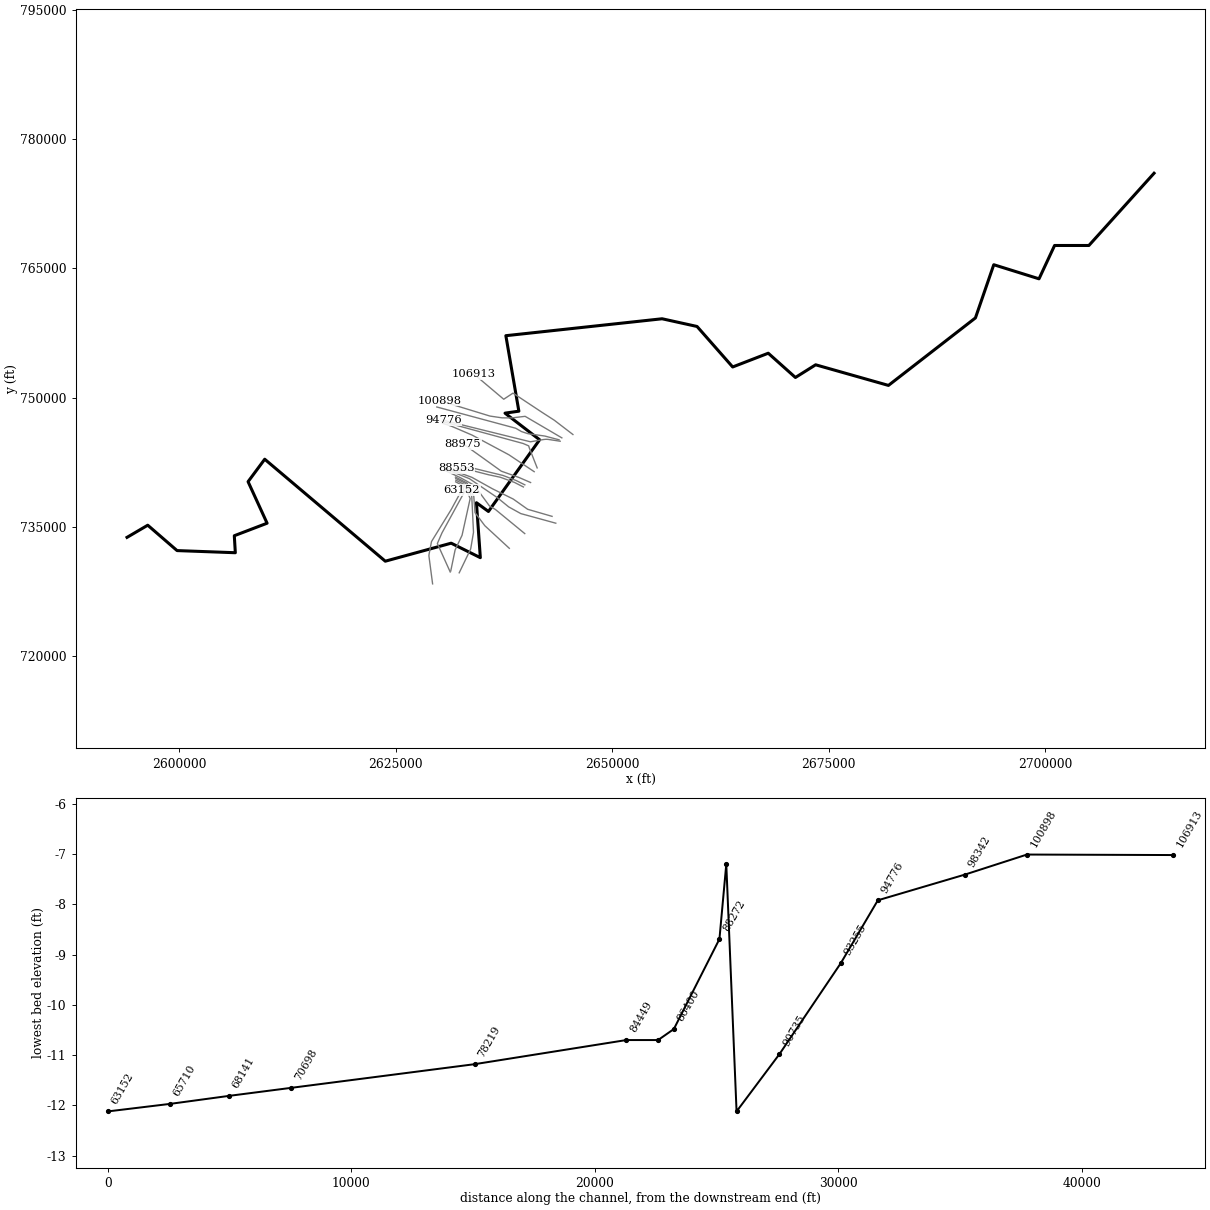
--- StanleyCreek.prj (project) ---

Proj Title=S-26-105 over Stanley Creek
Current Plan=p04
Default Exp/Contr=0.3,0.1
English Units
Geom File=g09
Geom File=g15
Geom File=g08
Flow File=f03
Flow File=f04
Plan File=p01
Plan File=p02
Plan File=p04
Plan File=p05
Plan File=p09
Y Axis Title=Elevation
X Axis Title(PF)=Main Channel Distance
X Axis Title(XS)=Station
BEGIN DESCRIPTION:
END DESCRIPTION:
DSS File=dss
DSS Export Rating Curves= 0
DSS Export Rating Curve Sorted= 0
DSS Export Volume Flow Curves= 0
DXF OffsetX= 0
DXF OffsetY= 0
DXF ScaleX= 1
DXF ScaleY= 10
Specific Locations Profile Table=HWM Comparison                       , 3
River 1         ,Reach 1         ,88553
River 1         ,Reach 1         ,50483
River 1         ,Reach 1         ,43579

--- StanleyCreek.p04 (plan) ---

Plan Title=Corrected Effective-Floodway
Program Version=6.60
Short Identifier=CE-FW
Geom File=g09
Flow File=f04
Subcritical Flow
K Sum by GR= 0
Std Step Tol= 0.01
Critical Tol= 0.01
Num of Std Step Trials= 20
Max Error Tol= 0.3
Flow Tol Ratio= 0.001
Split Flow NTrial= 30
Split Flow Tol= 0.02
Split Flow Ratio= 0.02
Log Output Level= 0
Friction Slope Method= 1
Unsteady Friction Slope Method= 2
Unsteady Bridges Friction Slope Method= 1
Calc Critical at every XS
Parabolic Critical Depth
Global Vel Dist= 0 , 0 , 0
Global Log Level= 0
CheckData=True
Encroach Param=-1 ,0,0, 2
Encroach River=River 1
Encroach Reach=Reach 1
Encroach Node=106913
       1    3096    9350
Encroach Node=100898
       1 3333.1511819.55
Encroach Node=98342
       1 2671.0410813.64
Encroach Node=94776
       1 2254.43 7766.43
Encroach Node=93255
       1 2354.98 7080.07
Encroach Node=90735
       1 1801.13 6507.15
Encroach Node=88975
       1 2170.23 5656.23
Encroach Node=88553
       1 1495.23  5943.7
Encroach Node=88272
       1 1325.11 6020.23
Encroach Node=86400
       1    5365   10685
Encroach Node=85753
       1 3713.8111471.91
Encroach Node=84449
       1 2104.08 9023.69
Encroach Node=78219
       1 1909.27 9110.37
Encroach Node=70698
       1 2585.9810318.88
Encroach Node=68141
       1 2648.93 9821.13
Encroach Node=65710
       1 2546.83 9232.65
Encroach Node=63152
       1 3411.5910954.77
Encroach Node=60474
       1  3534.512322.63
Encroach Node=58035
       1 3753.69 13750.1
Encroach Node=55486
       1 2893.64 13519.9
Encroach Node=53628
       1 4463.57 8588.57
Encroach Node=50483
       1 5492.07 9268.57
Encroach Node=47978
       1 4821.0810117.61
Encroach Node=45478
       1 4861.5810980.13
Encroach Node=43579
       1 5638.4413138.44
Flow Ratio Tolerance=0.1
Flow Ratio Min Ratio=0.5
Flow Ratio Max Ratio=4
Flow Ratio Max Iterations= 10
Computation Interval=1MIN
Output Interval=1HOUR
Instantaneous Interval=1HOUR
Mapping Interval=1HOUR
Computation Time Step Use Courant=        0
Computation Time Step Use Time Series=    0
Computation Time Step Count To Double=0
Computation Time Step Max Doubling=0
Computation Time Step Max Halving=0
Computation Time Step Residence Courant=0
Run HTab= 0
Run UNet= 0
Run Sediment= 0
Run PostProcess= 0
Run WQNet= 0
Run RASMapper= 0
UNET Theta= 1
UNET Theta Warmup= 1
UNET ZTol= 0.02
UNET ZSATol= 0.02
UNET MxIter= 20
UNET Max Iter WO Improvement= 0
UNET MaxInSteps= 0
UNET DtIC= 0
UNET DtMin= 0
UNET MaxCRTS= 20
UNET WFStab= 2
UNET SFStab= 1
UNET WFX= 1
UNET SFX= 1
UNET Gravity=32.17405
UNET 1D Methodology=Finite Difference
UNET DSS MLevel= 4
UNET Pardiso=0
UNET DZMax Abort= 100
UNET Use Existing IB Tables=-1
UNET Froude Reduction=False
UNET Froude Limit= 0.8
UNET Froude Power= 4
UNET D1 Cores= 0
UNET WindReference=Eulerian
UNET WindDragFormulation=Hsu (1988)
UNET D2 Coriolis=0
UNET D2 Cores= 0
UNET D2 Theta= 1
UNET D2 Theta Warmup= 1
UNET D2 Z Tol= 0.01
UNET D2 Volume Tol= 0.01
UNET D2 Max Iterations= 20
UNET D2 Advanced Convergence=0
UNET D2 WS Max Tol=0.15
UNET D2 WS RMS Tol=0.002
UNET D2 WS Stall Tol=1
UNET D2 Equation= 0
UNET D2 RampUpFraction=0.1
UNET D2 TimeSlices= 1
UNET D2 Turbulence Formulation=None
UNET D2 Eddy Viscosity=0.3
UNET D2 Transverse Eddy Viscosity=0.1
UNET D2 Smagorinsky Mixing=0.05
UNET D2 BCVolumeCheck=0
UNET D2 Cores=0
UNET D2 SolverType=PARDISO (Direct)
UNET D2 Minimum Iterations= 3
UNET D2 Maximum Iterations= 30
UNET D2 Restart Number= 10
UNET D2 Relaxation Coeff=1.3
UNET D2 SOR Precondition Iterations= 10
UNET D2 ILUT Maximum Fill= 8
UNET D2 ILUT Tolerance=1E-08
UNET D2 Convergence Tolerance=0.00001
PS Theta= 1
PS WS Tol= 0.01
PS Volume Tol= 0.01
PS Max Iterations= 20
PS Equation= 0
PS Advance Time Step=-1
PS Target Courant=0.9
PS Time Slices= 1
PS Iterate With 2D=0
PS Project Initial WSE from DS=-1
PS Ramp Up Initial WSE from US=-1
PS Cores=0
UNET D1D2 MaxIter= 0
UNET D1D2 ZTol=0.01
UNET D1D2 QTol=0.1
UNET D1D2 MinQTol=1
Write IC File= 0
Write IC File at Fixed DateTime=0
Write IC File at Sim End=0
Echo Input=False
Echo Parameters=False
Echo Output=False
Write Detailed= 0
HDF Write Warmup=0
HDF Write Time Slices=0
HDF Flush=0
HDF Compression= 1
HDF Chunk Size= 1
HDF Spatial Parts= 1
HDF Use Max Rows=0
HDF Fixed Rows= 1
Calibration Method= 0
Calibration Iterations= 20
Calibration Max Change=0.05
Calibration Tolerance=0.2
Calibration Maximum=1.5
Calibration Minimum=0.5
Calibration Optimization Method= 1
WQ AD Non Conservative
WQ ULTIMATE=-1
WQ Max Comp Step=1HOUR
WQ Output Interval=15MIN
WQ Output Selected Increments= 0
WQ Create Restart=0
WQ Fixed Restart=0
WQ System Summary=0
WQ Write To DSS=0
Sorting and Armoring Iterations= 10
XS Update Threshold= 0.02
Bed Roughness Predictor= 0
Processes Affected by Predictor=Sediment Only
Hydraulics Update Threshold= 0.02
Energy Slope Method= 1
Volume Change Method= 1
Sediment Retention Method= 0
Sediment TS Multiplier= 1
Warm Up Method= 0
XS Weighting Method= 0
Number of US Weighted Cross Sections= 1
Number of DS Weighted Cross Sections= 1
Upstream XS Weight=0
Main XS Weight=1
Downstream XS Weight=0
Number of DS XS's Weighted with US Boundary= 1
Upstream Boundary Weight= 1
Weight of XSs Associated with US Boundary= 0
Number of US XS's Weighted with DS Boundary= 1
Downstream Boundary Weight= 0.5
Weight of XSs Associated with DS Boundary= 0.5
Percentile Method= 0
Sediment Output Level= 3
Mass or Volume Output= 0
Output Increment Type= 1
Profile and TS Output Increment= 1
Transport Output Increment 1
XS Output Flag= 0
XS Output Increment= 10
Read HDF5 Sediment Hotstart= 0
Sediment Hotstart Type= 0
Write Gradation File= 0
Read Gradation Hotstart= 0
Write HDF5 File= 1
Write Binary Output= 1
Write DSS Sediment File= 0
DSS Sediment Output Type= 1
SV Curve= 0
Specific Gage Flag= 0
Subcell Erosion Methods= 0
Subcell Deposition Methods= 0
Advection Scheme= 1
Matrix Solver= 0
Implicit Weighting Factor= 1
Maximum Outer Loop Convergence Iterations= 5
Convergence Maximum Absolute= 0.001
Convergence RMSE= 0.0001
Grain Fractions Max Abs Error= 0.001
Max Subgrid Regions= 1
Max Subgrid Length Scale= 3.402823E+38
Initial Layer Thickness= 3
Min Layer Thickness= 0.1
Max Layer Thickness= 6
Number of Layers= 5

--- StanleyCreek.p01 (plan) ---

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Plan Title=Existing Conditions
Short Identifier=EXIST
Geom File=g09
Flow File=f03
Encroach Param=-1 ,0,0, 0

--- StanleyCreek.p02 (plan) ---

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Plan Title=Proposed Conditions
Short Identifier=PROP
Geom File=g08
Flow File=f03
Encroach Param=-1 ,0,0, 0

--- StanleyCreek.p05 (plan) ---

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Plan Title=Proposed Conditions-Floodway
Short Identifier=PROP-FW
Geom File=g08
Flow File=f04

--- StanleyCreek.p09 (plan) ---

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Plan Title=Natural Conditions
Short Identifier=Natural
Geom File=g15
Flow File=f03
Encroach Param=-1 ,0,0, 0

--- StanleyCreek.f04 (steady flow) ---

Flow Title=FIS
Program Version=6.60
Number of Profiles= 2
Profile Names=100Y,100Y-FW
River Rch & RM=River 1,Reach 1         ,106913
   18790   18790
River Rch & RM=River 1,Reach 1         ,94776
   19150   19150
River Rch & RM=River 1,Reach 1         ,70698
   19340   19340
Boundary for River Rch & Prof#=River 1,Reach 1         , 1
Up Type= 0
Dn Type= 1
Dn Known WS=14.2
Boundary for River Rch & Prof#=River 1,Reach 1         , 2
Up Type= 0
Dn Type= 1
Dn Known WS=15.2
DSS Import GetInterval= 0
DSS Import GetPeak= 0
DSS Import FillOption= 0

--- StanleyCreek.f03 (steady flow) ---

Flow Title=Weighted-Q_02110500-Translated
Program Version=6.60
Number of Profiles= 6
Profile Names=2Y,10Y,25Y,50Y,100Y,500Y
River Rch & RM=River 1,Reach 1         ,106913
    6339   15953   22477   28192   34266   50470
Boundary for River Rch & Prof#=River 1,Reach 1         , 1
Up Type= 0
Dn Type= 3
Dn Slope=0.000056
Boundary for River Rch & Prof#=River 1,Reach 1         , 2
Up Type= 0
Dn Type= 3
Dn Slope=0.000056
Boundary for River Rch & Prof#=River 1,Reach 1         , 3
Up Type= 0
Dn Type= 3
Dn Slope=0.000056
Boundary for River Rch & Prof#=River 1,Reach 1         , 4
Up Type= 0
Dn Type= 3
Dn Slope=0.000056
Boundary for River Rch & Prof#=River 1,Reach 1         , 5
Up Type= 0
Dn Type= 3
Dn Slope=0.000056
Boundary for River Rch & Prof#=River 1,Reach 1         , 6
Up Type= 0
Dn Type= 3
Dn Slope=0.000056
DSS Import GetInterval= 0
DSS Import GetPeak= 0
DSS Import FillOption= 0

--- StanleyCreek.g09 (geometry) ---

Geom Title=Existing Conditions
Program Version=6.60

River Reach=River 1         ,Reach 1
Reach XY= 30
2712560.73381626776022.9516027772705036.80696812767644.777889112
2701076.93527287767644.7831699762699280.36501104763779.548766559
2694056.20473085765414.4925418512691940.24509326759245.388181026
2681899.33942428751418.9924574672673494.67853485753809.622891038
2671159.24158516752338.9769037162668024.72890816755152.787332204
2663916.38480086753557.2924591182659804.08240615758253.128776612
 2655771.9471298759146.8087742192637733.38182145757185.116120058
2639234.57839131748431.5373598922637633.99670396748202.882833127
2641631.51009913745117.1493304062635724.43536497736800.530917115
2634337.58496276737816.8447878952634787.77080191731443.637099085
2631421.32853997733124.7610024572623815.11453592731035.467897699
2609897.85345288742859.7391357752607975.74927214740257.914495283
2610170.97284656735440.3423450122606386.33189943733988.516199378
2606503.38383539 732017.141954022599778.08657482 732265.59310347
2596393.88652638735208.3189271822594001.52730554733798.112382494

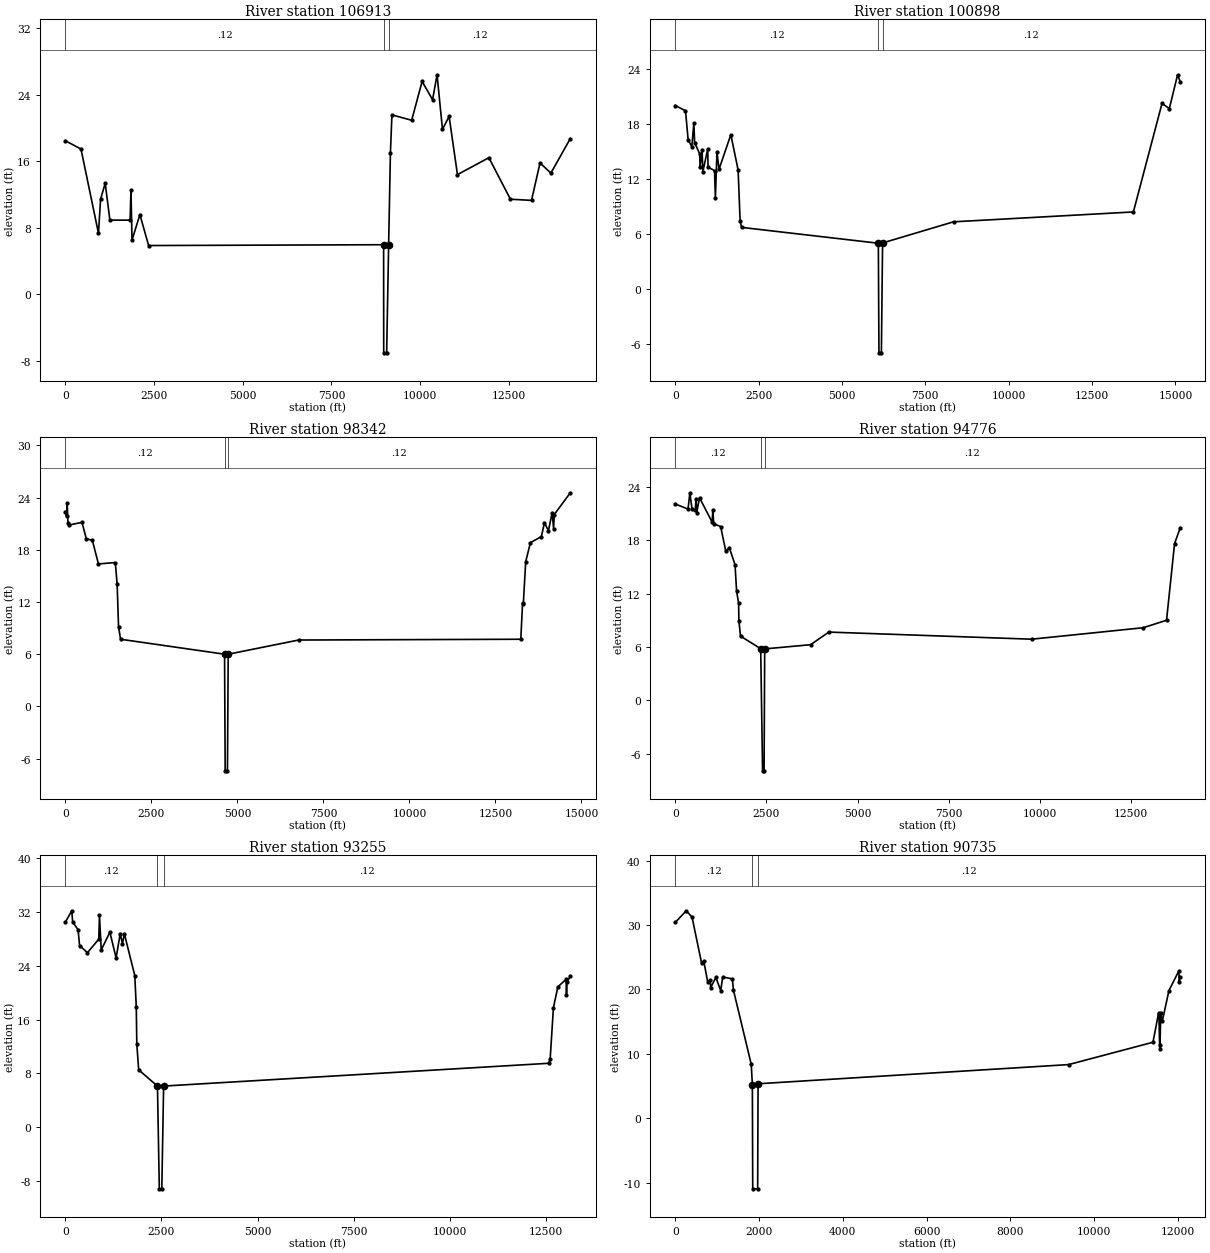
Type RM Length L Ch R = 1 ,106913  ,6014.7,6014.7,6014.7
BEGIN DESCRIPTION:
HEC-2 RS: 193847; LETTERED XS Q
END DESCRIPTION:
Node Name=Q
XS GIS Cut Line= 6
2645475.08900152745725.7020444292643330.02279168747377.874723611
 2641849.2459726748336.9332460442638559.47457019750525.614446444
2637487.77385908749815.0231131492634038.19890862752739.519819677
#Sta/Elev= 30
       0   18.48   440.8   17.48   933.6    7.35   991.9   11.44  1122.7   13.36
  1255.3    8.94  1825.2    8.93  1848.8   12.56    1879    6.54  2100.6     9.6
  2346.8    5.88 8969.37    5.98  8972.5  -7.019  9055.1  -7.019 9110.98    5.97
  9161.4   17.04  9203.9   21.59  9760.2   20.94 10054.4   25.61 10349.4   23.41
 10475.5   26.41 10628.4   19.86 10815.4    21.4 11050.5   14.41 11936.6   16.44
 12543.1   11.45 13137.7   11.31 13377.5   15.81 13682.9   14.59 14231.4   18.74
#Mann= 3 ,0,0
       0     .12       0 8969.37    .045       0 9110.98     .12       0
Bank Sta=8969.37,9110.98
XS Rating Curve= 0 ,0
Exp/Cntr(USF)=0,0
Exp/Cntr=0.3,0.1

Type RM Length L Ch R = 1 ,100898  ,2555.9,2555.9,2555.9
BEGIN DESCRIPTION:
HEC-2 RS: 187500
END DESCRIPTION:
XS GIS Cut Line= 6
2644195.07338281745337.3498578862639958.77418791747833.962940845
2638412.62981181747649.1882507342637290.75879478747658.270003195
2635903.20779355 747863.682550422630038.78397215749668.160115446
#Sta/Elev= 30
       0   20.02   308.6   19.45   389.1   16.25   498.4   15.53   559.9   18.12
   581.9   15.97     736   14.72   744.2   13.27   805.9   15.19   828.7   12.78
   976.7    15.3   984.3   13.28  1179.4   12.91  1204.5    9.91  1252.9   14.91
  1314.6   13.06  1667.9   16.83  1886.3   12.98 1947.04    7.37 1992.11     6.7
  6090.5    4.97    6109  -7.009    6182  -7.009 6217.69       5  8344.2    7.31
13737.46    8.39   14596   20.25 14815.7   19.69 15062.9   23.38 15140.3   22.62
#Mann= 3 ,0,0
       0     .12       0  6090.5    .045       0 6217.69     .12       0
Bank Sta=6090.5,6217.69
XS Rating Curve= 0 ,0
Exp/Cntr(USF)=0,0
Exp/Cntr=0.3,0.1

Type RM Length L Ch R = 1 ,98342   ,3566.4,3566.4,3566.4
BEGIN DESCRIPTION:
HEC-2 RS: 185000
END DESCRIPTION:
XS GIS Cut Line= 6
2643877.05160074745110.4083202322642228.66339347745548.152074705
2640283.05958245745821.0576389242639545.57765066746063.422313174
2638867.96507703746453.4349716562629765.04574944  748916.8735553
#Sta/Elev= 30
       0    22.4    35.1   21.84    52.1   23.39    75.9   21.12   116.6   20.86
   483.2   21.16   608.8   19.28   784.3   19.09   961.8   16.38  1452.1   16.54
    1505   14.06  1545.7    9.18 1604.51    7.72    4627       6 4644.77   -7.39
    4711  -7.409    4733       6 6779.02    7.63 13236.3    7.72 13287.3   11.81
 13311.1   11.91 13379.2   16.64 13515.3   18.82 13835.2   19.53 13923.6   21.12
 14039.3    20.2 14148.2   22.27 14189.4   20.44 14209.4   22.06 14675.6   24.56
#Mann= 3 ,0,0
       0     .12       0    4627    .045       0    4733     .12       0
Bank Sta=4627,4733
XS Rating Curve= 0 ,0
Exp/Cntr(USF)=0,0
Exp/Cntr=0.3,0.1

Type RM Length L Ch R = 1 ,94776   ,1520.6,1520.6,1520.6
BEGIN DESCRIPTION:
HEC-2 RS: 181722; LETTERED XS P
END DESCRIPTION:
Node Name=P
XS GIS Cut Line= 6
2644004.02404964744946.8952626132642607.96200529745159.502524023
2642354.78060459745170.4927714532642122.59952773745149.291758087
2640572.57839073 744881.376751042630504.80463159747382.038834102
#Sta/Elev= 30
       0   22.08   351.9   21.51   401.7   23.34   461.5    21.5   551.1   21.41
     571   22.65   590.9   21.12   667.2   22.78  1012.4   20.04  1032.3   21.38
  1055.5   19.86  1246.9   19.54  1387.4   16.76  1482.9   17.18  1640.5   15.25
  1683.2   12.28  1739.2    10.9  1745.8    8.97 1790.42    7.23 2344.13    5.81
  2395.6  -7.919  2437.1  -7.919  2453.7    5.79 3712.43    6.26 4211.83    7.68
 9772.39    6.8812832.68    8.1713472.01    9.01 13691.7   17.62 13845.5   19.39
#Mann= 3 ,0,0
       0     .12       0 2344.13    .045       0  2453.7     .12       0
Bank Sta=2344.13,2453.7
XS Rating Curve= 0 ,0
Exp/Cntr(USF)=0,0
Exp/Cntr=0.3,0.1

Type RM Length L Ch R = 1 ,93255   ,2520,2520,2520
BEGIN DESCRIPTION:
HEC-2 RS: 180000
END DESCRIPTION:
XS GIS Cut Line= 6
2641348.54787328741852.0659421232640419.17878782744225.218353953
2640395.86971783744331.4577071992640367.01266065744409.334096919
2639725.34545291744684.5390683512630367.63918595747240.593194604
#Sta/Elev= 30
       0   30.49   166.1    32.2   190.7   30.53   331.5   29.38   369.6   27.03
   574.4   25.96   870.1   27.98   887.7   31.57   933.5   26.37  1158.8   29.02
  1320.7   25.18  1427.3    28.8  1484.9    27.3  1535.4   28.78  1806.5   22.56
  1845.2   17.94  1859.3   12.36 1908.73    8.53 2396.52    6.12    2445  -9.169
    2510  -9.169 2556.72    6.12   12577    9.51 12614.4   10.09 12699.4   17.77
   12815   20.89 13029.3   21.99 13039.5   19.61 13053.1   21.66 13139.2   22.43
#Mann= 3 ,0,0
       0     .12       0 2396.52    .045       0 2556.72     .12       0
Bank Sta=2396.52,2556.72
XS Rating Curve= 0 ,0
Exp/Cntr(USF)=0,0
Exp/Cntr=0.3,0.1

Type RM Length L Ch R = 1 ,90735   ,1760.5,1760.5,1760.5
BEGIN DESCRIPTION:
HEC-2 RS: 177500
END DESCRIPTION:
XS GIS Cut Line= 6
2641004.73305628 741414.91629492 2638080.5689262743377.090479364
2633848.74864333745651.4117456662631514.16699338746660.901066132
2631083.74027524746818.5850923752630388.96432854747037.110463386
#Sta/Elev= 30
       0   30.39   264.1   32.21   402.3   31.22   631.4   24.03   680.3   24.45
   777.5   21.11   837.8    21.5   845.3   20.26   970.2   21.86    1087   19.82
  1134.1   21.93  1365.2   21.63  1388.8   19.94  1816.2    8.35 1842.33    5.14
    1851 -10.979    1969 -10.979 1978.05    5.34  9393.8    8.32   11407   11.79
 11540.1   16.28 11551.1   15.82 11565.3   11.34 11572.9   10.69 11592.8   16.27
 11630.6   15.09 11788.8   19.82 12026.1   22.89   12033   21.09 12056.5   21.97
#Mann= 3 ,0,0
       0     .12       0 1842.33    .045       0 1978.05     .12       0
Bank Sta=1842.33,1978.05
XS Rating Curve= 0 ,0
Exp/Cntr(USF)=0,0
Exp/Cntr=0.5,0.3

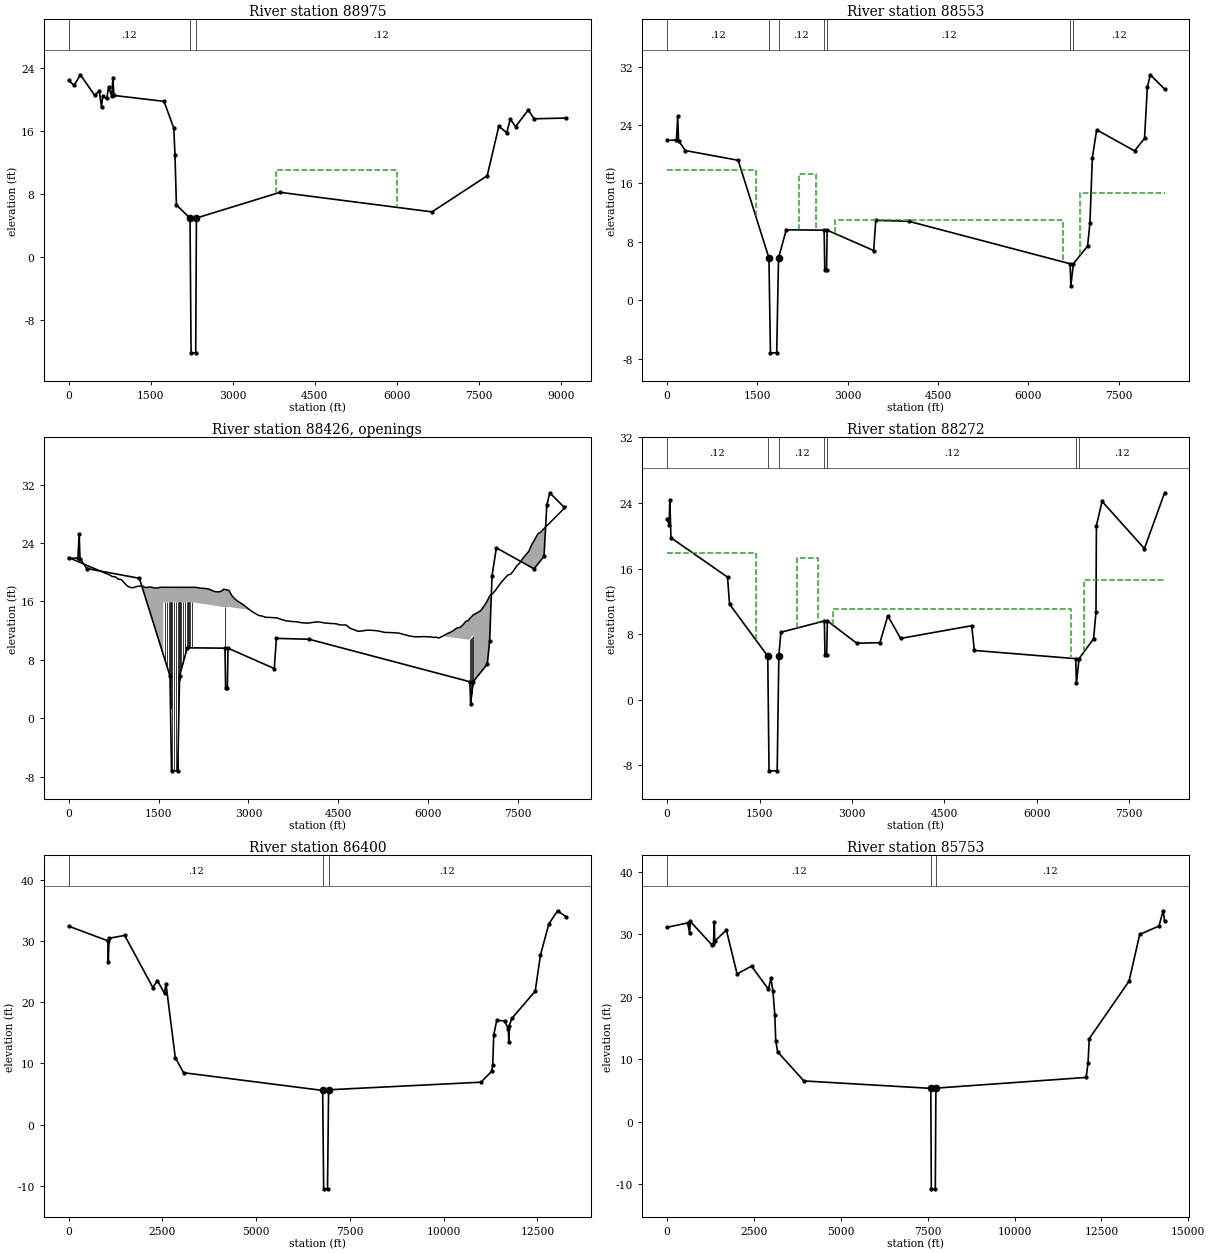
Type RM Length L Ch R = 1 ,88975   ,422.1,422.1,422.1
BEGIN DESCRIPTION:
HEC-2 RS: 175925; LETTERED XS O
END DESCRIPTION:
Node Name=O
XS GIS Cut Line= 6
2640588.85736791740158.6974255812639256.61391338 740740.78241696
2637208.91381491741473.6215394142634953.36176664743102.688214742
2633117.50385446744416.7883676932632743.28891142744631.481986932
#Sta/Elev= 30
       0   22.44     101   21.81   215.2   23.15   476.6   20.55   559.9   21.12
   601.9   19.04   623.4    20.4   699.2   20.15   730.8    21.6     788   20.47
   810.9    22.8   827.4   20.53    1745   19.78  1924.4   16.38  1945.3   13.03
  1972.1    6.65 2220.74    4.96    2240 -12.119    2325 -12.119    2338   4.981
 3866.39    8.24  6647.2    5.76  7656.7   10.34  7869.2   16.62  8014.5    15.8
  8079.1   17.53  8175.9   16.57  8406.1   18.67  8516.6   17.57  9100.2   17.66
#Mann= 3 ,0,0
       0     .12       0 2220.74    .045       0    2338     .12       0
#XS Ineff= 3 ,-1
       0    1350   17.85    3800    6000   11.01    8400    9101   14.65
Permanent Ineff=
       F       F       F
Bank Sta=2220.74,2338
XS Rating Curve= 0 ,0
Exp/Cntr(USF)=0,0
Exp/Cntr=0.5,0.3

Type RM Length L Ch R = 1 ,88553   ,281.1,281.1,281.1
BEGIN DESCRIPTION:
HEC-2 RS: 175431
END DESCRIPTION:
XS GIS Cut Line= 6
2639923.99594256739889.041723748 2638899.3778991740400.570090771
2637408.58032692740974.8775054672633845.05375212741849.243319125
2633485.11936892741882.4818361852632001.39702076741799.782192469
#Sta/Elev= 30
       0    21.9   155.3   21.94   176.3    25.2   190.2   21.85   304.3    20.5
  1180.4   19.17 1691.37     5.8 1716.69    -7.2 1820.37    -7.2 1851.37     5.8
 1979.19    9.65 2608.86     9.6 2619.18     4.2 2648.78     4.2 2658.86     9.6
  3431.5    6.81  3466.2   10.94  4012.7   10.82 6694.81       5 6707.29       2
 6749.81       5 6985.19    7.42  7024.7   10.64  7064.2   19.52  7136.5   23.34
  7765.5   20.46  7931.4   22.18  7978.1   29.18  8027.3   30.88  8264.8   28.92
#Mann= 7 ,-1,0
       0     .12       0 1691.37    .045       0 1851.37     .12       0
 2608.86    .045       0 2658.86     .12       0 6694.81    .045       0
 6749.81     .12       0
#XS Ineff= 4 ,-1
       0    1471   17.85    2199 2476.45   17.32 2784.45 6572.45   11.01
 6865.45    8300   14.65
Permanent Ineff=
       F       F       F       F
Bank Sta=1691.37,1851.37
XS Rating Curve= 0 ,0
Exp/Cntr(USF)=0,0
Exp/Cntr=0.5,0.3

Type RM Length L Ch R = 4 ,88426   ,,,
BEGIN DESCRIPTION:
S-105 Multi Opening
END DESCRIPTION:
Bridge Culvert--1,0,-1,-1, 0
Deck Dist Width WeirC Skew NumUp NumDn MinLoCord MaxHiCord MaxSubmerge Is_Ogee
110,35,2.6,0, 151, 151, , , 0.98, 0, 2,2,,
       0  527.45  577.45  627.45  677.45  727.45  777.45  827.45  877.45  927.45
  977.45 1027.45 1077.45 1127.45 1177.45 1227.45 1277.45 1327.45 1377.45 1427.45
 1477.45 1527.45 1577.45 1579.99    1580    2090 2090.01 2127.45 2177.45 2227.45
 2277.45 2327.45 2377.45 2427.45 2477.45 2527.45 2577.45 2585.44 2585.45 2675.45
 2675.46 2677.45 2727.45 2777.45 2827.45 2877.45 2927.45 2977.45 3027.45 3077.45
 3127.45 3177.45 3227.45 3277.45 3327.45 3377.45 3427.45 3477.45 3527.45 3577.45
 3627.45 3677.45 3727.45 3777.45 3827.45 3877.45 3927.45 3977.45 4027.45 4077.45
 4127.45 4177.45 4227.45 4277.45 4327.45 4377.45 4427.45 4477.45 4527.45 4577.45
 4627.45 4677.45 4727.45 4777.45 4827.45 4877.45 4927.45 4977.45 5027.45 5077.45
 5127.45 5177.45 5227.45 5277.45 5327.45 5377.45 5427.45 5477.45 5527.45 5577.45
 5627.45 5677.45 5727.45 5777.45 5827.45 5877.45 5927.45 5977.45 6027.45 6077.45
 6127.45 6177.45 6227.45 6277.45 6327.45 6377.45 6427.45 6477.45 6527.45 6577.45
 6627.45 6677.45 6681.44 6681.45 6756.45 6756.46 6777.45 6827.45 6877.45 6927.45
 6977.45 7027.45 7077.45 7127.45 7177.45 7227.45 7277.45 7327.45 7377.45 7427.45
 7477.45 7527.45 7577.45 7627.45 7677.45 7727.45 7777.45 7827.45 7877.45 7927.45
    8300
      22   20.18      20   19.81   19.66   19.41   19.38   19.06      19   18.56
   18.13   17.91   17.88   18.02   18.09   18.13   17.91   17.94   17.97   17.84
   17.84   17.94   17.94  17.947  17.947  17.931  17.931   17.93   17.84    17.8
   17.78   17.72   17.56   17.38   17.31   17.34   17.56  17.679  17.679  17.508
  17.508   17.47   16.75   16.31      16   15.75   15.47   15.13   14.81   14.53
   14.28   14.06      14   13.84   13.82    13.8   13.79   13.75   13.59   13.47
   13.34   13.31   13.25   13.22   13.19   13.09   13.06   13.03   13.06   13.13
   13.19   13.19   13.13   13.03   13.03   12.97   12.97   12.91   12.78   12.78
   12.78   12.44   12.22   12.09   11.91   11.94      12   12.06   12.06   12.03
      12   11.94   11.84   11.75   11.75   11.73   11.72   11.69   11.63    11.5
   11.41   11.28   11.22   11.16   11.16   11.16   11.19   11.16   11.16   11.09
   11.09      11   11.19   11.41   11.63   11.81   12.06   12.37   12.43   12.78
   13.28   13.41  13.559  13.559  14.208  14.208   14.25    14.5   14.75   15.33
   15.97   16.79   17.09   17.59   18.17   18.71   19.17   19.61   19.74   20.25
   20.88   21.28   21.89   22.39   22.87    23.8   24.47   25.25    25.5   25.94
      29
                                                                                
                                                                                
                                 15.8845 15.8685
                                                                  15.227  15.227
                                                                                
                                                                                
                                                                                
                                                                                
                                                                                
                                                                                
                                                                                
                                                                                
                          10.748  11.478
                                                                                
                                                                                
        
       0  467.45  517.45  567.45  617.45  667.45  717.45  767.45  817.45  867.45
  917.45  967.45 1017.45 1067.45 1117.45 1167.45 1217.45 1267.45 1317.45 1367.45
 1417.45 1467.45 1517.45 1519.99    1520    2030 2030.01 2067.45 2117.45 2167.45
 2217.45 2267.45 2317.45 2367.45 2417.45 2467.45 2517.45 2525.44 2525.45 2615.45
 2615.46 2617.45 2667.45 2717.45 2767.45 2817.45 2867.45 2917.45 2967.45 3017.45
 3067.45 3117.45 3167.45 3217.45 3267.45 3317.45 3367.45 3417.45 3467.45 3517.45
 3567.45 3617.45 3667.45 3717.45 3767.45 3817.45 3867.45 3917.45 3967.45 4017.45
 4067.45 4117.45 4167.45 4217.45 4267.45 4317.45 4367.45 4417.45 4467.45 4517.45
 4567.45 4617.45 4667.45 4717.45 4767.45 4817.45 4867.45 4917.45 4967.45 5017.45
 5067.45 5117.45 5167.45 5217.45 5267.45 5317.45 5367.45 5417.45 5467.45 5517.45
 5567.45 5617.45 5667.45 5717.45 5767.45 5817.45 5867.45 5917.45 5967.45 6017.45
 6067.45 6117.45 6167.45 6217.45 6267.45 6317.45 6367.45 6417.45 6467.45 6517.45
 6567.45 6617.45 6621.44 6621.45 6696.45 6696.46 6717.45 6767.45 6817.45 6867.45
 6917.45 6967.45 7017.45 7067.45 7117.45 7167.45 7217.45 7267.45 7317.45 7367.45
 7417.45 7467.45 7517.45 7567.45 7617.45 7667.45 7717.45 7767.45 7817.45 7867.45
    8100
      22   20.18      20   19.81   19.66   19.41   19.38   19.06      19   18.56
   18.13   17.91   17.88   18.02   18.09   18.13   17.91   17.94   17.97   17.84
   17.84   17.94   17.94  17.947  17.947  17.931  17.931   17.93   17.84    17.8
   17.78   17.72   17.56   17.38   17.31   17.34   17.56  17.679  17.679  17.508
  17.508   17.47   16.75   16.31      16   15.75   15.47   15.13   14.81   14.53
   14.28   14.06      14   13.84   13.82    13.8   13.79   13.75   13.59   13.47
   13.34   13.31   13.25   13.22   13.19   13.09   13.06   13.03   13.06   13.13
   13.19   13.19   13.13   13.03   13.03   12.97   12.97   12.91   12.78   12.78
   12.78   12.44   12.22   12.09   11.91   11.94      12   12.06   12.06   12.03
      12   11.94   11.84   11.75   11.75   11.73   11.72   11.69   11.63    11.5
   11.41   11.28   11.22   11.16   11.16   11.16   11.19   11.16   11.16   11.09
   11.09      11   11.19   11.41   11.63   11.81   12.06   12.37   12.43   12.78
   13.28   13.41  13.559  13.559  14.208  14.208   14.25    14.5   14.75   15.33
   15.97   16.79   17.09   17.59   18.17   18.71   19.17   19.61   19.74   20.25
   20.88   21.28   21.89   22.39   22.87    23.8   24.47   25.25    25.5   25.94
      29
                                                                                
                                                                                
                                 15.8845 15.8685
                                                                  15.227  15.227
                                                                                
                                                                                
                                                                                
                                                                                
                                                                                
                                                                                
                                                                                
                                                                                
                          10.748  11.478
                                                                                
                                                                                
        
Pier Skew, UpSta & Num, DnSta & Num=  ,1610, 2 ,1550, 2 , 0 , 0 , 0 ,,
     1.5     1.5
  -10.56 15.8845
     1.5     1.5
  -10.56 15.8845
Pier Skew, UpSta & Num, DnSta & Num=  ,1640, 2 ,1580, 2 , 0 , 0 , 0 ,,
     1.5     1.5
  -10.56 15.8845
     1.5     1.5
  -10.56 15.8845
Pier Skew, UpSta & Num, DnSta & Num=  ,1670, 2 ,1610, 2 , 0 , 0 , 0 ,,
     1.5     1.5
  -10.56 15.8845
     1.5     1.5
  -10.56 15.8845
Pier Skew, UpSta & Num, DnSta & Num=  ,1700, 2 ,1640, 2 , 0 , 0 , 0 ,,
     1.5     1.5
  -10.56 15.8845
     1.5     1.5
  -10.56 15.8845
Pier Skew, UpSta & Num, DnSta & Num=  ,1730, 2 ,1670, 2 , 0 , 0 , 0 ,,
     1.5     1.5
  -10.56 15.8845
     1.5     1.5
  -10.56 15.8845
Pier Skew, UpSta & Num, DnSta & Num=  ,1760, 2 ,1700, 2 , 0 , 0 , 0 ,,
     1.5     1.5
  -10.56 15.8845
     1.5     1.5
  -10.56 15.8845
Pier Skew, UpSta & Num, DnSta & Num=  ,1790, 2 ,1730, 2 , 0 , 0 , 0 ,,
     1.5     1.5
  -10.56 15.8845
     1.5     1.5
  -10.56 15.8845
Pier Skew, UpSta & Num, DnSta & Num=  ,1820, 2 ,1760, 2 , 0 , 0 , 0 ,,
     1.5     1.5
  -10.56 15.8845
     1.5     1.5
  -10.56 15.8845
Pier Skew, UpSta & Num, DnSta & Num=  ,1850, 2 ,1790, 2 , 0 , 0 , 0 ,,
     1.5     1.5
  -10.56 15.8845
     1.5     1.5
  -10.56 15.8845
Pier Skew, UpSta & Num, DnSta & Num=  ,1880, 2 ,1820, 2 , 0 , 0 , 0 ,,
     1.5     1.5
  -10.56 15.8845
     1.5     1.5
  -10.56 15.8845
Pier Skew, UpSta & Num, DnSta & Num=  ,1910, 2 ,1850, 2 , 0 , 0 , 0 ,,
     1.5     1.5
  -10.56 15.8845
     1.5     1.5
  -10.56 15.8845
Pier Skew, UpSta & Num, DnSta & Num=  ,1940, 2 ,1880, 2 , 0 , 0 , 0 ,,
     1.5     1.5
  -10.56 15.8845
     1.5     1.5
  -10.56 15.8845
Pier Skew, UpSta & Num, DnSta & Num=  ,1970, 2 ,1910, 2 , 0 , 0 , 0 ,,
     1.5     1.5
  -10.56 15.8845
     1.5     1.5
  -10.56 15.8845
Pier Skew, UpSta & Num, DnSta & Num=  ,2000, 2 ,1940, 2 , 0 , 0 , 0 ,,
     1.5     1.5
  -10.56 15.8845
     1.5     1.5
  -10.56 15.8845
Pier Skew, UpSta & Num, DnSta & Num=  ,2030, 2 ,1970, 2 , 0 , 0 , 0 ,,
     1.5     1.5
  -10.56 15.8845
     1.5     1.5
  -10.56 15.8845
Pier Skew, UpSta & Num, DnSta & Num=  ,2060, 2 ,2000, 2 , 0 , 0 , 0 ,,
     1.5     1.5
  -10.56 15.8845
     1.5     1.5
  -10.56 15.8845
Pier Skew, UpSta & Num, DnSta & Num=  ,2615.45, 2 ,2555.45, 2 , 0 , 0 , 0 ,,
     1.5     1.5
  -10.54  15.885
     1.5     1.5
  -10.54  15.885
Pier Skew, UpSta & Num, DnSta & Num=  ,6696.45, 2 ,6636.45, 2 , 0 , 0 , 0 ,,
       1       1
       5      13
       1       1
       5      13
Pier Skew, UpSta & Num, DnSta & Num=  ,6711.45, 2 ,6651.45, 2 , 0 , 0 , 0 ,,
       1       1
       5      13
       1       1
       5      13
Pier Skew, UpSta & Num, DnSta & Num=  ,6726.45, 2 ,6666.45, 2 , 0 , 0 , 0 ,,
       1       1
       5      13
       1       1
       5      13
Pier Skew, UpSta & Num, DnSta & Num=  ,6741.45, 2 ,6681.45, 2 , 0 , 0 , 0 ,,
       1       1
       5      13
       1       1
       5      13
Abutment Skew #Up #Dn= , 3 , 3
2075.273 2088.01 2090.01
     7.5 13.8685 13.8685
2016.873 2028.01 2030.01
     8.3 13.8685 13.8685
Abutment Skew #Up #Dn= , 3 , 3
 2585.44 2587.442601.894
  13.227  13.227       6
 2525.44 2527.442540.894
  13.227  13.227     6.5
Abutment Skew #Up #Dn= , 3 , 3
2659.006 2673.46 2675.46
       6  13.227  13.227
2599.006 2613.46 2615.46
       6  13.227  13.227
Abutment Skew #Up #Dn= , 3 , 3
 6681.44 6683.44  6690.6
8.8298338.829833    5.25
 6621.44 6623.44  6630.6
8.8298338.829833    5.25
Abutment Skew #Up #Dn= , 3 , 3
 6681.44 6683.44 6690.44
    8.75    8.75    5.25
 6621.44 6623.44 6630.44
    8.75    8.75    5.25
Abutment Skew #Up #Dn= , 3 , 3
  6745.5 6754.46 6756.46
       5    9.48    9.48
  6685.5 6694.46 6696.46
       5    9.48    9.48
BR Coef=-1 , 0 , 0 ,, 0 ,,,0.8,0,,1,
WSPro=,,,, 1 ,,,, 0 ,,,, 0 ,,,,-1 ,-1 ,-1 , 0 , 0 , 0 , 0 , 0
BR Coef= 1 , 0 , 0 ,, 0 ,,,0.8,0,,1,
WSPro=,,,, 1 ,,,, 0 ,,,, 0 ,,,,-1 ,-1 ,-1 , 0 , 0 , 0 , 0 , 0
BR Coef=-1 , 0 , 0 ,, 0 ,,,0.8,0,,1,
WSPro=,,,, 1 ,,,, 0 ,,,, 0 ,,,,-1 ,-1 ,-1 , 0 , 0 , 0 , 0 , 0
BC Mult= 3 ,0,2400,0,2335
BC Mult= 3 ,2300,5000,2235,4935
BC Mult= 3 ,4900,8264.8,4835,8076.3
BC Design=,, 0 ,, 0 ,,,,,,
BC Use User HTab Curves=0
BC User HTab FreeFlow(D)= 0

Type RM Length L Ch R = 1 ,88272   ,1871.6,1871.6,1871.6
BEGIN DESCRIPTION:
HEC-2 RS: 175405
END DESCRIPTION:
XS GIS Cut Line= 6
2639759.10162326 739641.054175242638739.93718149740164.078255589
2637110.02084291740765.7370482342635698.68947809741068.115000988
2633648.35548859741599.1871794712632022.55717049 741532.54762993
#Sta/Elev= 30
       0   22.07    33.4   21.34    44.3   24.34    62.4   19.75   980.8   14.95
  1013.1   11.65 1633.84    5.31 1654.64   -8.69 1786.96   -8.69 1813.84    5.31
 1846.76    8.22 2553.02     9.6 2562.77     5.4 2589.75     5.4 2602.02     9.6
  3078.8    6.88  3454.9    6.95  3582.3   10.22  3790.6    7.47  4944.3    9.02
  4987.9       6 6632.35       5 6644.83       2 6687.35       5 6922.73    7.42
 6962.24   10.64  6969.1   21.24  7061.2   24.19  7748.2   18.43  8076.3   25.24
#Mann= 7 ,-1,0
       0     .12       0 1633.84    .045       0 1813.84     .12       0
 2553.02    .045       0 2602.02     .12       0 6632.35    .045       0
 6687.35     .12       0
#XS Ineff= 4 ,-1
       0    1448   17.85    2102 2453.45   17.32 2687.45 6549.45   11.01
 6768.45    8100   14.65
Permanent Ineff=
       F       F       F       F
Bank Sta=1633.84,1813.84
XS Rating Curve= 0 ,0
Exp/Cntr(USF)=0,0
Exp/Cntr=0.5,0.3

Type RM Length L Ch R = 1 ,86400   ,647.2,647.2,647.2
BEGIN DESCRIPTION:
HEC-2 RS: 173378; LETTERED XS N
END DESCRIPTION:
Node Name=N
XS GIS Cut Line= 6
2643067.77836505736235.5792383672640250.09170809737055.058598447
2638582.82833254738241.8137045732636199.92921926739424.593244212
2633808.65895275740761.1114126562631107.89266354741747.365582393
#Sta/Elev= 30
       0   32.43  1047.9   30.03  1058.1    26.5  1078.6   30.45  1495.5   30.91
  2246.6    22.4  2366.7   23.54  2558.1   21.47  2595.7   23.05  2844.9   10.95
  3065.2    8.49    67755.594706 6802.01  -10.48 6904.46  -10.48  6933.2     5.7
 10997.7    6.9411278.87    8.71 11309.8    9.73 11337.8   14.66 11418.5   17.06
 11628.9   16.94   11726   15.63 11739.8   13.53 11750.2   16.16   11823   17.38
 12443.4   21.81 12582.1   27.68 12807.4    32.8 13039.6   34.94 13267.3   33.96
#Mann= 3 ,0,0
       0     .12       0    6775    .045       0  6933.2     .12       0
Bank Sta=6775,6933.2
XS Rating Curve= 0 ,0
Exp/Cntr(USF)=0,0
Exp/Cntr=0.3,0.1

Type RM Length L Ch R = 1 ,85753   ,1303.9,1303.9,1303.9
BEGIN DESCRIPTION:
HEC-2 RS: 172500
END DESCRIPTION:
XS GIS Cut Line= 6
2643498.25279085735441.6171081092639454.40158606736555.895108586
2638063.89942882737330.3520062932636740.41698843738410.676530577
2633536.05631338740599.0380276742630814.18735025741703.608658451
#Sta/Elev= 30
       0   31.11   591.8   31.81   646.2   30.19     670   32.04  1282.6   28.34
  1333.9   28.46  1357.5   31.93  1371.1   28.88  1704.8   30.68  2014.3   23.65
  2429.4    24.9  2916.1   21.22  2987.6   22.95  3045.4   20.97  3099.9   17.15
  3127.1      13  3181.5    11.2    3937    6.55 7589.86    5.36    7605 -10.699
    7720 -10.699 7736.72     5.412060.84    7.11 12115.3    9.38 12151.4   13.31
 13296.3    22.5 13603.4   29.97 14157.7   31.31 14277.3   33.75 14320.2   32.14
#Mann= 3 ,0,0
       0     .12       0 7589.86    .045       0 7736.72     .12       0
Bank Sta=7589.86,7736.72
XS Rating Curve= 0 ,0
Exp/Cntr(USF)=0,0
Exp/Cntr=0.3,0.1

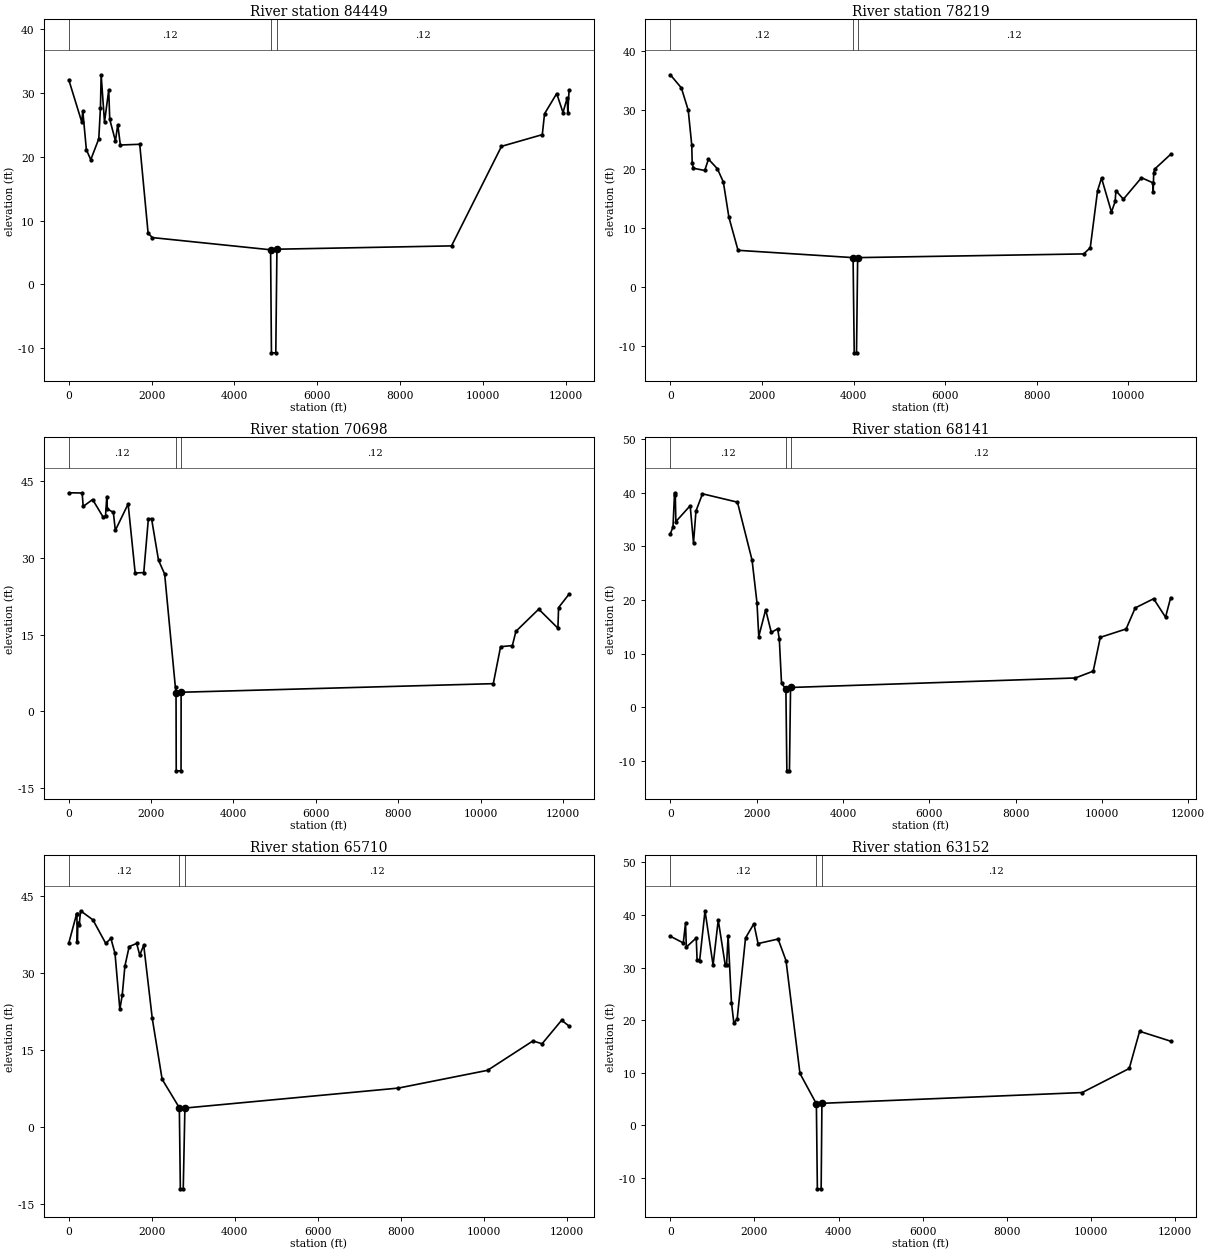
Type RM Length L Ch R = 1 ,84449   ,6230.6,6230.6,6230.6
BEGIN DESCRIPTION:
HEC-2 RS: 171200
END DESCRIPTION:
XS GIS Cut Line= 6
2639916.14138831734235.4944340412636520.15257366737037.341571777
2635842.18742927737439.6651947142634098.05706312739828.835775386
2632437.24568683740743.5441770742630594.12250267741607.712126059
#Sta/Elev= 30
       0   32.05     315   25.41   338.8   27.19   425.6   21.09   531.9   19.53
   725.4    22.8   765.9   27.69   782.5   32.82   863.7    25.4   965.8   30.44
     990   25.84  1127.5   22.47  1183.4   25.02  1246.5   21.83  1714.4   21.94
 1916.62    8.02 2019.15    7.34 4874.37    5.43    4895 -10.699    5000 -10.699
 5027.63    5.52 9243.94    6.04 10450.4   21.62   11436   23.45 11490.3   26.72
 11783.8   29.88   11936   26.91 12037.5   29.21   12052   26.88   12082   30.38
#Mann= 3 ,0,0
       0     .12       0 4874.37    .045       0 5027.63     .12       0
Bank Sta=4874.37,5027.63
XS Rating Curve= 0 ,0
Exp/Cntr(USF)=0,0
Exp/Cntr=0.3,0.1

Type RM Length L Ch R = 1 ,78219   ,7520.4,7520.4,7520.4
BEGIN DESCRIPTION:
HEC-2 RS: 165000
END DESCRIPTION:
XS GIS Cut Line= 6
2638133.47498179 732528.434096982635306.12358247735151.110545361
2634174.09222052 736663.220125972634030.16043813738558.369952187
2633251.39438061740108.3927138422631917.67839532740790.919817662
#Sta/Elev= 30
       0   36.01   241.3   33.78   390.9      30   468.1   24.06   477.7      21
   503.1   20.15   751.6   19.77   832.8   21.69  1027.8   20.06  1157.7   17.81
  1278.6   11.84  1478.2    6.22    3990   4.981    4015 -11.179    4065 -11.179
    4090   4.981  9025.2    5.61  9168.1    6.66  9327.9   16.34  9413.8   18.49
  9631.1   12.72  9711.8   14.51  9727.7   16.34    9892    14.9 10286.5   18.54
 10529.9    17.7   10542   16.09 10553.2   19.26 10571.2   19.98 10922.9   22.51
#Mann= 3 ,0,0
       0     .12       0    3990    .045       0    4090     .12       0
Bank Sta=3990,4090
XS Rating Curve= 0 ,0
Exp/Cntr(USF)=0,0
Exp/Cntr=0.3,0.1

Type RM Length L Ch R = 1 ,70698   ,2556.8,2556.8,2556.8
BEGIN DESCRIPTION:
HEC-2 RS: 157500
END DESCRIPTION:
XS GIS Cut Line= 6
2632348.19282865729687.8921651612633672.79885286732455.867471648
2633999.11022492734384.3758029712633799.08550119738520.775863484
2633094.00888505740055.1430204672631947.51463399740627.642558463
#Sta/Elev= 30
       0   42.73   325.6   42.69     351   40.06   579.4   41.41   840.4   37.91
   893.9   38.26   923.7      42   938.2   39.57  1083.2   38.89  1131.3   35.38
  1442.1   40.54  1613.3   27.03  1821.7   27.13  1933.7   37.65  2010.6   37.68
  2179.8   29.54  2328.9   26.84 2602.82    3.54    2605   4.691  2610.1 -11.649
  2727.1 -11.649 2729.01    3.72 10309.4     5.4 10486.9   12.63 10773.1   12.85
 10859.3   15.64   11413   19.97 11878.7   16.25   11895   20.28 12149.2   22.91
#Mann= 3 ,0,0
       0     .12       0 2602.82    .045       0 2729.01     .12       0
Bank Sta=2602.82,2729.01
XS Rating Curve= 0 ,0
Exp/Cntr(USF)=0,0
Exp/Cntr=0.3,0.1

Type RM Length L Ch R = 1 ,68141   ,2431.6,2431.6,2431.6
BEGIN DESCRIPTION:
HEC-2 RS: 155000
END DESCRIPTION:
XS GIS Cut Line= 6
  2631373.912898729906.1423250612631875.03871705732335.493873044
 2632676.7359611734037.8990850882633612.71130867738297.527555848
2632909.30395715739946.4930628752631959.79940364740430.889661226
#Sta/Elev= 30
       0   32.36    61.3    33.6    98.2   39.99   114.9   39.58   128.3   34.62
     460   37.58   537.1   30.66     594   36.59   744.8    39.8  1555.5   38.24
  1893.8   27.44  2007.3   19.53    2049   13.21  2208.6   18.21  2339.3   13.97
  2486.4   14.65  2524.8   12.76  2576.4    4.49 2677.18    3.45    2700 -11.809
    2760 -11.809 2785.35    3.72 9383.66    5.49  9797.5    6.76  9961.6   13.06
 10559.7   14.62 10770.6   18.54 11196.8   20.25 11473.1   16.81 11591.1   20.44
#Mann= 3 ,0,0
       0     .12       0 2677.18    .045       0 2785.35     .12       0
Bank Sta=2677.18,2785.35
XS Rating Curve= 0 ,0
Exp/Cntr(USF)=0,0
Exp/Cntr=0.3,0.1

Type RM Length L Ch R = 1 ,65710   ,2558.1,2558.1,2558.1
BEGIN DESCRIPTION:
HEC-2 RS: 152500
END DESCRIPTION:
XS GIS Cut Line= 6
2631309.92870102729784.734066432 2629826.0425096733085.209952217
2630353.28275791734303.3074276862632921.63158501739015.930867519
2632746.32902076739805.2481180062631940.66360788740237.477546556
#Sta/Elev= 30
       0   35.81   189.2   41.51   196.3   41.49   206.9    36.1   221.1   39.75
     253   39.44     285   42.13   583.1   40.36   891.8   35.78    1016   36.76
  1115.4   33.82  1231.7   22.96  1289.5   25.72  1353.2   31.34  1456.1   35.16
  1637.1   35.78  1711.6   33.49  1807.2   35.44  2013.2   21.19    2251    9.35
 2665.92    3.81    2690 -11.969    2760 -11.969 2799.77    3.75 7942.54    7.63
10095.77   11.09 11188.9   16.81 11408.8   16.25 11881.3   20.84 12059.6   19.69
#Mann= 3 ,0,0
       0     .12       0 2665.92    .045       0 2799.77     .12       0
Bank Sta=2665.92,2799.77
XS Rating Curve= 0 ,0
Exp/Cntr(USF)=0,0
Exp/Cntr=0.3,0.1

Type RM Length L Ch R = 1 ,63152   ,2677.2,2677.2,2677.2
BEGIN DESCRIPTION:
HEC-2 RS: 150000
END DESCRIPTION:
XS GIS Cut Line= 6
2629276.87160227728407.3215036292628850.99387506 731652.58257899
2628872.72645044731859.0352030172629149.67220284733310.170687622
2631417.89140519737013.5091879132632651.79240473 739291.63502489
#Sta/Elev= 30
       0   35.96   308.2   34.69   361.1   38.44     381    33.9   615.9   35.63
   635.8   31.53   695.3   31.21   824.4   40.81  1016.3   30.46  1138.8   39.06
  1304.2   30.53  1337.3   30.54  1373.7   36.01  1453.1   23.35  1509.4   19.48
  1588.8   20.19  1787.3   35.62  1985.8   38.34  2085.1   34.57  2561.6   35.43
  2750.2   31.32  3081.1    9.85 3471.47    4.07    3495 -12.119    3585 -12.119
 3603.38    4.16  9789.3    6.21 10908.1   10.79 11154.6   17.87 11891.8   15.99
#Mann= 3 ,0,0
       0     .12       0 3471.47    .045       0 3603.38     .12       0
Bank Sta=3471.47,3603.38
XS Rating Curve= 0 ,0
Exp/Cntr(USF)=0,0
Exp/Cntr=0.3,0.1