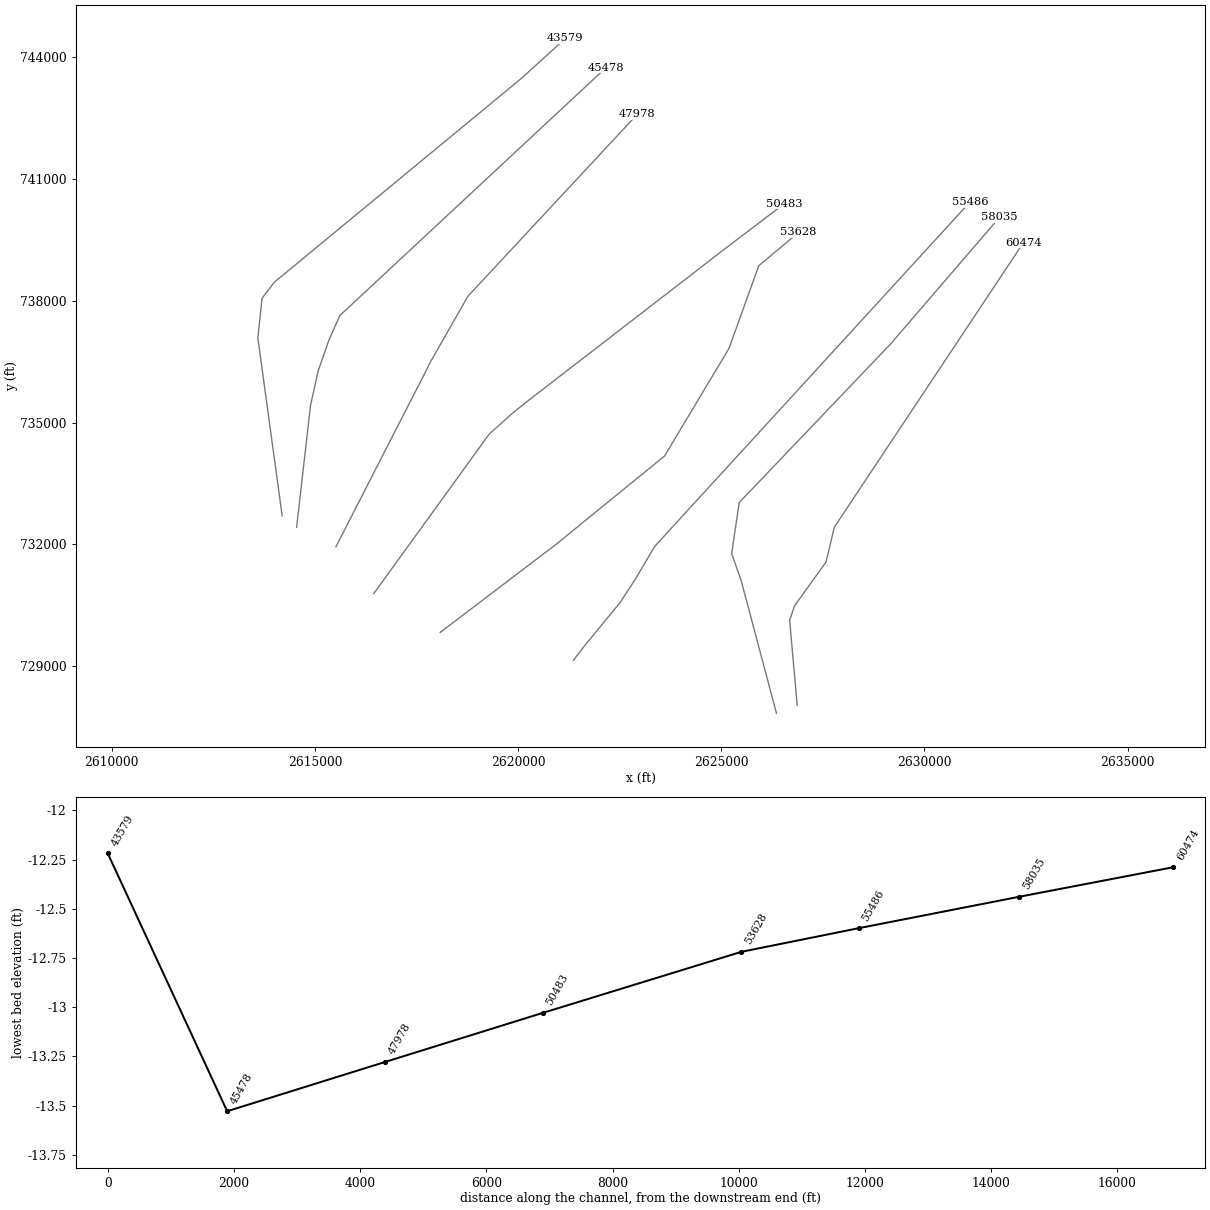
HEC-RAS study StanleyCreek.prj: S-26-105 over Stanley Creek

--- StanleyCreek.g09 (geometry) --- (continued)

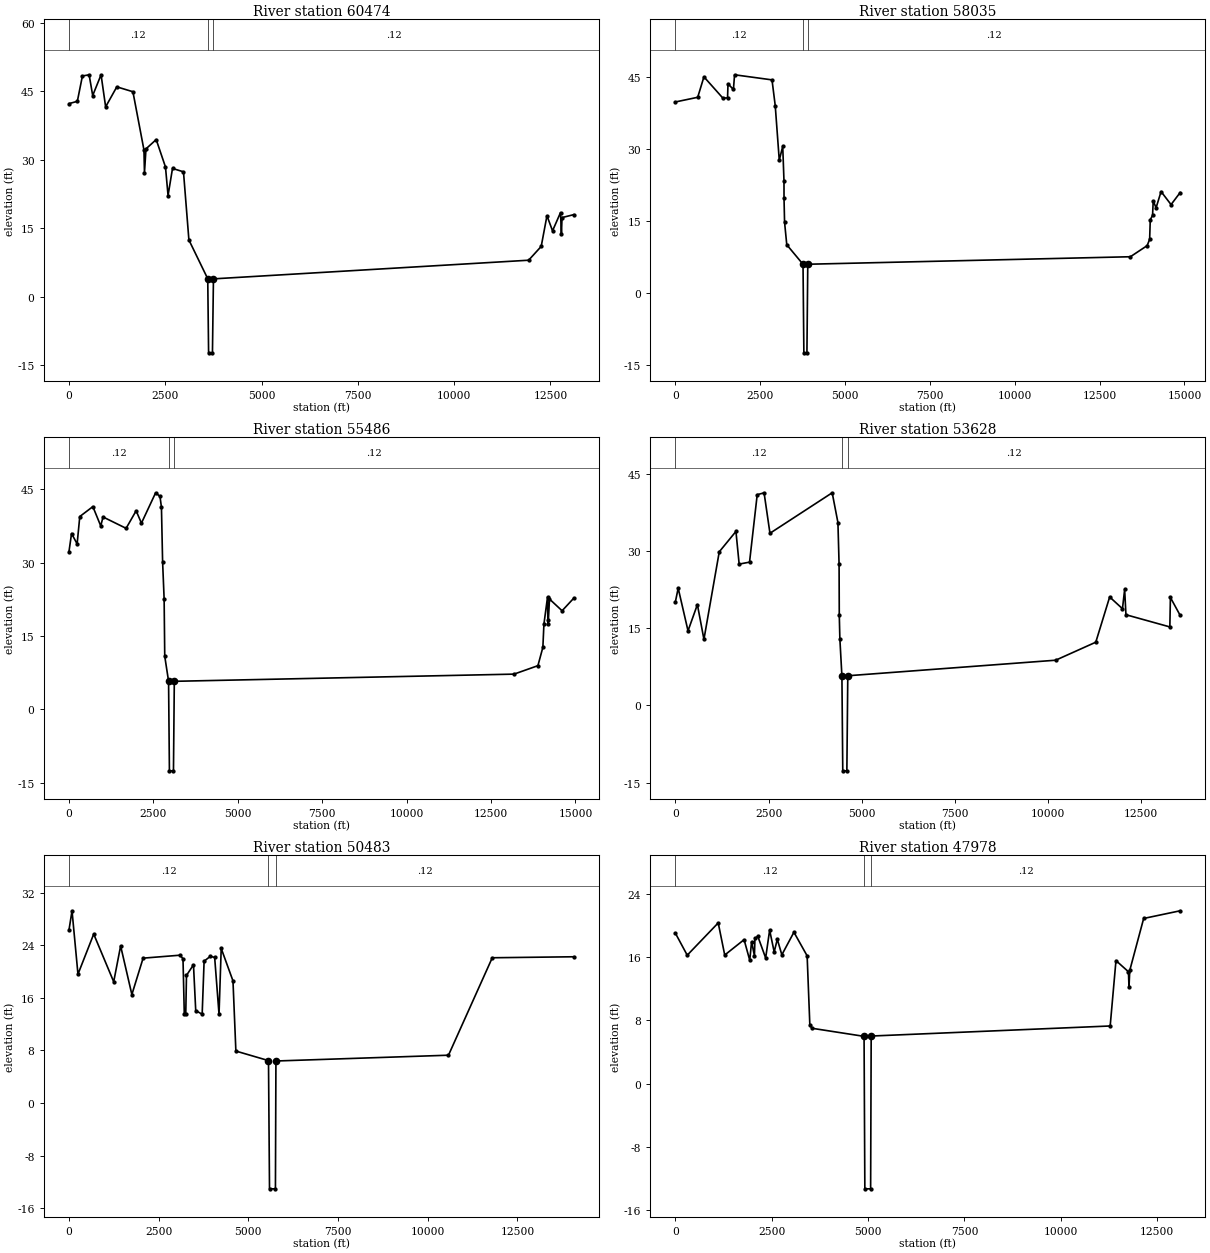
Type RM Length L Ch R = 1 ,60474   ,2439.7,2439.7,2439.7
BEGIN DESCRIPTION:
HEC-2 RS: 147500
END DESCRIPTION:
XS GIS Cut Line= 6
2626868.07188746728043.5069915672626682.53235896730130.493510958
2626803.75761909730488.6028676052627580.24170562731569.249116595
2627781.79473085 732424.604084472632434.63714995739428.841685655
#Sta/Elev= 30
       0   42.25   217.5   42.75   349.2    48.3   523.8   48.55     616   44.02
   833.4   48.56     952   41.54  1241.9   45.92  1660.2   44.85  1946.7   32.12
  1959.9    27.1  1999.4   32.35  2264.7   34.38  2505.6   28.38  2572.5   22.14
  2687.9   28.07    2973   27.32  3113.7   12.41 3602.76    3.92    3625 -12.289
    3725 -12.289 3750.81     3.911933.52    7.9812259.98      11 12409.3   17.71
 12554.1   14.41 12760.9    18.4 12784.8   13.76 12800.7   17.31 13103.8   17.95
#Mann= 3 ,0,0
       0     .12       0 3602.76    .045       0 3750.81     .12       0
Bank Sta=3602.76,3750.81
XS Rating Curve= 0 ,0
Exp/Cntr(USF)=0,0
Exp/Cntr=0.3,0.1

Type RM Length L Ch R = 1 ,58035   ,2548.7,2548.7,2548.7
BEGIN DESCRIPTION:
HEC-2 RS: 145000
END DESCRIPTION:
XS GIS Cut Line= 6
2626358.97366803727839.0297992742625485.09585853731124.747573113
 2625255.3036849731770.6713996232625440.53437452733030.137042183
2629163.98196823736933.6472687732631851.22811513740058.453716155
#Sta/Elev= 30
       0   39.72   656.4   40.69   839.9   44.94  1396.5   40.53  1535.7   40.56
  1549.3   43.49  1708.8   42.31  1742.8   45.37  2846.1   44.31  2941.2   38.95
    3060    27.6  3161.9   30.49  3199.2   23.25    3200   19.71  3216.2   14.71
 3281.13   10.03    3760   5.971    3785 -12.439    3875 -12.439    3900   5.981
13407.19    7.5413901.94    9.8513974.91   11.18 13992.9   15.23 14060.6   16.13
 14080.2   19.16 14164.4   17.71 14311.7   21.09 14605.8   18.38 14874.6   20.89
#Mann= 3 ,0,0
       0     .12       0    3760    .045       0    3900     .12       0
Bank Sta=3760,3900
XS Rating Curve= 0 ,0
Exp/Cntr(USF)=0,0
Exp/Cntr=0.3,0.1

Type RM Length L Ch R = 1 ,55486   ,1857.7,1857.7,1857.7
BEGIN DESCRIPTION:
HEC-2 RS: 142500
END DESCRIPTION:
XS GIS Cut Line= 6
2621362.12421734729147.4664821842621625.28132742729491.471420728
2622515.83589658730576.6432226552622875.02708837731129.012811941
2623361.25499938731951.4817683192631121.92967713740433.424617514
#Sta/Elev= 30
       0   32.22    76.6   35.94   241.8   33.81   320.3   39.41   707.7   41.44
   941.1   37.49    1009   39.32  1692.3      37  1989.3   40.59  2146.4   38.06
  2566.8   44.27  2695.8   43.52    2739   41.31  2773.4   30.12  2818.4   22.55
  2836.7   10.84    2950   5.731    2975 -12.599    3095 -12.599    3120   5.711
 13181.3    7.18   13889    8.91 14035.7   12.66 14066.8    17.4 14173.6   22.94
 14183.3   18.16   14193   17.36 14231.4   22.54 14604.9   20.14 14949.2    22.7
#Mann= 3 ,0,0
       0     .12       0    2950    .045       0    3120     .12       0
Bank Sta=2950,3120
XS Rating Curve= 0 ,0
Exp/Cntr(USF)=0,0
Exp/Cntr=0.3,0.1

Type RM Length L Ch R = 1 ,53628   ,3144.9,3144.9,3144.9
BEGIN DESCRIPTION:
HEC-2 RS: 140647; LETTERED XS M
END DESCRIPTION:
Node Name=M
XS GIS Cut Line= 6
2618081.87282596729832.9479352772620917.82512446 731989.25798583
2623604.52902367734177.9478348432625188.58429417736825.068839286
2625923.05940966738863.335534895  2626900.390606739681.971882515
#Sta/Elev= 30
       0   20.17    73.9   22.78   338.1   14.49   589.7   19.59   765.6   12.84
  1177.4   29.85  1625.4   33.81  1711.7   27.46  1990.5   27.84  2196.7   40.95
  2381.6   41.31    2539   33.45  4210.9   41.32    4365   35.53  4395.9   27.43
 4401.13   17.58  4416.9   12.96 4472.11    5.67    4495 -12.719    4605 -12.719
 4629.86    5.7610213.32    8.78 11291.3   12.28 11664.4   21.07 12008.3   18.79
 12066.9   22.55 12101.4   17.62 13280.9   15.25   13296   20.97 13558.5   17.49
#Mann= 3 ,0,0
       0     .12       0 4472.11    .045       0 4629.86     .12       0
Bank Sta=4472.11,4629.86
XS Rating Curve= 0 ,0
Exp/Cntr(USF)=0,0
Exp/Cntr=0.3,0.1

Type RM Length L Ch R = 1 ,50483   ,2505.7,2505.7,2505.7
BEGIN DESCRIPTION:
HEC-2 RS: 137500
END DESCRIPTION:
XS GIS Cut Line= 6
2616447.27691853730789.8962944342619290.04297241734719.168903382
2619873.32365448735241.0164428262620182.15315116735489.740492851
 2625251.6318661739405.6401725892626554.61789832740392.593817691
#Sta/Elev= 30
       0   26.29    85.3   29.23   250.8   19.59   689.8   25.69    1247   18.44
  1439.9   23.89  1753.3    16.5  2066.7   22.03  3096.6   22.48  3178.5   21.94
    3215   13.47  3255.5   13.59  3275.7   19.41  3470.7   21.02  3533.2   14.07
  3712.7    13.5  3766.8   21.57  3940.7   22.31  4061.3   22.14  4182.8    13.5
  4243.5   23.51  4571.6   18.58  4652.5    7.91 5561.69    6.46    5590 -13.029
    5755 -13.029 5769.01     6.410578.67    7.28 11799.1   22.09 14069.3   22.24
#Mann= 3 ,0,0
       0     .12       0 5561.69    .045       0 5769.01     .12       0
Bank Sta=5561.69,5769.01
XS Rating Curve= 0 ,0
Exp/Cntr(USF)=0,0
Exp/Cntr=0.3,0.1

Type RM Length L Ch R = 1 ,47978   ,2499.2,2499.2,2499.2
BEGIN DESCRIPTION:
HEC-2 RS: 135000
END DESCRIPTION:
XS GIS Cut Line= 6
2615514.66081892731940.5290744942617772.30573559736350.989738754
2617793.76096837736399.9439318552617826.69928348736466.424934832
2618762.42447497738110.7364743822622933.44373475742593.342172272
#Sta/Elev= 30
       0      19   306.1   16.23  1110.2   20.31  1279.2   16.25  1781.4   18.19
  1928.4   15.59  1976.3   17.94  2050.1   16.16  2062.9   18.34  2137.3   18.62
  2341.2   15.88  2444.4    19.4  2562.4   16.64  2643.4   18.24  2761.4   16.28
  3074.7   19.13  3417.4   16.15  3487.5    7.44  3543.9       7 4894.62    5.98
    4915 -13.279    5065 -13.279 5079.44    6.02 11280.8    7.29 11431.2   15.55
 11754.8   14.14 11769.3   12.16 11788.5    14.3 12149.7   20.87 13097.3   21.84
#Mann= 3 ,0,0
       0     .12       0 4894.62    .045       0 5079.44     .12       0
Bank Sta=4894.62,5079.44
XS Rating Curve= 0 ,0
Exp/Cntr(USF)=0,0
Exp/Cntr=0.3,0.1

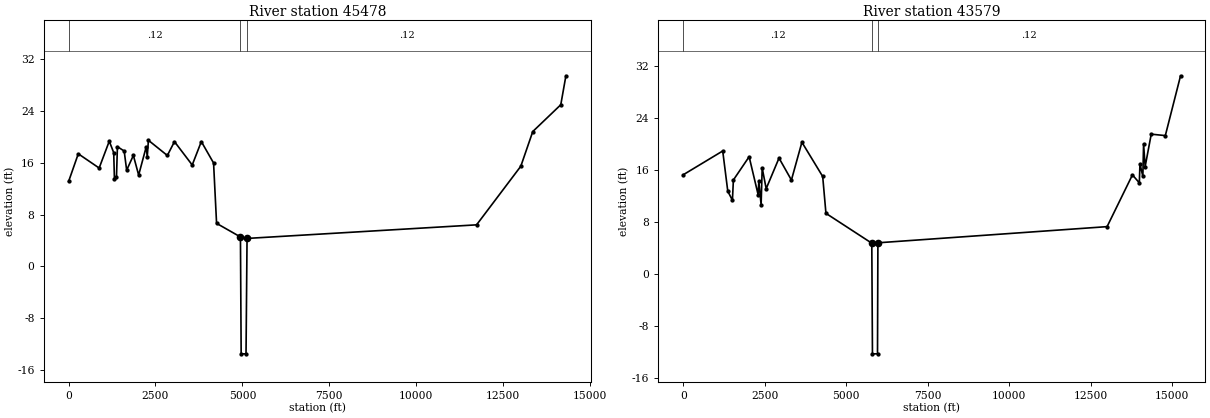
Type RM Length L Ch R = 1 ,45478   ,1892.4,1892.4,1892.4
BEGIN DESCRIPTION:
HEC-2 RS: 132500
END DESCRIPTION:
XS GIS Cut Line= 6
2614547.87738676732418.9242953642614891.41892253735430.838380706
2615079.20897269736275.8936064142615348.58486434737044.502167812
2615613.21169934737637.5142950412622158.63741759743738.062620957
#Sta/Elev= 30
       0   13.11   278.7   17.39   879.1   15.19  1170.3   19.34  1297.9   17.57
  1318.9    13.5  1378.3   13.86  1404.7   18.49  1599.6   17.82  1670.5   14.86
  1863.7   17.14  2015.6    14.1  2233.7   18.47  2263.3   16.91  2296.3   19.48
    2841   17.13  3046.1   19.27    3557   15.66  3819.1   19.28  4171.1   15.97
  4257.6    6.64  4944.3    4.54    4965 -13.529    5105 -13.529 5134.34    4.31
11738.41    6.41 13011.2   15.47 13355.1   20.83 14160.9   24.97 14308.5   29.45
#Mann= 3 ,0,0
       0     .12       0  4944.3    .045       0 5134.34     .12       0
Bank Sta=4944.3,5134.34
XS Rating Curve= 0 ,0
Exp/Cntr(USF)=0,0
Exp/Cntr=0.3,0.1

Type RM Length L Ch R = 1 ,43579   ,,,
BEGIN DESCRIPTION:
HEC-2 RS: 130607; LETTERED XS L
END DESCRIPTION:
Node Name=L
XS GIS Cut Line= 6
2614192.39882371732705.3640515842613594.04585968737085.547323083
2613697.61074653738062.3001128372613998.45148109738456.469654984
2620083.20957427743479.5313214252621165.17611915744463.547595774
#Sta/Elev= 30
       0   15.26  1211.2   18.91  1366.7   12.73    1509   11.35  1538.6   14.46
  2021.8   18.03  2296.4   12.23  2319.6   14.25  2389.1   10.65  2422.2    16.3
  2544.6   13.13  2938.3   17.82  3318.8   14.45  3640.5   20.25  4278.3      15
  4378.1    9.34 5784.76    4.76    5805 -12.219    5960 -12.219 5972.15    4.82
 13003.4     7.3   13781   15.24 13992.4   14.02   14012   16.94 14100.7   15.01
 14122.9      20 14170.8   16.51 14357.9   21.49   14790   21.27 15257.2   30.45
#Mann= 3 ,0,0
       0     .12       0 5784.76    .045       0 5972.15     .12       0
Bank Sta=5784.76,5972.15
XS Rating Curve= 0 ,0
Exp/Cntr(USF)=0,0
Exp/Cntr=0.3,0.1
LCMann Table=0

Chan Stop Cuts=-1
Use User Specified Reach Order=0
Composite Channel Slope=5

--- StanleyCreek.g08 (geometry) ---

Geom Title=Proposed Conditions
Program Version=6.60

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
River Reach=River 1         ,Reach 1

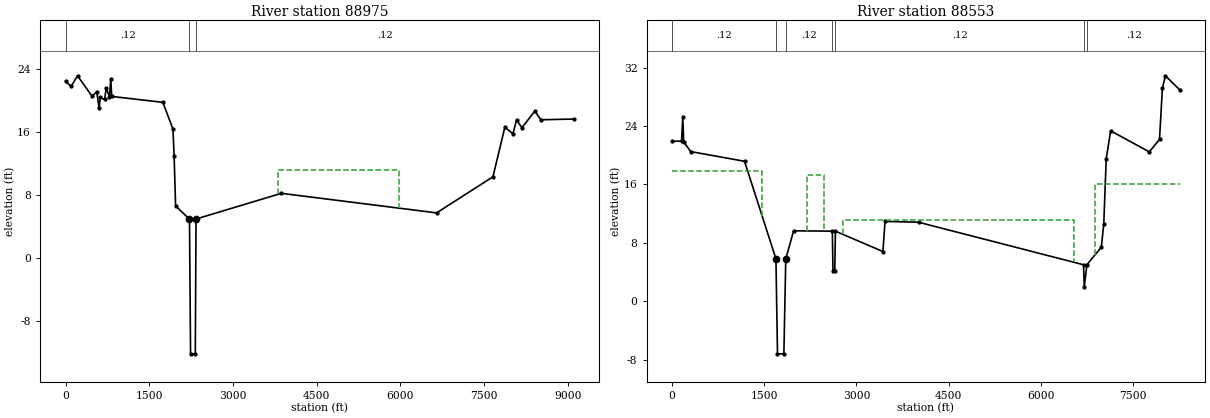
Type RM Length L Ch R = 1 ,88975   ,422.1,422.1,422.1
BEGIN DESCRIPTION:
HEC-2 RS: 175925; LETTERED XS O
END DESCRIPTION:
Node Name=O
XS GIS Cut Line= 6
2640588.85736791740158.6974255812639256.61391338 740740.78241696
2637208.91381491741473.6215394142634953.36176664743102.688214742
2633117.50385446744416.7883676932632743.28891142744631.481986932
#Sta/Elev= 30
       0   22.44     101   21.81   215.2   23.15   476.6   20.55   559.9   21.12
   601.9   19.04   623.4    20.4   699.2   20.15   730.8    21.6     788   20.47
   810.9    22.8   827.4   20.53    1745   19.78  1924.4   16.38  1945.3   13.03
  1972.1    6.65 2220.74    4.96    2240 -12.119    2325 -12.119    2338   4.981
 3866.39    8.24  6647.2    5.76  7656.7   10.34  7869.2   16.62  8014.5    15.8
  8079.1   17.53  8175.9   16.57  8406.1   18.67  8516.6   17.57  9100.2   17.66
#Mann= 3 ,0,0
       0     .12       0 2220.74    .045       0    2338     .12       0
#XS Ineff= 3 ,-1
       0    1350   17.85    3800    5965   11.14    8410    9101   16.08
Permanent Ineff=
       F       F       F
Bank Sta=2220.74,2338
XS Rating Curve= 0 ,0
Exp/Cntr(USF)=0,0
Exp/Cntr=0.5,0.3

Type RM Length L Ch R = 1 ,88553   ,281.1,281.1,281.1
BEGIN DESCRIPTION:
HEC-2 RS: 175431
END DESCRIPTION:
XS GIS Cut Line= 6
2639923.99594256739889.041723748 2638899.3778991740400.570090771
2637408.58032692740974.8775054672633845.05375212741849.243319125
2633485.11936892741882.4818361852632001.39702076741799.782192469
#Sta/Elev= 30
       0    21.9   155.3   21.94   176.3    25.2   190.2   21.85   304.3    20.5
  1180.4   19.17 1691.37     5.8 1716.69    -7.2 1820.37    -7.2 1851.37     5.8
 1979.19    9.65 2608.86     9.6 2619.18     4.2 2648.78     4.2 2658.86     9.6
  3431.5    6.81  3466.2   10.94  4012.7   10.82 6694.81       5 6707.29       2
 6749.81       5 6985.19    7.42  7024.7   10.64  7064.2   19.52  7136.5   23.34
  7765.5   20.46  7931.4   22.18  7978.1   29.18  8027.3   30.88  8264.8   28.92
#Mann= 7 ,-1,0
       0     .12       0 1691.37    .045       0 1851.37     .12       0
 2608.86    .045       0 2658.86     .12       0 6694.81    .045       0
 6749.81     .12       0
#XS Ineff= 4 ,-1
       0    1471   17.85    2199 2476.45   17.32 2784.45 6537.45   11.14
 6875.45    8300   16.08
Permanent Ineff=
       F       F       F       F
Bank Sta=1691.37,1851.37
XS Rating Curve= 0 ,0
Exp/Cntr(USF)=0,0
Exp/Cntr=0.5,0.3