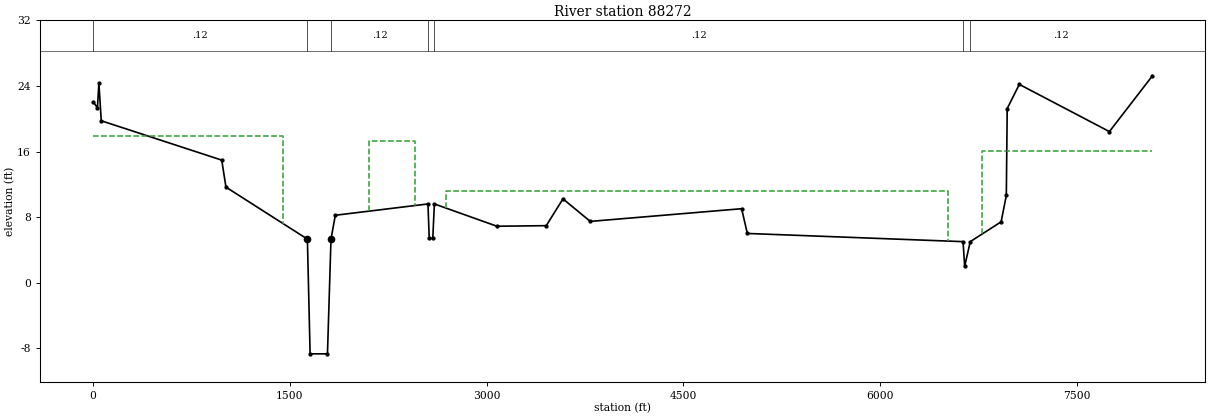
HEC-RAS study StanleyCreek.prj: S-26-105 over Stanley Creek

--- StanleyCreek.g08 (geometry) --- (continued)

Type RM Length L Ch R = 4 ,88426   ,,,
BEGIN DESCRIPTION:
S-105 Multi Opening
END DESCRIPTION:
Bridge Culvert--1,0,-1,-1, 0
Deck Dist Width WeirC Skew NumUp NumDn MinLoCord MaxHiCord MaxSubmerge Is_Ogee
110,35,2.6,0, 143, 143, , , 0.98, 0, 2,2,,
       0  527.45  577.45  627.45  677.45  727.45  777.45  827.45  877.45  927.45
  977.45 1027.45 1077.45 1127.45 1177.45 1227.45 1277.45 1327.45 1377.45 1427.45
 1477.45 1527.45 1577.45 1579.99    1580    2090 2090.01 2127.45 2177.45 2227.45
 2277.45 2327.45 2377.45 2427.45 2477.45 2527.45 2577.45 2585.44 2585.45 2675.45
 2675.46 2677.45 2727.45 2777.45 2827.45 2877.45 2927.45 2977.45 3027.45 3077.45
 3127.45 3177.45 3227.45 3277.45 3327.45 3377.45 3427.45 3477.45 3527.45 3577.45
 3627.45 3677.45 3727.45 3777.45 3827.45 3877.45 3927.45 3977.45 4027.45 4077.45
 4127.45 4177.45 4227.45 4277.45 4327.45 4377.45 4427.45 4477.45 4527.45 4577.45
 4627.45 4677.45 4727.45 4777.45 4827.45 4877.45 4927.45 4977.45 5027.45 5077.45
 5127.45 5177.45 5227.45 5277.45 5327.45 5377.45 5427.45 5477.45 5877.45 5927.45
 5977.45 6027.45 6077.45 6127.45 6177.45 6227.45 6277.45 6327.45 6377.45 6427.45
 6477.45 6527.45 6577.45 6627.45 6646.44 6646.45 6766.45 6766.46 6777.45 6827.45
 6877.45 6927.45 6977.45 7027.45 7077.45 7127.45 7177.45 7227.45 7277.45 7327.45
 7377.45 7427.45 7477.45 7527.45 7577.45 7627.45 7677.45 7727.45 7777.45 7827.45
 7877.45 7927.45    8300
      22   20.18      20   19.81   19.66   19.41   19.38   19.06      19   18.56
   18.13   17.91   17.88   18.02   18.09   18.13   17.91   17.94   17.97   17.84
   17.84   17.94   17.94  17.947  17.947  17.931  17.931   17.93   17.84    17.8
   17.78   17.72   17.56   17.38   17.31   17.34   17.56  17.679  17.679  17.508
  17.508   17.47   16.75   16.31      16   15.75   15.47   15.13   14.81   14.53
   14.28   14.06      14   13.84   13.82    13.8   13.79   13.75   13.59   13.47
   13.34   13.31   13.25   13.22   13.19   13.09   13.06   13.03   13.06   13.13
   13.19   13.19   13.13   13.03   13.03   12.97   12.97   12.91   12.78   12.78
   12.78   12.44   12.22   12.09   11.91   11.94      12   12.06   12.06   12.03
      12   11.94   11.84   11.75   11.75   11.73   11.72   11.69   11.62   11.56
   11.49   11.43   11.36    11.3   11.23   11.17   11.13   11.31   11.72   12.38
   13.25   14.12   14.77   15.17   15.25   15.25   15.62   15.62   15.65   15.81
   16.07   16.45   16.92    17.4   17.89   18.37   18.86   19.33   19.74   20.08
   19.74   20.25   20.88   21.28   21.89   22.39   22.87    23.8   24.47   25.25
    25.5   25.94      29
                                                                                
                                                                                
                                  15.885  15.869
                                                                  15.227  15.227
                                                                                
                                                                                
                                                                                
                                                                                
                                                                                
                                                                                
                                                                                
                                           13.12   13.47
                                                                                
                                                                                
                        
       0  467.45  517.45  567.45  617.45  667.45  717.45  767.45  817.45  867.45
  917.45  967.45 1017.45 1067.45 1117.45 1167.45 1217.45 1267.45 1317.45 1367.45
 1417.45 1467.45 1517.45 1519.99    1520    2030 2030.01 2067.45 2117.45 2167.45
 2217.45 2267.45 2317.45 2367.45 2417.45 2467.45 2517.45 2525.44 2525.45 2615.45
 2615.46 2617.45 2667.45 2717.45 2767.45 2817.45 2867.45 2917.45 2967.45 3017.45
 3067.45 3117.45 3167.45 3217.45 3267.45 3317.45 3367.45 3417.45 3467.45 3517.45
 3567.45 3617.45 3667.45 3717.45 3767.45 3817.45 3867.45 3917.45 3967.45 4017.45
 4067.45 4117.45 4167.45 4217.45 4267.45 4317.45 4367.45 4417.45 4467.45 4517.45
 4567.45 4617.45 4667.45 4717.45 4767.45 4817.45 4867.45 4917.45 4967.45 5017.45
 5067.45 5117.45 5167.45 5217.45 5267.45 5317.45 5367.45 5417.45 5817.45 5867.45
 5917.45 5967.45 6017.45 6067.45 6117.45 6167.45 6217.45 6267.45 6317.45 6367.45
 6417.45 6467.45 6517.45 6567.45 6586.44 6586.45 6706.45 6706.46 6717.45 6767.45
 6817.45 6867.45 6917.45 6967.45 7017.45 7067.45 7117.45 7167.45 7217.45 7267.45
 7317.45 7367.45 7417.45 7467.45 7517.45 7567.45 7617.45 7667.45 7717.45 7767.45
 7817.45 7867.45    8100
      22   20.18      20   19.81   19.66   19.41   19.38   19.06      19   18.56
   18.13   17.91   17.88   18.02   18.09   18.13   17.91   17.94   17.97   17.84
   17.84   17.94   17.94  17.947  17.947  17.931  17.931   17.93   17.84    17.8
   17.78   17.72   17.56   17.38   17.31   17.34   17.56  17.679  17.679  17.508
  17.508   17.47   16.75   16.31      16   15.75   15.47   15.13   14.81   14.53
   14.28   14.06      14   13.84   13.82    13.8   13.79   13.75   13.59   13.47
   13.34   13.31   13.25   13.22   13.19   13.09   13.06   13.03   13.06   13.13
   13.19   13.19   13.13   13.03   13.03   12.97   12.97   12.91   12.78   12.78
   12.78   12.44   12.22   12.09   11.91   11.94      12   12.06   12.06   12.03
      12   11.94   11.84   11.75   11.75   11.73   11.72   11.69   11.62   11.56
   11.49   11.43   11.36    11.3   11.23   11.17   11.13   11.31   11.72   12.38
   13.25   14.12   14.77   15.17   15.25   15.25   15.62   15.62   15.65   15.81
   16.07   16.45   16.92    17.4   17.09   18.37   18.86   19.33   19.74   20.08
   19.74   20.25   20.88   21.28   21.89   22.39   22.87    23.8   24.47   25.25
    25.5   25.94      29
                                                                                
                                                                                
                                  15.885  15.869
                                                                  15.227  15.227
                                                                                
                                                                                
                                                                                
                                                                                
                                                                                
                                                                                
                                                                                
                                           13.12   13.47
                                                                                
                                                                                
                        
Pier Skew, UpSta & Num, DnSta & Num=  ,1610, 2 ,1550, 2 , 0 , 0 , 0 ,,
     1.5     1.5
  -10.56 15.8845
     1.5     1.5
  -10.56 15.8845
Pier Skew, UpSta & Num, DnSta & Num=  ,1640, 2 ,1580, 2 , 0 , 0 , 0 ,,
     1.5     1.5
  -10.56 15.8845
     1.5     1.5
  -10.56 15.8845
Pier Skew, UpSta & Num, DnSta & Num=  ,1670, 2 ,1610, 2 , 0 , 0 , 0 ,,
     1.5     1.5
  -10.56 15.8845
     1.5     1.5
  -10.56 15.8845
Pier Skew, UpSta & Num, DnSta & Num=  ,1700, 2 ,1640, 2 , 0 , 0 , 0 ,,
     1.5     1.5
  -10.56 15.8845
     1.5     1.5
  -10.56 15.8845
Pier Skew, UpSta & Num, DnSta & Num=  ,1730, 2 ,1670, 2 , 0 , 0 , 0 ,,
     1.5     1.5
  -10.56 15.8845
     1.5     1.5
  -10.56 15.8845
Pier Skew, UpSta & Num, DnSta & Num=  ,1760, 2 ,1700, 2 , 0 , 0 , 0 ,,
     1.5     1.5
  -10.56 15.8845
     1.5     1.5
  -10.56 15.8845
Pier Skew, UpSta & Num, DnSta & Num=  ,1790, 2 ,1730, 2 , 0 , 0 , 0 ,,
     1.5     1.5
  -10.56 15.8845
     1.5     1.5
  -10.56 15.8845
Pier Skew, UpSta & Num, DnSta & Num=  ,1820, 2 ,1760, 2 , 0 , 0 , 0 ,,
     1.5     1.5
  -10.56 15.8845
     1.5     1.5
  -10.56 15.8845
Pier Skew, UpSta & Num, DnSta & Num=  ,1850, 2 ,1790, 2 , 0 , 0 , 0 ,,
     1.5     1.5
  -10.56 15.8845
     1.5     1.5
  -10.56 15.8845
Pier Skew, UpSta & Num, DnSta & Num=  ,1880, 2 ,1820, 2 , 0 , 0 , 0 ,,
     1.5     1.5
  -10.56 15.8845
     1.5     1.5
  -10.56 15.8845
Pier Skew, UpSta & Num, DnSta & Num=  ,1910, 2 ,1850, 2 , 0 , 0 , 0 ,,
     1.5     1.5
  -10.56 15.8845
     1.5     1.5
  -10.56 15.8845
Pier Skew, UpSta & Num, DnSta & Num=  ,1940, 2 ,1880, 2 , 0 , 0 , 0 ,,
     1.5     1.5
  -10.56 15.8845
     1.5     1.5
  -10.56 15.8845
Pier Skew, UpSta & Num, DnSta & Num=  ,1970, 2 ,1910, 2 , 0 , 0 , 0 ,,
     1.5     1.5
  -10.56 15.8845
     1.5     1.5
  -10.56 15.8845
Pier Skew, UpSta & Num, DnSta & Num=  ,2000, 2 ,1940, 2 , 0 , 0 , 0 ,,
     1.5     1.5
  -10.56 15.8845
     1.5     1.5
  -10.56 15.8845
Pier Skew, UpSta & Num, DnSta & Num=  ,2030, 2 ,1970, 2 , 0 , 0 , 0 ,,
     1.5     1.5
  -10.56 15.8845
     1.5     1.5
  -10.56 15.8845
Pier Skew, UpSta & Num, DnSta & Num=  ,2060, 2 ,2000, 2 , 0 , 0 , 0 ,,
     1.5     1.5
  -10.56 15.8845
     1.5     1.5
  -10.56 15.8845
Pier Skew, UpSta & Num, DnSta & Num=  ,2615.45, 2 ,2555.45, 2 , 0 , 0 , 0 ,,
     1.5     1.5
  -10.54  15.885
     1.5     1.5
  -10.54  15.885
Pier Skew, UpSta & Num, DnSta & Num=  ,6676.45, 2 ,6616.45, 2 , 0 , 0 , 0 ,,
       2       2
       0      14
       2       2
       0      14
Pier Skew, UpSta & Num, DnSta & Num=  ,6706.45, 2 ,6646.45, 2 , 0 , 0 , 0 ,,
       2       2
       0      14
       2       2
       0      14
Pier Skew, UpSta & Num, DnSta & Num=  ,6736.45, 2 ,6676.45, 2 , 0 , 0 , 0 ,,
       2       2
       0      14
       2       2
       0      14
Abutment Skew #Up #Dn= , 3 , 3
 1579.99 1581.991597.179
  13.885  13.885    6.29
 1519.99 1521.991531.559
  13.885  13.885     9.1
Abutment Skew #Up #Dn= , 3 , 3
2075.273 2088.01 2090.01
     7.5  13.869  13.869
2016.873 2028.01 2030.01
     8.3  13.869  13.869
Abutment Skew #Up #Dn= , 3 , 3
 2585.44 2587.442601.894
  13.227  13.227       6
 2525.44 2527.442540.894
  13.227  13.227     6.5
Abutment Skew #Up #Dn= , 3 , 3
2659.006 2673.46 2675.46
       6  13.227  13.227
2599.006 2613.46 2615.46
       6  13.227  13.227
Abutment Skew #Up #Dn= , 3 , 3
 6646.44 6648.44 6659.74
    10.9    10.9    5.25
 6586.44 6588.44 6599.74
    10.9    10.9    5.25
Abutment Skew #Up #Dn= , 3 , 3
 6752.66 6764.46 6766.46
       5    10.9    10.9
 6692.66 6704.46 6706.46
       5    10.9    10.9
BR Coef=-1 , 0 , 0 ,, 0 ,,,0.8,0,,1,
WSPro=,,,, 1 ,,,, 0 ,,,, 0 ,,,,-1 ,-1 ,-1 , 0 , 0 , 0 , 0 , 0
BR Coef=-1 , 0 , 0 ,, 0 ,,,0.8,0,,1,
WSPro=,,,, 1 ,,,, 0 ,,,, 0 ,,,,-1 ,-1 ,-1 , 0 , 0 , 0 , 0 , 0
BR Coef=-1 , 0 , 0 ,, 0 ,,,0.8,0,,1,
WSPro=,,,, 1 ,,,, 0 ,,,, 0 ,,,,-1 ,-1 ,-1 , 0 , 0 , 0 , 0 , 0
BC Mult= 3 ,0,2400,0,2335
BC Mult= 3 ,2300,5000,2235,4935
BC Mult= 3 ,4900,8264.8,4835,8076.3
BC Design=,, 0 ,, 0 ,,,,,,
BC Use User HTab Curves=0
BC User HTab FreeFlow(D)= 0

Type RM Length L Ch R = 1 ,88272   ,1871.6,1871.6,1871.6
BEGIN DESCRIPTION:
HEC-2 RS: 175405
END DESCRIPTION:
XS GIS Cut Line= 6
2639759.10162326 739641.054175242638739.93718149740164.078255589
2637110.02084291740765.7370482342635698.68947809741068.115000988
2633648.35548859741599.1871794712632022.55717049 741532.54762993
#Sta/Elev= 30
       0   22.07    33.4   21.34    44.3   24.34    62.4   19.75   980.8   14.95
  1013.1   11.65 1633.84    5.31 1654.64   -8.69 1786.96   -8.69 1813.84    5.31
 1846.76    8.22 2553.02     9.6 2562.77     5.4 2589.75     5.4 2602.02     9.6
  3078.8    6.88  3454.9    6.95  3582.3   10.22  3790.6    7.47  4944.3    9.02
  4987.9       6 6632.35       5 6644.83       2 6687.35       5 6922.73    7.42
 6962.24   10.64  6969.1   21.24  7061.2   24.19  7748.2   18.43  8076.3   25.24
#Mann= 7 ,-1,0
       0     .12       0 1633.84    .045       0 1813.84     .12       0
 2553.02    .045       0 2602.02     .12       0 6632.35    .045       0
 6687.35     .12       0
#XS Ineff= 4 ,-1
       0    1448   17.85    2102 2453.45   17.32 2687.45 6514.45   11.14
 6778.45    8100   16.08
Permanent Ineff=
       F       F       F       F
Bank Sta=1633.84,1813.84
XS Rating Curve= 0 ,0
Exp/Cntr(USF)=0,0
Exp/Cntr=0.5,0.3

--- StanleyCreek.g15 (geometry) ---

Geom Title=Natural Conditions
Program Version=6.60

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
River Reach=River 1         ,Reach 1

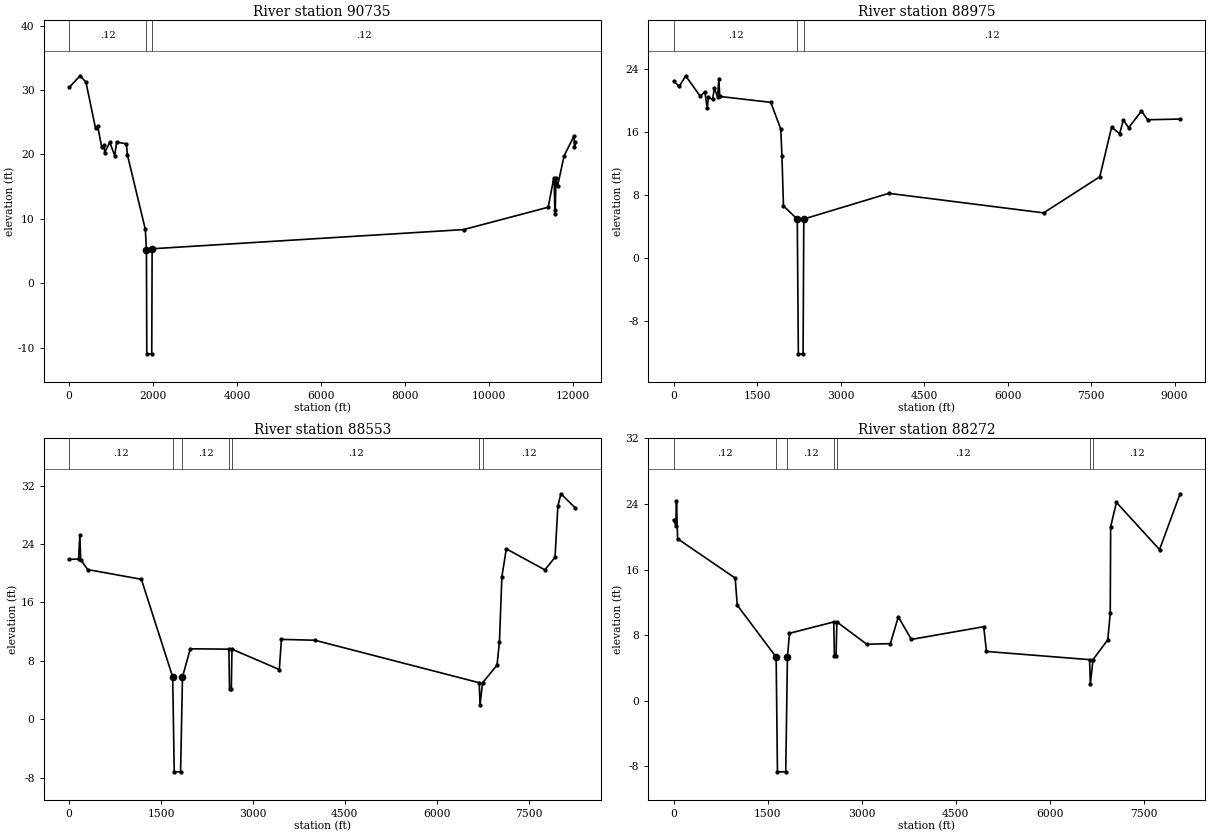
Type RM Length L Ch R = 1 ,90735   ,1760.5,1760.5,1760.5
BEGIN DESCRIPTION:
HEC-2 RS: 177500
END DESCRIPTION:
XS GIS Cut Line= 6
2641004.73305628 741414.91629492 2638080.5689262743377.090479364
2633848.74864333745651.4117456662631514.16699338746660.901066132
2631083.74027524746818.5850923752630388.96432854747037.110463386
#Sta/Elev= 30
       0   30.39   264.1   32.21   402.3   31.22   631.4   24.03   680.3   24.45
   777.5   21.11   837.8    21.5   845.3   20.26   970.2   21.86    1087   19.82
  1134.1   21.93  1365.2   21.63  1388.8   19.94  1816.2    8.35 1842.33    5.14
    1851 -10.979    1969 -10.979 1978.05    5.34  9393.8    8.32   11407   11.79
 11540.1   16.28 11551.1   15.82 11565.3   11.34 11572.9   10.69 11592.8   16.27
 11630.6   15.09 11788.8   19.82 12026.1   22.89   12033   21.09 12056.5   21.97
#Mann= 3 ,0,0
       0     .12       0 1842.33    .045       0 1978.05     .12       0
Bank Sta=1842.33,1978.05
XS Rating Curve= 0 ,0
Exp/Cntr(USF)=0,0
Exp/Cntr=0.3,0.1

Type RM Length L Ch R = 1 ,88975   ,422.1,422.1,422.1
BEGIN DESCRIPTION:
HEC-2 RS: 175925; LETTERED XS O
END DESCRIPTION:
Node Name=O
XS GIS Cut Line= 6
2640588.85736791740158.6974255812639256.61391338 740740.78241696
2637208.91381491741473.6215394142634953.36176664743102.688214742
2633117.50385446744416.7883676932632743.28891142744631.481986932
#Sta/Elev= 30
       0   22.44     101   21.81   215.2   23.15   476.6   20.55   559.9   21.12
   601.9   19.04   623.4    20.4   699.2   20.15   730.8    21.6     788   20.47
   810.9    22.8   827.4   20.53    1745   19.78  1924.4   16.38  1945.3   13.03
  1972.1    6.65 2220.74    4.96    2240 -12.119    2325 -12.119    2338   4.981
 3866.39    8.24  6647.2    5.76  7656.7   10.34  7869.2   16.62  8014.5    15.8
  8079.1   17.53  8175.9   16.57  8406.1   18.67  8516.6   17.57  9100.2   17.66
#Mann= 3 ,0,0
       0     .12       0 2220.74    .045       0    2338     .12       0
Bank Sta=2220.74,2338
XS Rating Curve= 0 ,0
Exp/Cntr(USF)=0,0
Exp/Cntr=0.3,0.1

Type RM Length L Ch R = 1 ,88553   ,281.1,281.1,281.1
BEGIN DESCRIPTION:
HEC-2 RS: 175431
END DESCRIPTION:
XS GIS Cut Line= 6
2639923.99594256739889.041723748 2638899.3778991740400.570090771
2637408.58032692740974.8775054672633845.05375212741849.243319125
2633485.11936892741882.4818361852632001.39702076741799.782192469
#Sta/Elev= 30
       0    21.9   155.3   21.94   176.3    25.2   190.2   21.85   304.3    20.5
  1180.4   19.17 1691.37     5.8 1716.69    -7.2 1820.37    -7.2 1851.37     5.8
 1979.19    9.65 2608.86     9.6 2619.18     4.2 2648.78     4.2 2658.86     9.6
  3431.5    6.81  3466.2   10.94  4012.7   10.82 6694.81       5 6707.29       2
 6749.81       5 6985.19    7.42  7024.7   10.64  7064.2   19.52  7136.5   23.34
  7765.5   20.46  7931.4   22.18  7978.1   29.18  8027.3   30.88  8264.8   28.92
#Mann= 7 ,-1,0
       0     .12       0 1691.37    .045       0 1851.37     .12       0
 2608.86    .045       0 2658.86     .12       0 6694.81    .045       0
 6749.81     .12       0
Bank Sta=1691.37,1851.37
XS Rating Curve= 0 ,0
Exp/Cntr(USF)=0,0
Exp/Cntr=0.3,0.1

Type RM Length L Ch R = 1 ,88272   ,1871.6,1871.6,1871.6
BEGIN DESCRIPTION:
HEC-2 RS: 175405
END DESCRIPTION:
XS GIS Cut Line= 6
2639759.10162326 739641.054175242638739.93718149740164.078255589
2637110.02084291740765.7370482342635698.68947809741068.115000988
2633648.35548859741599.1871794712632022.55717049 741532.54762993
#Sta/Elev= 30
       0   22.07    33.4   21.34    44.3   24.34    62.4   19.75   980.8   14.95
  1013.1   11.65 1633.84    5.31 1654.64   -8.69 1786.96   -8.69 1813.84    5.31
 1846.76    8.22 2553.02     9.6 2562.77     5.4 2589.75     5.4 2602.02     9.6
  3078.8    6.88  3454.9    6.95  3582.3   10.22  3790.6    7.47  4944.3    9.02
  4987.9       6 6632.35       5 6644.83       2 6687.35       5 6922.73    7.42
 6962.24   10.64  6969.1   21.24  7061.2   24.19  7748.2   18.43  8076.3   25.24
#Mann= 7 ,-1,0
       0     .12       0 1633.84    .045       0 1813.84     .12       0
 2553.02    .045       0 2602.02     .12       0 6632.35    .045       0
 6687.35     .12       0
Bank Sta=1633.84,1813.84
XS Rating Curve= 0 ,0
Exp/Cntr(USF)=0,0
Exp/Cntr=0.3,0.1