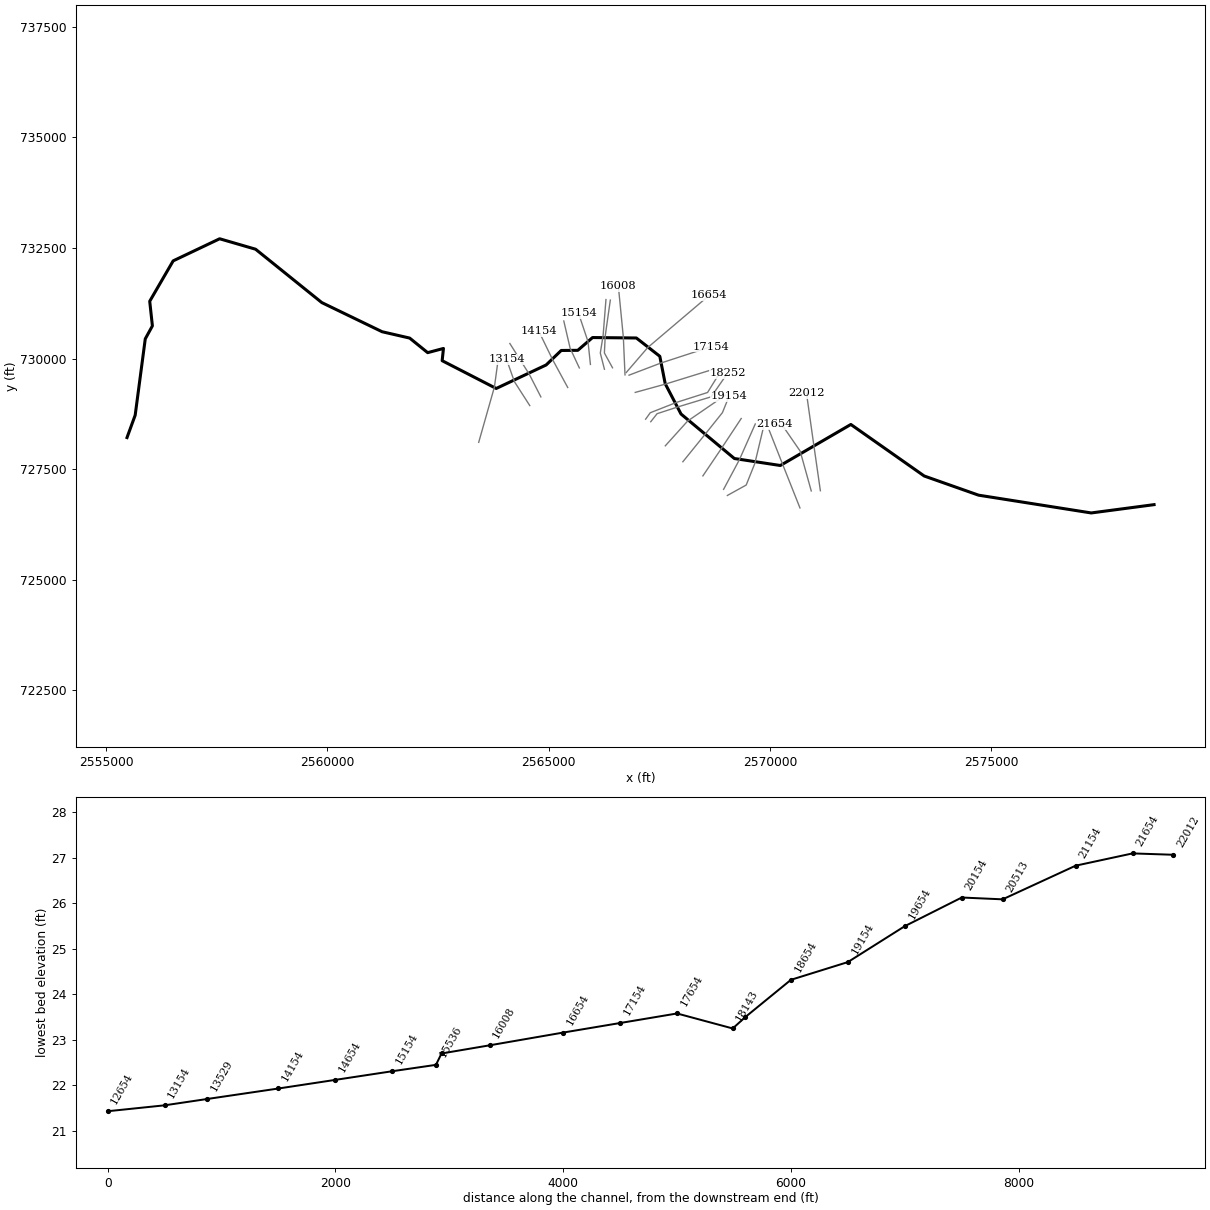
--- JenkinsSwamp.prj (project) ---

Proj Title=S-26-134 over Jenkins Swamp
Current Plan=p02
Default Exp/Contr=0.3,0.1
English Units
Geom File=g04
Geom File=g03
Geom File=g02
Geom File=g05
Flow File=f01
Flow File=f02
Flow File=f03
Plan File=p02
Plan File=p03
Plan File=p04
Plan File=p01
Plan File=p05
Y Axis Title=Elevation
X Axis Title(PF)=Main Channel Distance
X Axis Title(XS)=Station
BEGIN DESCRIPTION:
END DESCRIPTION:
DSS File=dss
DSS Export Rating Curves= 0
DSS Export Rating Curve Sorted= 0
DSS Export Volume Flow Curves= 0
DXF OffsetX= 0
DXF OffsetY= 0
DXF ScaleX= 1
DXF ScaleY= 10

--- JenkinsSwamp.p02 (plan) ---

Plan Title=Sensitivity
Program Version=6.60
Short Identifier=Sensitivity
Geom File=g04
Flow File=f02
Subcritical Flow
K Sum by GR= 0
Std Step Tol= 0.01
Critical Tol= 0.01
Num of Std Step Trials= 20
Max Error Tol= 0.3
Flow Tol Ratio= 0.001
Split Flow NTrial= 30
Split Flow Tol= 0.02
Split Flow Ratio= 0.02
Log Output Level= 0
Friction Slope Method= 1
Unsteady Friction Slope Method= 2
Unsteady Bridges Friction Slope Method= 1
Parabolic Critical Depth
Global Vel Dist= 0 , 0 , 0
Global Log Level= 0
CheckData=True
Encroach Param=-1 ,0,0, 0
Flow Ratio Tolerance=0.1
Flow Ratio Min Ratio=0.5
Flow Ratio Max Ratio=4
Flow Ratio Max Iterations= 10
Computation Interval=1MIN
Output Interval=1HOUR
Instantaneous Interval=1HOUR
Mapping Interval=1HOUR
Computation Time Step Use Courant=        0
Computation Time Step Use Time Series=    0
Computation Time Step Count To Double=0
Computation Time Step Max Doubling=0
Computation Time Step Max Halving=0
Computation Time Step Residence Courant=0
Run HTab= 0
Run UNet= 0
Run Sediment= 0
Run PostProcess= 0
Run WQNet= 0
Run RASMapper= 0
UNET Theta= 1
UNET Theta Warmup= 1
UNET ZTol= 0.02
UNET ZSATol= 0.02
UNET MxIter= 20
UNET Max Iter WO Improvement= 0
UNET MaxInSteps= 0
UNET DtIC= 0
UNET DtMin= 0
UNET MaxCRTS= 20
UNET WFStab= 2
UNET SFStab= 1
UNET WFX= 1
UNET SFX= 1
UNET Gravity=32.17405
UNET 1D Methodology=Finite Difference
UNET DSS MLevel= 4
UNET Pardiso=0
UNET DZMax Abort= 100
UNET Use Existing IB Tables=-1
UNET Froude Reduction=False
UNET Froude Limit= 0.8
UNET Froude Power= 4
UNET D1 Cores= 0
UNET WindReference=Eulerian
UNET WindDragFormulation=Hsu (1988)
UNET D2 Coriolis=0
UNET D2 Cores= 0
UNET D2 Theta= 1
UNET D2 Theta Warmup= 1
UNET D2 Z Tol= 0.01
UNET D2 Volume Tol= 0.01
UNET D2 Max Iterations= 20
UNET D2 Advanced Convergence=0
UNET D2 WS Max Tol=0.15
UNET D2 WS RMS Tol=0.002
UNET D2 WS Stall Tol=1
UNET D2 Equation= 0
UNET D2 RampUpFraction=0.1
UNET D2 TimeSlices= 1
UNET D2 Turbulence Formulation=None
UNET D2 Eddy Viscosity=0.3
UNET D2 Transverse Eddy Viscosity=0.1
UNET D2 Smagorinsky Mixing=0.05
UNET D2 BCVolumeCheck=0
UNET D2 Cores=0
UNET D2 SolverType=PARDISO (Direct)
UNET D2 Minimum Iterations= 3
UNET D2 Maximum Iterations= 30
UNET D2 Restart Number= 10
UNET D2 Relaxation Coeff=1.3
UNET D2 SOR Precondition Iterations= 10
UNET D2 ILUT Maximum Fill= 8
UNET D2 ILUT Tolerance=1E-08
UNET D2 Convergence Tolerance=0.00001
PS Theta= 1
PS WS Tol= 0.01
PS Volume Tol= 0.01
PS Max Iterations= 20
PS Equation= 0
PS Advance Time Step=-1
PS Target Courant=0.9
PS Time Slices= 1
PS Iterate With 2D=0
PS Project Initial WSE from DS=-1
PS Ramp Up Initial WSE from US=-1
PS Cores=0
UNET D1D2 MaxIter= 0
UNET D1D2 ZTol=0.01
UNET D1D2 QTol=0.1
UNET D1D2 MinQTol=1
Write IC File= 0
Write IC File at Fixed DateTime=0
Write IC File at Sim End=0
Echo Input=False
Echo Parameters=False
Echo Output=False
Write Detailed= 0
HDF Write Warmup=0
HDF Write Time Slices=0
HDF Flush=0
HDF Compression= 1
HDF Chunk Size= 1
HDF Spatial Parts= 1
HDF Use Max Rows=0
HDF Fixed Rows= 1
Calibration Method= 0
Calibration Iterations= 20
Calibration Max Change=0.05
Calibration Tolerance=0.2
Calibration Maximum=1.5
Calibration Minimum=0.5
Calibration Optimization Method= 1
WQ AD Non Conservative
WQ ULTIMATE=-1
WQ Max Comp Step=1HOUR
WQ Output Interval=15MIN
WQ Output Selected Increments= 0
WQ Create Restart=0
WQ Fixed Restart=0
WQ System Summary=0
WQ Write To DSS=0
Sorting and Armoring Iterations= 10
XS Update Threshold= 0.02
Bed Roughness Predictor= 0
Processes Affected by Predictor=Sediment Only
Hydraulics Update Threshold= 0.02
Energy Slope Method= 1
Volume Change Method= 1
Sediment Retention Method= 0
Sediment TS Multiplier= 1
Warm Up Method= 0
XS Weighting Method= 0
Number of US Weighted Cross Sections= 1
Number of DS Weighted Cross Sections= 1
Upstream XS Weight=0
Main XS Weight=1
Downstream XS Weight=0
Number of DS XS's Weighted with US Boundary= 1
Upstream Boundary Weight= 1
Weight of XSs Associated with US Boundary= 0
Number of US XS's Weighted with DS Boundary= 1
Downstream Boundary Weight= 0.5
Weight of XSs Associated with DS Boundary= 0.5
Percentile Method= 0
Sediment Output Level= 3
Mass or Volume Output= 0
Output Increment Type= 1
Profile and TS Output Increment= 1
Transport Output Increment 1
XS Output Flag= 0
XS Output Increment= 10
Read HDF5 Sediment Hotstart= 0
Sediment Hotstart Type= 0
Write Gradation File= 0
Read Gradation Hotstart= 0
Write HDF5 File= 1
Write Binary Output= 1
Write DSS Sediment File= 0
DSS Sediment Output Type= 1
SV Curve= 0
Specific Gage Flag= 0
Subcell Erosion Methods= 0
Subcell Deposition Methods= 0
Advection Scheme= 1
Matrix Solver= 0
Implicit Weighting Factor= 1
Maximum Outer Loop Convergence Iterations= 5
Convergence Maximum Absolute= 0.001
Convergence RMSE= 0.0001
Grain Fractions Max Abs Error= 0.001
Max Subgrid Regions= 1
Max Subgrid Length Scale= 3.402823E+38
Initial Layer Thickness= 3
Min Layer Thickness= 0.1
Max Layer Thickness= 6
Number of Layers= 5

--- JenkinsSwamp.p01 (plan) ---

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Plan Title=Proposed Conditions
Short Identifier=Proposed
Geom File=g02
Flow File=f01
DSS File=dss

--- JenkinsSwamp.p03 (plan) ---

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Plan Title=Natural Conditions
Short Identifier=Natural
Geom File=g03
Flow File=f01

--- JenkinsSwamp.p04 (plan) ---

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Plan Title=Existing Conditions
Short Identifier=Existing
Geom File=g04
Flow File=f01
DSS File=dss

--- JenkinsSwamp.p05 (plan) ---

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Plan Title=Duplicate Effective
Short Identifier=DE
Geom File=g05
Flow File=f03
DSS File=dss

--- JenkinsSwamp.f02 (steady flow) ---

Flow Title=USGS Regression Equations-Sensitivity
Program Version=6.60
Number of Profiles= 3
Profile Names=-3 ft,100 Yr,+3 ft
River Rch & RM=Jenkins Swamp,Reach-1         ,22012
     840     840     840
River Rch & RM=Jenkins Swamp,Reach-1         ,12154
    1630    1630    1630
River Rch & RM=Jenkins Swamp,Reach-1         ,4154
    2080    2080    2080
River Rch & RM=Jenkins Swamp,Reach-1         ,2576
    2130    2130    2130
River Rch & RM=Jenkins Swamp,Reach-1         ,1075
    2360    2360    2360
Boundary for River Rch & Prof#=Jenkins Swamp,Reach-1         , 1
Up Type= 0
Dn Type= 1
Dn Known WS=17.12
Boundary for River Rch & Prof#=Jenkins Swamp,Reach-1         , 2
Up Type= 0
Dn Type= 1
Dn Known WS=20.12
Boundary for River Rch & Prof#=Jenkins Swamp,Reach-1         , 3
Up Type= 0
Dn Type= 1
Dn Known WS=23.12
DSS Import GetInterval= 0
DSS Import GetPeak= 0
DSS Import FillOption= 0

--- JenkinsSwamp.f01 (steady flow) ---

Flow Title=USGS Regression Equations
Program Version=6.60
Number of Profiles= 6
Profile Names=2 Yr,10 Yr,25 Yr,50 Yr,100 Yr,500 Yr
River Rch & RM=Jenkins Swamp,Reach-1         ,22012
     133     374     536     686     840    1230
River Rch & RM=Jenkins Swamp,Reach-1         ,12154
     270     741    1050    1340    1630    2370
River Rch & RM=Jenkins Swamp,Reach-1         ,4154
     350     951    1350    1710    2080    3010
River Rch & RM=Jenkins Swamp,Reach-1         ,2576
     358     973    1380    1750    2130    3080
River Rch & RM=Jenkins Swamp,Reach-1         ,1075
     401    1080    1530    1950    2360    3420
Boundary for River Rch & Prof#=Jenkins Swamp,Reach-1         , 1
Up Type= 0
Dn Type= 3
Dn Slope=0.00035
Boundary for River Rch & Prof#=Jenkins Swamp,Reach-1         , 2
Up Type= 0
Dn Type= 3
Dn Slope=0.00035
Boundary for River Rch & Prof#=Jenkins Swamp,Reach-1         , 3
Up Type= 0
Dn Type= 3
Dn Slope=0.00035
Boundary for River Rch & Prof#=Jenkins Swamp,Reach-1         , 4
Up Type= 0
Dn Type= 3
Dn Slope=0.00035
Boundary for River Rch & Prof#=Jenkins Swamp,Reach-1         , 5
Up Type= 0
Dn Type= 3
Dn Slope=0.00035
Boundary for River Rch & Prof#=Jenkins Swamp,Reach-1         , 6
Up Type= 0
Dn Type= 3
Dn Slope=0.00035
DSS Import GetInterval= 0
DSS Import GetPeak= 0
DSS Import FillOption= 0

--- JenkinsSwamp.f03 (steady flow) ---

Flow Title=FEMA - 100-year Single
Program Version=6.60
Number of Profiles= 1
Profile Names=100-year
River Rch & RM=Jenkins Swamp,Reach-1         ,17859
     566
River Rch & RM=Jenkins Swamp,Reach-1         ,17000
     621
River Rch & RM=Jenkins Swamp,Reach-1         ,16359
     673
River Rch & RM=Jenkins Swamp,Reach-1         ,16000
     621
River Rch & RM=Jenkins Swamp,Reach-1         ,15500
     673
River Rch & RM=Jenkins Swamp,Reach-1         ,14099
     800
River Rch & RM=Jenkins Swamp,Reach-1         ,12500
     913
River Rch & RM=Jenkins Swamp,Reach-1         ,11432
     970
River Rch & RM=Jenkins Swamp,Reach-1         ,7385
    1193
River Rch & RM=Jenkins Swamp,Reach-1         ,5500
    1224
River Rch & RM=Jenkins Swamp,Reach-1         ,5000
    1266
River Rch & RM=Jenkins Swamp,Reach-1         ,1500
    1617
Boundary for River Rch & Prof#=Jenkins Swamp,Reach-1         , 1
Up Type= 0
Dn Type= 1
Dn Known WS=21.4
DSS Import GetInterval= 0
DSS Import GetPeak= 0
DSS Import FillOption= 0

--- JenkinsSwamp.g04 (geometry) ---

Geom Title=Existing
Program Version=6.60

River Reach=Jenkins Swamp   ,Reach-1
Reach XY= 30
      2578677.66       726699.11       2577257.9        726511.6
      2574713.06       726913.41      2573484.98        727346.7
      2571827.56       728511.84      2570234.04       727584.19
      2569195.81       727742.07      2567990.63       728748.12
      2567633.78       729432.19      2567511.81       730052.51
      2566981.91       730466.49      2565992.19        730476.3
      2565658.55       730187.51      2565284.25       730184.43
      2564943.94       729856.73      2563815.79       729325.21
2562594.66679142729953.3861257122562623.83007283730229.904245109
2562267.16308228730134.937704487      2561860.65       730464.31
      2561237.85       730607.93      2559875.92       731266.37
      2558379.21       732473.17      2557567.64       732709.32
      2556517.69       732209.872555987.86927582731296.811984907
2556048.24925956 730739.625104892555887.36296133730447.002726712
2555659.33707716728720.772682855 2555475.0030825728215.481838119

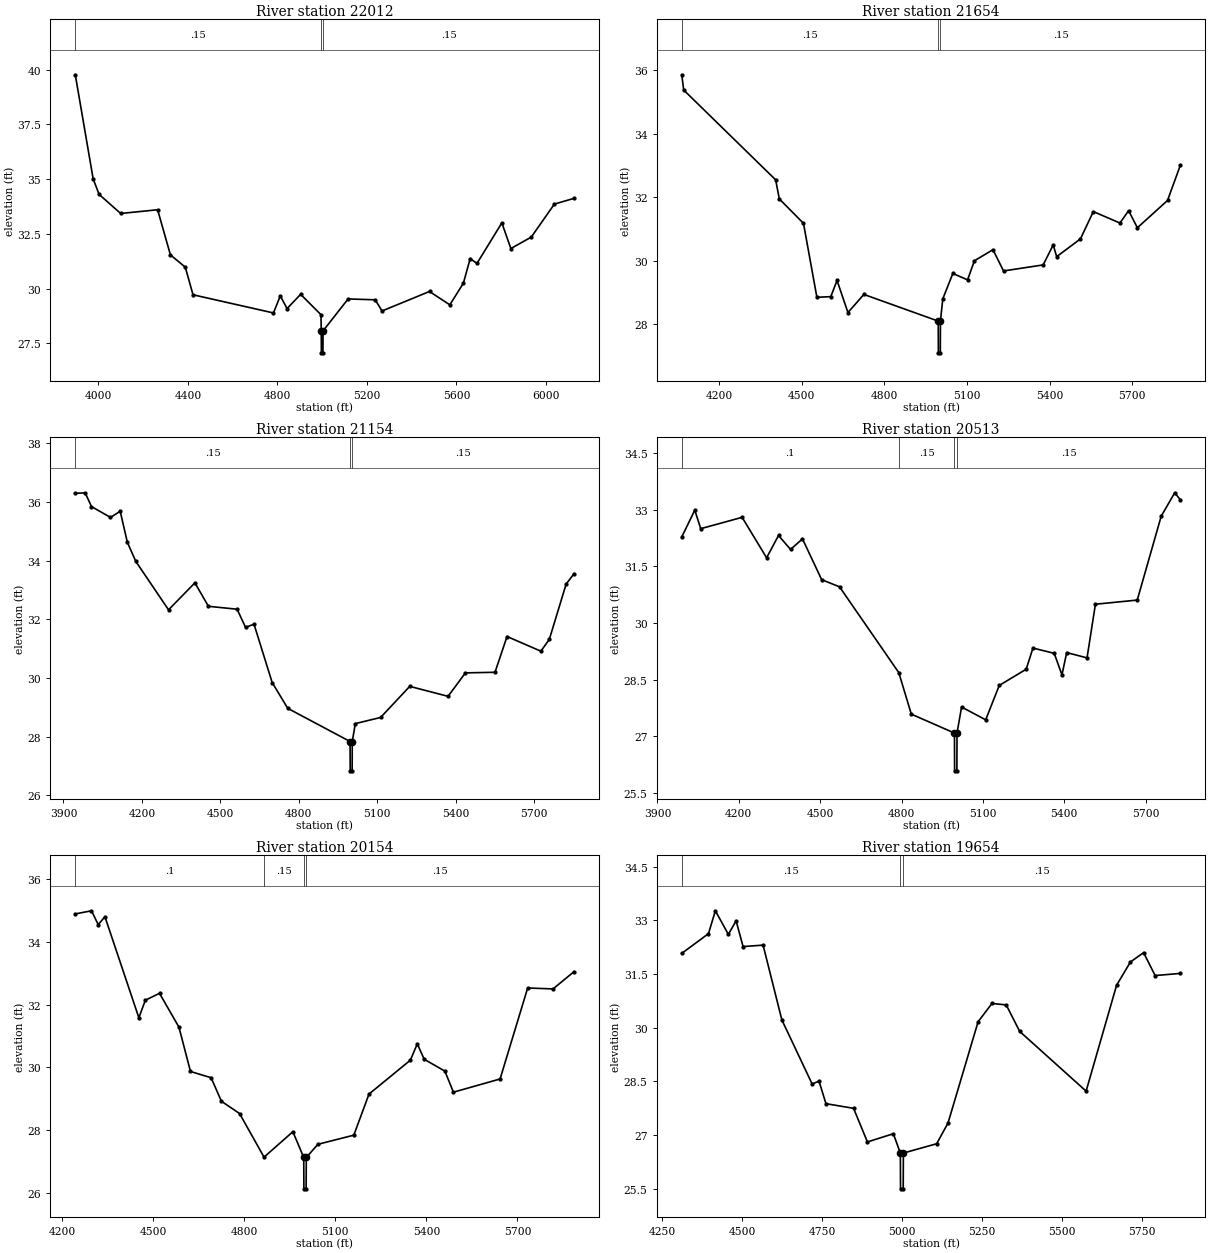
Type RM Length L Ch R = 1 ,22012   ,359,359,359
BEGIN DESCRIPTION:
Jenkins Swamp 36.0
END DESCRIPTION:
XS GIS Cut Line= 3
        2571139.       727013.57      2570982.04       728105.14
      2570825.07       729219.34
#Sta/Elev= 30
  3897.2   39.76    3977   35.01 4003.66    34.3    4100   33.43    4265    33.6
  4322.2   31.54  4388.6   30.98  4423.1   29.72  4782.6   28.89    4813   29.67
  4843.3   29.09  4903.9   29.74  4994.8   28.81    4996   28.07  4996.5   27.07
  5003.5   27.07    5004   28.07    5116   29.53  5237.2   29.49  5267.5   28.98
  5479.6   29.87  5570.4   29.26    5631   30.25  5661.3   31.37  5691.6   31.15
  5802.8      33  5843.1   31.83    5934   32.35  6037.7   33.86  6125.2   34.12
#Mann= 3 ,-1,0
  3897.2     .15       0    4996     .05       0    5004     .15       0
Bank Sta=4996,5004
XS Rating Curve= 0 ,0
Exp/Cntr=0.3,0.1

Type RM Length L Ch R = 1 ,21654   ,500,500,500
BEGIN DESCRIPTION:
Jenkins Swamp 35.0
END DESCRIPTION:
XS GIS Cut Line= 4
      2570933.11       727008.86      2570682.21       727909.67
      2570310.59       728449.04       2570101.5       728518.73
#Sta/Elev= 30
  4064.9   35.86  4071.9   35.38  4405.8   32.55    4419   31.95  4506.8   31.18
  4555.5   28.85  4605.9   28.87  4628.6   29.38  4668.2   28.37    4726   28.94
    4996    28.1  4996.5    27.1  5003.5    27.1    5004    28.1  5012.5    28.8
    5049    29.6  5102.5    29.4  5127.3      30  5194.7   30.35    5233   29.68
  5376.9   29.87  5413.3    30.5    5426   30.13  5512.3   30.69    5559   31.55
  5655.6   31.19  5687.2   31.58  5718.9   31.04  5828.3    31.9  5875.4   33.02
#Mann= 3 ,-1,0
  4064.9     .15       0    4996     .05       0    5004     .15       0
Bank Sta=4996,5004
XS Rating Curve= 0 ,0
Exp/Cntr=0.3,0.1

Type RM Length L Ch R = 1 ,21154   ,641,641,641
BEGIN DESCRIPTION:
Jenkins Swamp 34.0
END DESCRIPTION:
XS GIS Cut Line= 3
      2570677.87       726624.97      2570288.54       727605.29
       2569976.1       728397.93
#Sta/Elev= 30
  3945.2   36.29  3982.9   36.31  4007.1   35.84  4079.7   35.47  4116.9   35.68
  4144.3   34.62  4176.6   33.97  4301.7   32.32  4402.5   33.24  4454.2   32.44
  4563.9   32.34  4596.2   31.72  4628.5   31.83    4698   29.84  4757.6   28.96
  4995.8   27.83  4996.3   26.83  5003.7   26.83  5004.2   27.83  5015.8   28.44
  5112.6   28.65  5223.9   29.71  5370.5   29.37  5436.8   30.17  5549.9   30.19
  5595.9   31.41  5725.2   30.91  5757.5   31.31    5822    33.2    5852   33.55
#Mann= 3 ,-1,0
  3945.2     .15       0  4995.8     .05       0  5004.2     .15       0
Bank Sta=4995.8,5004.2
XS Rating Curve= 0 ,0
Exp/Cntr=0.3,0.1

Type RM Length L Ch R = 1 ,20513   ,359,359,359
BEGIN DESCRIPTION:
Jenkins Swamp 33.0
END DESCRIPTION:
XS GIS Cut Line= 4
      2569037.98       726906.81      2569463.34       727142.55
      2569657.78       727629.12      2569850.66       728435.06
#Sta/Elev= 30
  3989.7   32.28  4037.7   32.99  4059.7    32.5  4212.3    32.8  4302.5   31.73
  4346.6   32.32  4390.8   31.95  4434.9   32.23  4505.6   31.15  4571.5   30.96
    4790   28.69  4836.2   27.59  4995.3   27.09  4995.8   26.09  5004.2   26.09
  5004.7   27.09  5021.5   27.78  5110.4   27.44  5160.4   28.35  5259.8   28.78
  5284.7   29.34  5363.2    29.2  5391.6   28.63  5409.1   29.22  5484.2   29.08
    5515    30.5  5669.3   30.61  5757.6   32.83  5807.4   33.45  5828.7   33.26
#Mann= 4 ,-1,0
  3989.7      .1       0    4790     .15       0  4995.3     .05       0
  5004.7     .15       0
Bank Sta=4995.3,5004.7
XS Rating Curve= 0 ,0
Exp/Cntr=0.3,0.1

Type RM Length L Ch R = 1 ,20154   ,500,500,500
BEGIN DESCRIPTION:
Jenkins Swamp 32.0
END DESCRIPTION:
XS GIS Cut Line= 3
      2568952.67       727045.14      2569308.83       727713.01
      2569668.33       728523.13
#Sta/Elev= 30
  4243.1   34.89  4296.5   34.99  4318.6   34.55  4340.8    34.8  4452.6   31.58
  4473.9   32.14  4520.6   32.36  4584.7   31.28  4622.6   29.87  4690.6   29.67
  4724.6   28.92  4784.3   28.53    4865   27.14    4960   27.95  4995.8   27.13
  4996.3   26.13  5003.7   26.13  5004.2   27.13  5042.6   27.55  5160.8   27.84
  5210.8   29.15  5347.2   30.23  5369.9   30.75  5392.6   30.26  5460.8   29.88
    5489   29.21  5642.7   29.63  5733.6   32.53  5817.2    32.5  5886.3   33.05
#Mann= 4 ,-1,0
  4243.1      .1       0    4865     .15       0  4995.8     .05       0
  5004.2     .15       0
Bank Sta=4995.8,5004.2
XS Rating Curve= 0 ,0
Exp/Cntr=0.3,0.1

Type RM Length L Ch R = 1 ,19654   ,500,500,500
BEGIN DESCRIPTION:
Jenkins Swamp 31.0
END DESCRIPTION:
XS GIS Cut Line= 3
      2568484.86       727349.26      2568869.95       727919.64
      2569350.61       728646.12
#Sta/Elev= 30
  4311.8   32.08  4395.3   32.63  4416.9   33.27  4457.5   32.61  4481.7   32.99
  4503.5   32.27  4566.1   32.31  4624.8   30.22  4719.4   28.43    4741   28.51
  4762.6   27.88    4849   27.75  4892.3   26.81  4973.3   27.04  4995.3    26.5
  4995.8    25.5  5004.2    25.5  5004.7    26.5  5108.8   26.76  5144.3   27.34
  5238.4   30.17  5281.7   30.68  5326.3   30.64  5368.3    29.9    5576   28.23
  5671.4   31.19  5714.7   31.84  5755.8    32.1  5791.8   31.46  5871.1   31.52
#Mann= 3 ,-1,0
  4311.8     .15       0  4995.3     .05       0  5004.7     .15       0
Bank Sta=4995.3,5004.7
XS Rating Curve= 0 ,0
Exp/Cntr=0.3,0.1

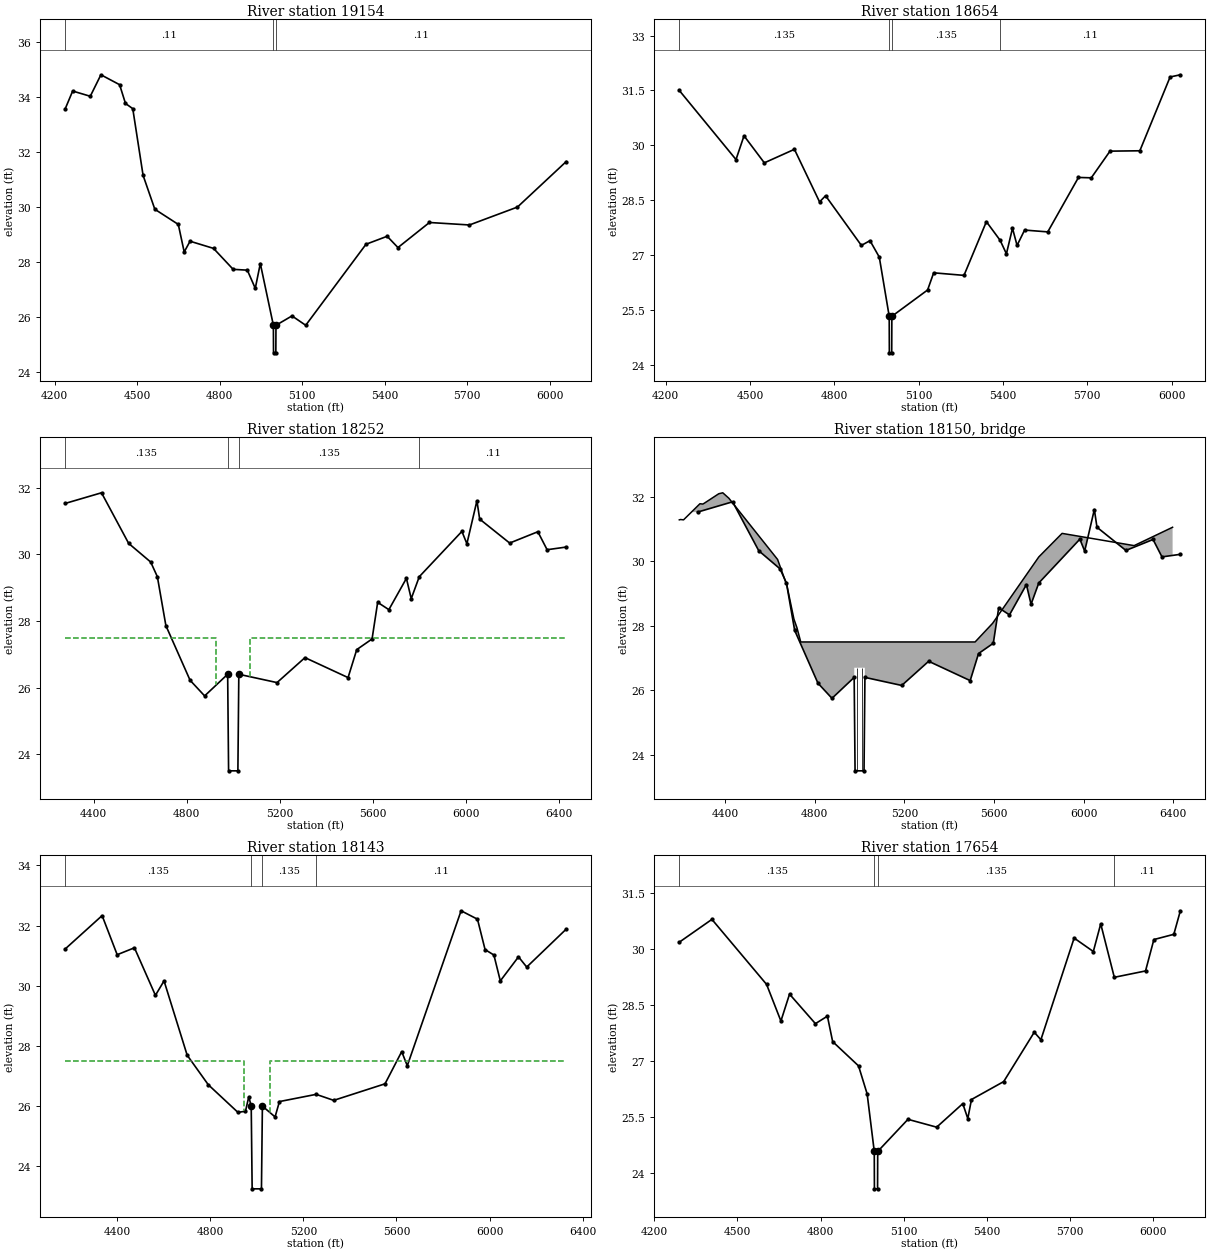
Type RM Length L Ch R = 1 ,19154   ,500,500,500
BEGIN DESCRIPTION:
Jenkins Swamp 30.0
END DESCRIPTION:
XS GIS Cut Line= 4
      2568032.66       727668.98      2568511.63       728260.86
      2568926.19       728778.88      2569074.83       729145.84
#Sta/Elev= 30
  4238.6   33.56  4265.9   34.21  4329.9   34.02  4368.5    34.8  4436.5   34.44
  4457.8   33.76  4484.3   33.57  4521.8   31.15  4564.5   29.92  4649.8   29.37
  4671.2   28.37  4692.5   28.76  4777.8    28.5  4849.1   27.74  4900.6   27.71
  4929.5   27.05  4947.8   27.95  4995.3   25.71  4995.8   24.71  5004.2   24.71
  5004.7   25.71  5062.9   26.05  5112.8   25.71  5331.9   28.65  5408.8   28.94
    5448   28.53  5562.4   29.44  5707.8   29.35  5882.3      30  6059.4   31.65
#Mann= 3 ,-1,0
  4238.6     .11       0  4995.3     .05       0  5004.7     .11       0
Bank Sta=4995.3,5004.7
XS Rating Curve= 0 ,0
Exp/Cntr=0.3,0.1

Type RM Length L Ch R = 1 ,18654   ,401,401,401
BEGIN DESCRIPTION:
Jenkins Swamp 29.0
END DESCRIPTION:
XS GIS Cut Line= 3
      2567635.94       728029.14      2568138.89       728587.66
      2568988.85       729171.92
#Sta/Elev= 30
  4248.4    31.5  4450.1   29.61  4478.6   30.26  4550.9   29.52    4658   29.89
  4747.5   28.45  4768.8   28.62  4896.2   27.26  4926.9   27.39    4960   26.94
  4995.3   25.32  4995.8   24.32  5004.2   24.32  5004.7   25.32  5131.9   26.04
  5153.5   26.51  5261.4   26.44  5341.1   27.91    5390    27.4  5412.4   27.03
    5434   27.73  5450.3   27.26  5477.1   27.68  5559.5   27.63  5668.8   29.12
  5714.4   29.11    5781   29.84  5887.2   29.85  5994.9   31.87  6031.4   31.93
#Mann= 4 ,-1,0
  4248.4    .135       0  4995.3     .05       0  5004.7    .135       0
    5390     .11       0
Bank Sta=4995.3,5004.7
XS Rating Curve= 0 ,0
Exp/Cntr=0.5,0.3

Type RM Length L Ch R = 1 ,18252   ,110,110,110
BEGIN DESCRIPTION:
Jenkins Swamp (Shad Rd) US
END DESCRIPTION:
XS GIS Cut Line= 5
      2567307.04        728573.5      2567450.04       728754.97
      2567917.51       728907.63      2568671.43       729136.79
      2569038.68       729665.59
#Sta/Elev= 30
  4277.2   31.53  4433.5   31.85  4550.3   30.33    4645   29.77  4673.7   29.33
  4710.4   27.86  4814.4   26.22    4877   25.75    4976    26.4    4980    23.5
    5020    23.5    5024    26.4  5188.3   26.15  5308.5    26.9  5493.8    26.3
  5531.1   27.14    5597   27.46  5621.1   28.56  5669.2   28.34  5744.7   29.28
  5765.4   28.67    5800   29.33  5983.3   30.69  6004.8   30.32  6047.9   31.61
  6059.7   31.06  6188.7   30.34  6309.9   30.68  6349.7   30.14  6431.8   30.22
#Mann= 4 ,-1,0
  4277.2    .135       0    4976     .05       0    5024    .135       0
    5800     .11       0
#XS Ineff= 2 , 0
          4927.5    27.5  5072.5            27.5
Permanent Ineff=
       F       F
Bank Sta=4976,5024
XS Rating Curve= 0 ,0
Exp/Cntr=0.5,0.3

Type RM Length L Ch R = 3 ,18150   ,,,
BEGIN DESCRIPTION:
Jenkins Swamp (Shad Rd) TOR
Structure ID: LDS_JKS_03
Approximate Survey Structure
END DESCRIPTION:
Bridge Culvert--1,0,-1,-1, 0
Deck Dist Width WeirC Skew NumUp NumDn MinLoCord MaxHiCord MaxSubmerge Is_Ogee
49,28,3,0, 24, 24, , , 0.95, 0, 2,2,,
  4195.7  4201.4  4214.6  4287.7  4300.6  4305.8  4371.7  4389.6  4416.9  4634.3
    4676  4707.2  4720.8  4737.6  4976.5  4976.5  5023.5  5023.5  5515.7    5594
  5800.1  5903.9  6225.5  6397.1
   31.29    31.3   31.29   31.79   31.78    31.8    32.1   32.13   31.96   30.06
   29.25   28.21   27.94    27.5    27.5    27.5    27.5    27.5    27.5   28.08
   30.14   30.87   30.49   31.06
    3.39    3.39    3.39    3.39    3.39    3.39    3.39    3.39    3.39    3.39
    3.39    3.39    3.39    3.39    3.39    26.7    26.7    3.39    3.39    3.39
    3.39    3.39    3.39    3.39
  4195.7  4201.4  4214.6  4287.7  4300.6  4305.8  4371.7  4389.6  4416.9  4634.3
    4676  4707.2  4720.8  4737.6  4976.5  4976.5  5023.5  5023.5  5515.7    5594
  5800.1  5903.9  6225.5  6397.1
   31.29    31.3   31.29   31.79   31.78    31.8    32.1   32.13   31.96   30.06
   29.25   28.21   27.94    27.5    27.5    27.5    27.5    27.5    27.5   28.08
   30.14   30.87   30.49   31.06
    3.39    3.39    3.39    3.39    3.39    3.39    3.39    3.39    3.39    3.39
    3.39    3.39    3.39    3.39    3.39    26.7    26.7    3.39    3.39    3.39
    3.39    3.39    3.39    3.39
Pier Skew, UpSta & Num, DnSta & Num=  ,4988.3, 2 ,4988.3, 2 , 0 , 0 , 0 ,0,0
       1       1
    18.5    26.7
       1       1
   18.25    26.7
Pier Skew, UpSta & Num, DnSta & Num=  ,5011.8, 2 ,5011.8, 2 , 0 , 0 , 0 ,0,0
       1       1
    18.5    26.7
       1       1
   18.25    26.7
Abutment Skew #Up #Dn= , 2 , 2
  4976.5  4979.5
    26.7   19.05
  4976.5  4979.5
    26.7    18.8
Abutment Skew #Up #Dn= , 2 , 2
  5020.5  5023.5
   19.05    26.7
  5020.5  5023.5
    18.8    26.7
BR Coef=-1 ,-1 , 0 ,1.25, 0 ,,,0.8,0,2,0,
WSPro=,,,, 1 ,,,, 0 ,,,, 0 ,,,,-1 ,-1 ,-1 , 0 , 0 , 0 , 0 , 0
BC Design=,, 0 ,, 0 ,,,,,,
BC HTab HWMax=31.87
BC Use User HTab Curves=0
BC User HTab FreeFlow(D)= 0

Type RM Length L Ch R = 1 ,18143   ,489,489,489
BEGIN DESCRIPTION:
Jenkins Swamp (Shad Rd) DS
END DESCRIPTION:
XS GIS Cut Line= 5
      2567191.15        728631.2      2567296.18       728776.71
      2567895.24       729012.65      2568590.65       729234.29
      2568905.07       729744.39
#Sta/Elev= 30
  4176.7   31.22  4335.5   32.33  4400.2   31.03  4474.3   31.26  4564.5   29.68
  4601.5   30.16  4700.9   27.69  4791.5   26.71  4919.1   25.79  4951.4   25.83
  4965.5   26.31    4976      26    4980   23.25    5020   23.25    5024      26
  5078.5   25.64  5097.2   26.15    5255   26.39  5330.4   26.19  5550.8   26.74
  5622.5   27.81  5646.4   27.34  5877.6   32.49    5948   32.21  5980.6    31.2
  6018.5   31.02  6046.1   30.16  6124.2   30.96  6159.5   30.62  6329.1   31.88
#Mann= 4 ,-1,0
  4176.7    .135       0    4976     .05       0    5024    .135       0
    5255     .11       0
#XS Ineff= 2 , 0
          4943.5    27.5  5056.5            27.5
Permanent Ineff=
       F       F
Bank Sta=4976,5024
XS Rating Curve= 0 ,0
Exp/Cntr=0.5,0.3

Type RM Length L Ch R = 1 ,17654   ,500,500,500
BEGIN DESCRIPTION:
Jenkins Swamp 27.0
END DESCRIPTION:
XS GIS Cut Line= 3
      2566956.61       729236.17      2567640.77       729424.84
       2568690.1       729749.46
#Sta/Elev= 30
  4290.3   30.18  4407.9   30.79  4605.2   29.05  4656.9   28.07    4688   28.79
  4781.4      28  4824.7    28.2  4843.6   27.52    4937   26.87  4968.1   26.12
  4993.8   24.58  4994.3   23.58  5005.7   23.58  5006.2   24.58  5115.4   25.44
    5219   25.23  5313.2   25.86  5331.3   25.46  5344.6   25.97  5460.9   26.45
  5571.1   27.77  5595.1   27.57    5715   30.29  5784.3   29.93    5811   30.67
    5860   29.24  5972.7   29.41  6002.8   30.25  6074.8   30.39  6098.4   31.02
#Mann= 4 ,-1,0
  4290.3    .135       0  4993.8     .05       0  5006.2    .135       0
    5860     .11       0
Bank Sta=4993.8,5006.2
XS Rating Curve= 0 ,0
Exp/Cntr=0.3,0.1

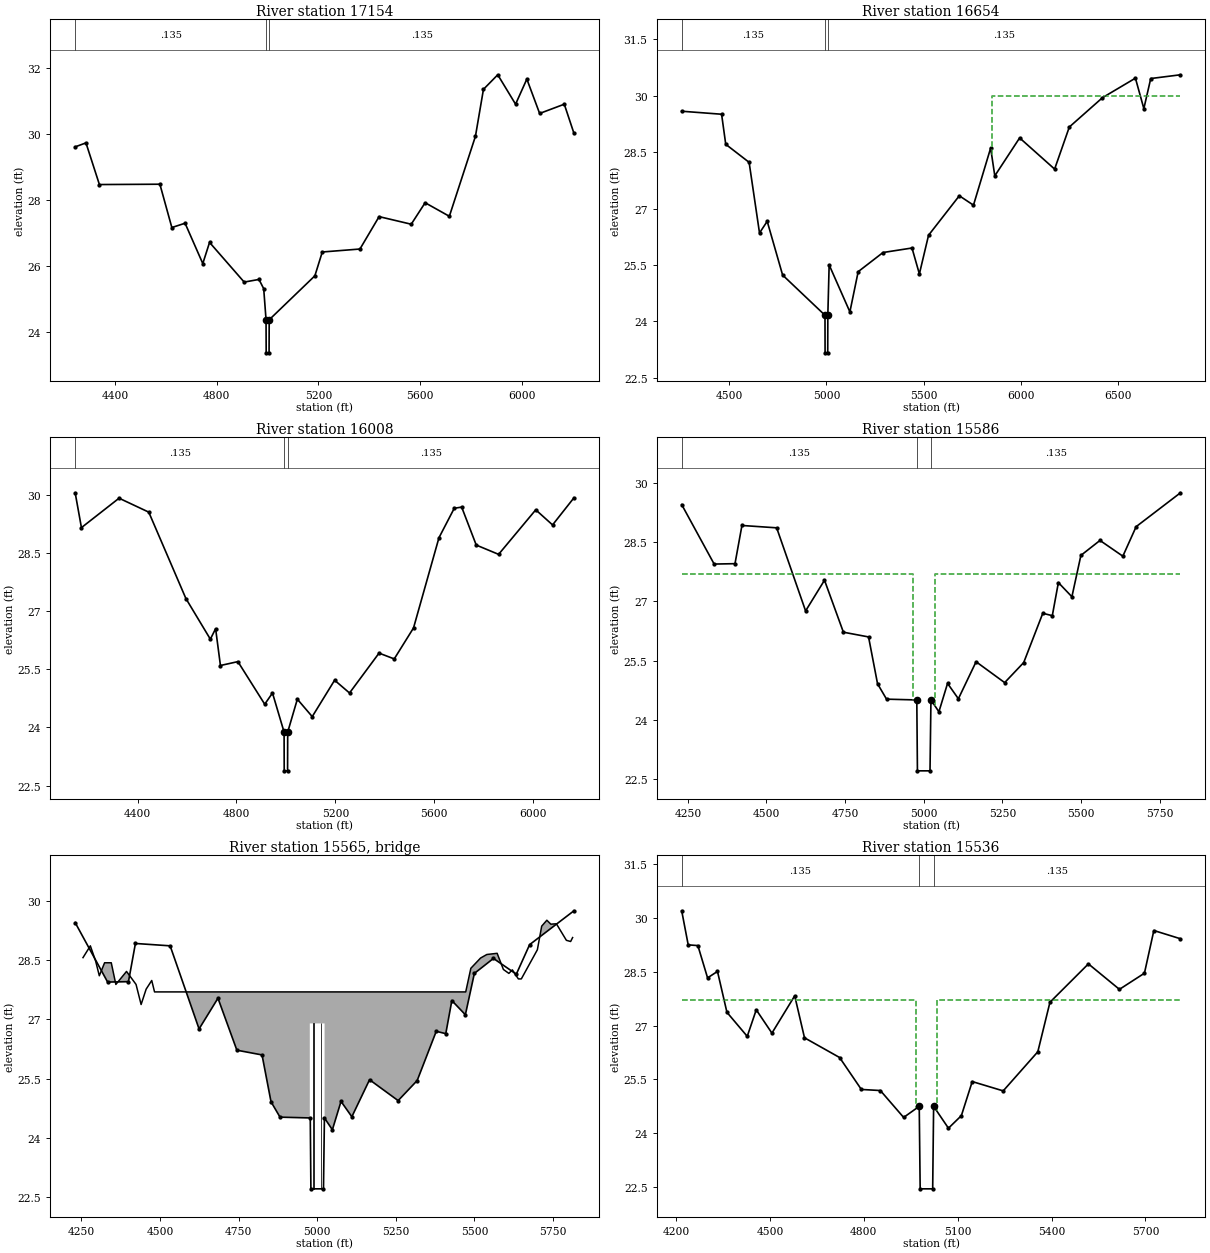
Type RM Length L Ch R = 1 ,17154   ,500,500,500
BEGIN DESCRIPTION:
Jenkins Swamp 26.0
END DESCRIPTION:
XS GIS Cut Line= 3
       2566816.3       729626.04      2567523.35       729895.65
       2568668.2       730269.67
#Sta/Elev= 30
  4243.3    29.6 4285.73   29.72  4338.6   28.46  4576.4   28.47  4623.4   27.16
  4675.4   27.29  4745.1   26.07  4771.7   26.71  4907.8   25.51    4966   25.59
  4984.6   25.31  4993.8   24.37  4994.3   23.37  5005.7   23.37  5006.2   24.37
  5185.8    25.7  5214.9   26.42    5363   26.51  5438.3   27.49  5564.6   27.26
  5619.3   27.91  5714.5    27.5  5817.1   29.92  5848.6   31.34  5904.8   31.78
  5974.9   30.89  6019.2   31.65  6069.5   30.61  6166.4   30.89  6204.4   30.01
#Mann= 3 ,-1,0
  4243.3    .135       0  4993.8     .05       0  5006.2    .135       0
Bank Sta=4993.8,5006.2
XS Rating Curve= 0 ,0
Exp/Cntr=0.3,0.1

Type RM Length L Ch R = 1 ,16654   ,645,645,645
BEGIN DESCRIPTION:
Jenkins Swamp 25.0
END DESCRIPTION:
XS GIS Cut Line= 3
       2566753.9       729686.85      2567239.24       730250.62
      2568626.51       731428.86
#Sta/Elev= 30
  4256.1   29.59  4461.2   29.51  4482.5   28.71  4602.7   28.23  4656.1   26.35
  4695.7   26.66  4774.9   25.23  4992.7   24.16  4993.2   23.16  5006.8   23.16
  5007.3   24.16  5014.1    25.5  5120.7   24.25  5163.3   25.32    5291   25.83
    5440   25.95  5477.9   25.26  5525.1   26.29  5683.2   27.34    5756   27.09
  5844.3   28.61  5865.6   27.87  5993.3   28.88  6173.1   28.05  6248.7   29.17
    6419   29.95  6588.5   30.47  6631.8   29.66  6667.2   30.46  6820.1   30.56
#Mann= 3 ,-1,0
  4256.1    .135       0  4992.7     .05       0  5007.3    .135       0
#XS Ineff= 2 , 0
                            5850              30
Permanent Ineff=
       F       F
Bank Sta=4992.7,5007.3
XS Rating Curve= 0 ,0
Exp/Cntr=0.3,0.1

Type RM Length L Ch R = 1 ,16008   ,423,423,423
BEGIN DESCRIPTION:
Jenkins Swamp 24.0
END DESCRIPTION:
XS GIS Cut Line= 5
2566725.41339533729632.681217799      2566725.36       729633.89
      2566687.81       730483.96      2566574.64       731641.24
2566574.44629964731643.220785965
#Sta/Elev= 30
 4147.89   30.06 4173.24   29.16  4325.4   29.92  4445.5   29.56  4595.6   27.33
  4694.5   26.28  4715.8   26.55  4735.3    25.6  4805.9    25.7  4914.4    24.6
  4945.8   24.89  4992.7   23.88  4993.2   22.88  5006.8   22.88  5007.3   23.88
  5046.3   24.73  5106.5   24.28    5197   25.22  5257.3   24.89  5376.7   25.92
  5438.1   25.77  5516.1   26.57    5619    28.9  5680.8   29.66  5710.8   29.69
  5769.7   28.71  5860.1   28.47  6010.3   29.62  6078.3   29.23 6164.79   29.93
#Mann= 3 ,-1,0
 4147.89    .135       0  4992.7     .05       0  5007.3    .135       0
Bank Sta=4992.7,5007.3
XS Rating Curve= 0 ,0
Exp/Cntr=0.5,0.3

Type RM Length L Ch R = 1 ,15586   ,49,49,49
BEGIN DESCRIPTION:
Jenkins Swamp (HWY-134) US
END DESCRIPTION:
XS GIS Cut Line= 6
2566443.12218896729793.061365811       2566441.4        729796.2
      2566259.63       730127.47      2566278.73       730515.14
      2566393.72        731323.1 2566393.7693293731323.446604946
#Sta/Elev= 30
 4230.42   29.46  4333.6   27.95  4399.9   27.96    4422   28.93  4532.4   28.87
  4624.4   26.76  4684.5   27.54  4744.6   26.22  4824.6    26.1  4853.2   24.91
  4881.8   24.52    4978    24.5    4980    22.7    5020    22.7    5023    24.5
  5048.3    24.2  5075.8   24.92  5110.2   24.53  5166.5   25.47  5257.4   24.94
    5318   25.45  5378.6    26.7  5408.9   26.64  5428.2   27.48  5471.2   27.12
  5499.8   28.17  5560.5   28.55  5633.2   28.15  5675.5    28.9 5816.45   29.76
#Mann= 3 ,-1,0
 4230.42    .135       0    4978     .05       0    5023    .135       0
#XS Ineff= 2 , 0
          4964.5    27.7  5035.5            27.7
Permanent Ineff=
       F       F
Bank Sta=4978,5023
XS Rating Curve= 0 ,0
Exp/Cntr=0.5,0.3

Type RM Length L Ch R = 3 ,15565   ,,,
BEGIN DESCRIPTION:
Jenkins Swamp (HWY-134) TOR
Structure ID: LDS_JKS_02
Approximate Survey Structure
END DESCRIPTION:
Bridge Culvert--1,0,-1,-1, 0
Deck Dist Width WeirC Skew NumUp NumDn MinLoCord MaxHiCord MaxSubmerge Is_Ogee
12,28,3,0, 35, 35, , , 0.95, 0, 2,2,,
  4255.3  4278.7  4295.6  4307.2    4324  4345.2  4359.8  4393.7    4424  4440.1
  4456.1  4473.9  4482.8  4976.5  4976.5  5023.5  5023.5  5472.3  5488.6  5519.5
  5539.4  5572.2  5592.1  5609.5  5620.6  5639.7  5649.1  5700.1  5713.9  5730.3
  5742.9  5760.6  5792.4  5805.9  5812.2
   28.57   28.87   28.48   28.11   28.44   28.44   27.89   28.22   27.89   27.38
   27.77   27.99    27.7    27.7    27.7    27.7    27.7    27.7    28.3   28.56
   28.65   28.68   28.27   28.17   28.26   28.03   28.03   28.77   29.37   29.52
   29.42   29.43   29.01   28.98   29.08
    2.64    2.64    2.64    2.64    2.64    2.64    2.64    2.64    2.64    2.64
    2.64    2.64    2.64    2.64    26.9    26.9    2.64    2.64    2.64    2.64
    2.64    2.64    2.64    2.64    2.64    2.64    2.64    2.64    2.64    2.64
    2.64    2.64    2.64    2.64    2.64
  4255.3  4278.7  4295.6  4307.2    4324  4345.2  4359.8  4393.7    4424  4440.1
  4456.1  4473.9  4482.8  4976.5  4976.5  5023.5  5023.5  5472.3  5488.6  5519.5
  5539.4  5572.2  5592.1  5609.5  5620.6  5639.7  5649.1  5700.1  5713.9  5730.3
  5742.9  5760.6  5792.4  5805.9  5812.2
   28.57   28.87   28.48   28.11   28.44   28.44   27.89   28.22   27.89   27.38
   27.77   27.99    27.7    27.7    27.7    27.7    27.7    27.7    28.3   28.56
   28.65   28.68   28.27   28.17   28.26   28.03   28.03   28.77   29.37   29.52
   29.42   29.43   29.01   28.98   29.08
    2.64    2.64    2.64    2.64    2.64    2.64    2.64    2.64    2.64    2.64
    2.64    2.64    2.64    2.64    26.9    26.9    2.64    2.64    2.64    2.64
    2.64    2.64    2.64    2.64    2.64    2.64    2.64    2.64    2.64    2.64
    2.64    2.64    2.64    2.64    2.64
Pier Skew, UpSta & Num, DnSta & Num=  ,4988.3, 2 ,4988.3, 2 , 0 , 0 , 0 ,0,0
       1       1
    17.7    26.9
       1       1
   17.45    26.9
Pier Skew, UpSta & Num, DnSta & Num=  ,5011.8, 2 ,5011.8, 2 , 0 , 0 , 0 ,0,0
       1       1
    17.7    26.9
       1       1
   17.45    26.9
Abutment Skew #Up #Dn= , 2 , 2
  4976.5  4979.5
    26.9   18.25
  4976.5  4979.5
    26.9      18
Abutment Skew #Up #Dn= , 2 , 2
  5020.5  5023.5
   18.25    26.9
  5020.5  5023.5
      18    26.9
BR Coef=-1 ,-1 , 0 ,1.25, 0 ,,,0.8,0,2,0,
WSPro=,,,, 1 ,,,, 0 ,,,, 0 ,,,,-1 ,-1 ,-1 , 0 , 0 , 0 , 0 , 0
BC Design=,, 0 ,, 0 ,,,,,,
BC HTab HWMax=29.45
BC Use User HTab Curves=0
BC User HTab FreeFlow(D)= 0

Type RM Length L Ch R = 1 ,15536   ,383,383,383
BEGIN DESCRIPTION:
Jenkins Swamp (HWY-134) DS
END DESCRIPTION:
XS GIS Cut Line= 4
      2566260.33       729759.87      2566167.24       730126.52
      2566231.07       730525.36      2566295.07       731334.84
#Sta/Elev= 30
  4217.8    30.2  4238.6   29.25  4269.5   29.23  4300.5   28.33  4332.2   28.51
  4362.4   27.37  4427.3    26.7  4456.1   27.44  4506.2   26.79    4579   27.83
  4610.3   26.66  4722.5   26.11    4792   25.22  4852.8   25.19  4927.2   24.44
    4977   24.75    4980   22.45    5020   22.45    5023   24.75  5070.4   24.14
  5111.7   24.49  5146.4   25.44  5245.4   25.18    5356   26.27  5394.8   27.65
  5517.7   28.72  5616.9   28.01  5696.8   28.46  5726.9   29.65    5812   29.42
#Mann= 3 ,-1,0
  4217.8    .135       0    4977     .05       0    5023    .135       0
#XS Ineff= 2 , 0
          4967.5    27.7  5032.5            27.7
Permanent Ineff=
       F       F
Bank Sta=4977,5023
XS Rating Curve= 0 ,0
Exp/Cntr=0.5,0.3

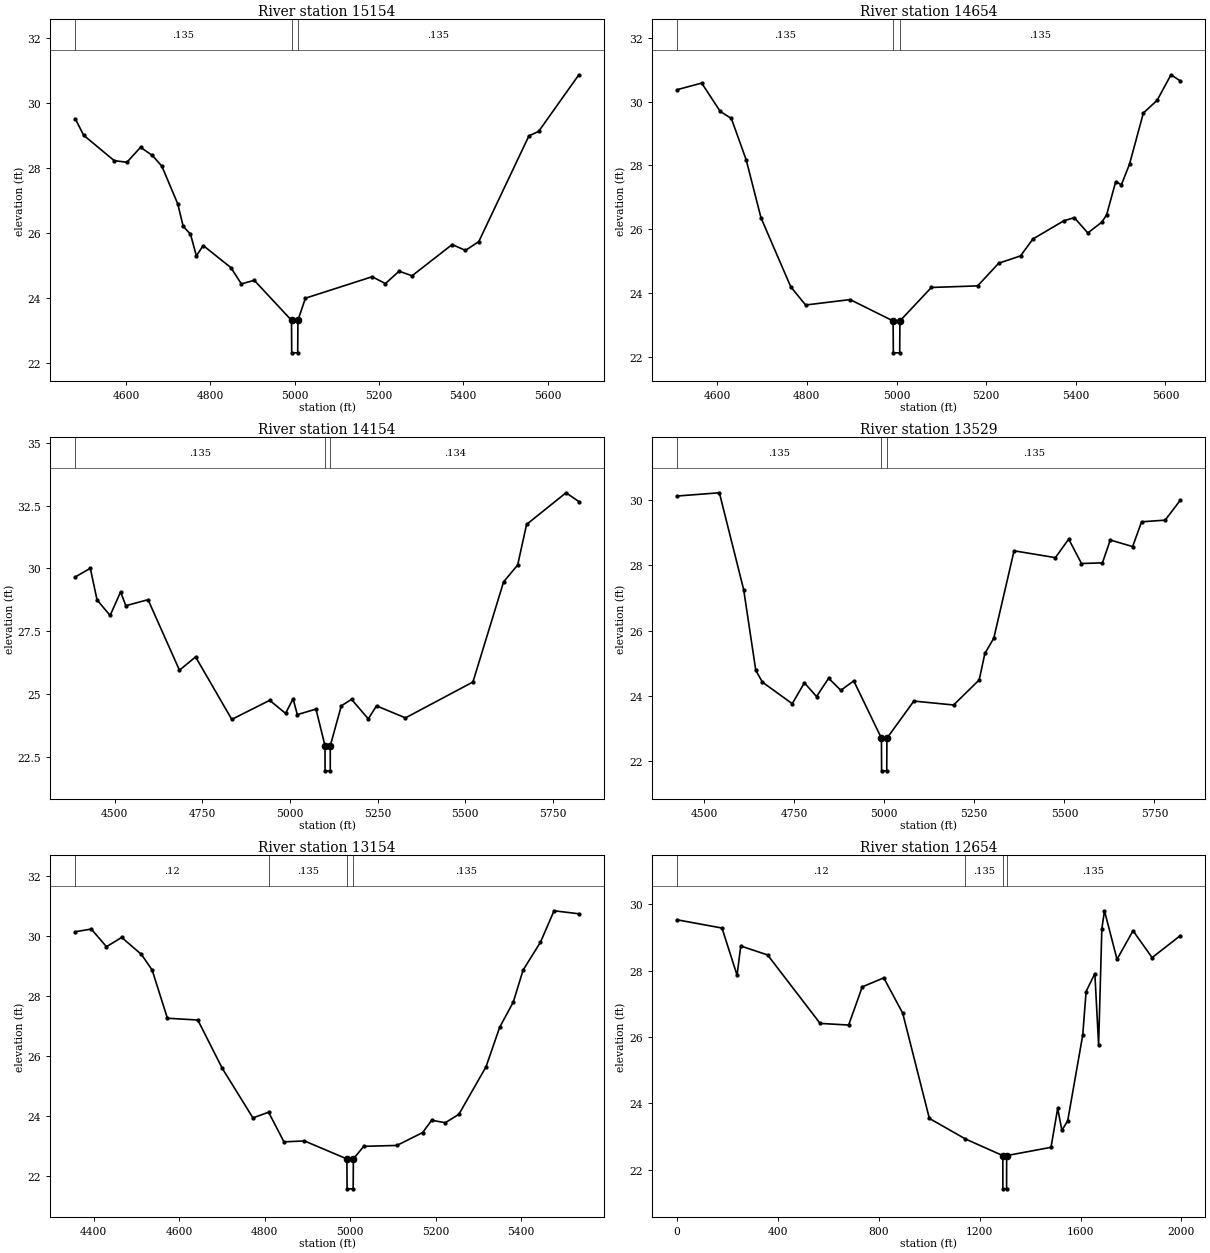
Type RM Length L Ch R = 1 ,15154   ,500,500,500
BEGIN DESCRIPTION:
Jenkins Swamp 22.0
END DESCRIPTION:
XS GIS Cut Line= 4
2565944.03501611 729868.48407552      2565943.58        729872.8
      2565889.48       730385.95      2565674.99       731025.02
#Sta/Elev= 30
 4479.66    29.5  4499.3      29  4571.7   28.22  4601.9   28.17  4634.2   28.63
  4662.2   28.38  4684.8   28.05  4722.5   26.89  4735.4    26.2  4752.7   25.96
  4766.7   25.29  4782.9   25.61  4848.6   24.93  4873.4   24.43    4904   24.54
  4992.4   23.31  4992.9   22.31  5007.1   22.31  5007.6   23.31  5025.4   23.99
  5183.6   24.65  5215.2   24.44  5247.6   24.82  5278.5   24.68  5373.5   25.64
  5405.1   25.46  5436.7   25.73  5555.6   28.98  5578.8   29.12  5674.1   30.86
#Mann= 3 ,-1,0
 4479.66    .135       0  4992.4     .05       0  5007.6    .135       0
Bank Sta=4992.4,5007.6
XS Rating Curve= 0 ,0
Exp/Cntr=0.3,0.1

Type RM Length L Ch R = 1 ,14654   ,500,500,500
BEGIN DESCRIPTION:
Jenkins Swamp 21.0
END DESCRIPTION:
XS GIS Cut Line= 3
       2565693.5       729789.75       2565485.9       730233.71
      2565342.62       730850.18
#Sta/Elev= 30
  4509.9   30.37  4565.4   30.58  4606.8   29.69  4631.6   29.47  4664.7   28.17
  4697.8   26.35  4764.1   24.19  4797.2   23.62  4896.5   23.79  4992.4   23.12
  4992.9   22.12  5007.1   22.12  5007.6   23.12  5077.7   24.17    5181   24.22
  5227.9   24.93  5276.7   25.16  5304.2   25.69  5373.1   26.26  5396.6   26.36
  5426.7   25.88  5458.2   26.22  5468.7   26.45    5489   27.49  5501.6   27.39
  5519.8   28.04  5550.6   29.64  5581.4   30.04  5612.2   30.84  5632.9   30.65
#Mann= 3 ,-1,0
  4509.9    .135       0  4992.4     .05       0  5007.6    .135       0
Bank Sta=4992.4,5007.6
XS Rating Curve= 0 ,0
Exp/Cntr=0.3,0.1

Type RM Length L Ch R = 1 ,14154   ,624,624,624
BEGIN DESCRIPTION:
Jenkins Swamp 20.0
END DESCRIPTION:
XS GIS Cut Line= 3
2565431.19962559729347.531461199      2565089.47       729977.31
        2564775.         730625.
#Sta/Elev= 30
  4387.4   29.66  4429.9      30  4449.2   28.74  4486.5   28.12  4516.4   29.06
  4531.3   28.51  4594.7   28.75  4684.3   25.94  4730.3   26.47  4833.6   23.98
  4941.8   24.74    4987   24.22  5008.5    24.8  5020.6   24.17  5073.8   24.39
  5099.6   22.93  5099.8   21.93  5114.6   21.93  5114.7   22.93  5146.1   24.52
  5175.3   24.78  5223.1      24  5246.6   24.52  5329.2   24.04  5521.7   25.47
  5609.2   29.46  5649.3   30.13  5674.8   31.75  5787.4   33.01  5823.9   32.66
#Mann= 3 ,-1,0
  4387.4    .135       0  5099.6     .05       0  5114.7    .134       0
Bank Sta=5099.6,5114.7
XS Rating Curve= 0 ,0
Exp/Cntr=0.3,0.1

Type RM Length L Ch R = 1 ,13529   ,376,376,376
BEGIN DESCRIPTION:
Jenkins Swamp 19.0
END DESCRIPTION:
XS GIS Cut Line= 3
      2564824.53       729134.82       2564562.4       729647.05
      2564123.88       730341.72
#Sta/Elev= 30
  4424.6   30.13  4542.7   30.23  4610.1   27.26  4643.8   24.78  4662.2   24.42
  4744.9   23.76  4778.6    24.4  4812.3   23.98  4845.9   24.54  4879.7   24.17
 4915.61   24.46  4992.4    22.7  4992.9    21.7  5007.1    21.7  5007.6    22.7
 5082.37   23.84  5192.7   23.72  5263.7   24.49  5279.4    25.3  5304.2   25.77
  5360.4   28.45  5475.1   28.24    5512   28.81  5547.5   28.06  5605.6   28.08
  5627.3   28.78  5689.4   28.58  5714.3   29.34  5779.6   29.39  5821.5      30
#Mann= 3 ,-1,0
  4424.6    .135       0  4992.4     .05       0  5007.6    .135       0
Bank Sta=4992.4,5007.6
XS Rating Curve= 0 ,0
Exp/Cntr=0.3,0.1

Type RM Length L Ch R = 1 ,13154   ,500,500,500
BEGIN DESCRIPTION:
Jenkins Swamp 18.0
END DESCRIPTION:
XS GIS Cut Line= 3
      2564573.44        728938.8       2564226.4       729479.99
       2564048.3       729984.69
#Sta/Elev= 30
  4357.1   30.15  4394.2   30.24  4429.8   29.65  4465.4   29.96  4511.7   29.39
  4536.7   28.87  4572.4   27.26  4643.6    27.2  4700.6   25.59  4772.5   23.93
  4809.2   24.12  4845.1   23.13  4893.1   23.16  4992.4   22.56  4992.9   21.56
  5007.1   21.56  5007.6   22.56  5031.8   22.98  5109.4   23.01  5169.6   23.44
  5190.9   23.85  5222.7   23.77  5254.5   24.05  5318.1   25.64    5350   26.96
  5381.8    27.8  5404.8   28.87  5445.4    29.8  5477.2   30.85  5535.2   30.75
#Mann= 4 ,-1,0
  4357.1     .12       0  4809.2    .135       0  4992.4     .05       0
  5007.6    .135       0
Bank Sta=4992.4,5007.6
XS Rating Curve= 0 ,0
Exp/Cntr=0.3,0.1

Type RM Length L Ch R = 1 ,12654   ,506.5,500,447.2
BEGIN DESCRIPTION:
Jenkins Swamp 17.0
END DESCRIPTION:
XS GIS Cut Line= 3
 2563420.1972294 728107.62728046      2563775.02       729357.84
      2563868.96       730047.07
#Sta/Elev= 30
       0   29.53   179.1   29.28   238.8   27.86   253.4   28.74   359.9   28.47
   567.9   26.41     681   26.36     735   27.51   820.2   27.78   895.2   26.72
  1000.9   23.55  1144.1   22.93    1292   22.43  1292.3   21.43    1307   21.43
  1307.2   22.43    1483   22.68  1509.5   23.85  1526.1   23.19  1549.2   23.48
  1608.8   26.06  1622.1   27.37  1656.8   27.91  1671.7   25.76  1684.5   29.26
  1694.9    29.8  1744.6   28.34  1808.2    29.2  1883.6   28.39  1995.2   29.05
#Mann= 4 ,-1,0
       0     .12       0  1144.1    .135       0    1292     .05       0
  1307.2    .135       0
Bank Sta=1292,1307.2
XS Rating Curve= 0 ,0
Exp/Cntr=0.3,0.1