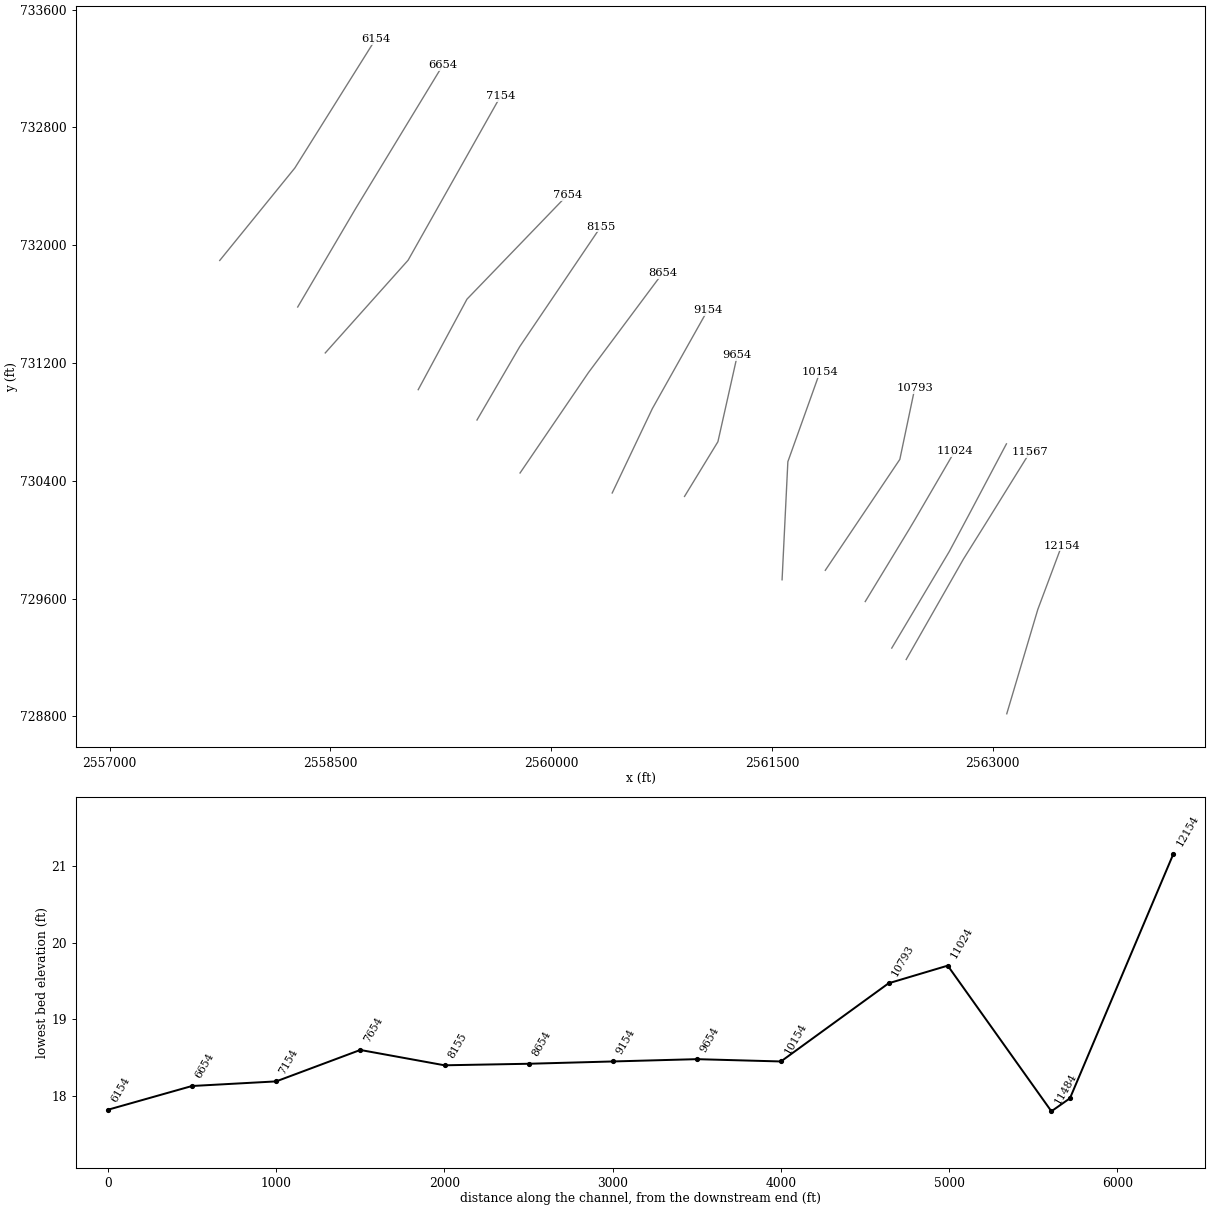
HEC-RAS study JenkinsSwamp.prj: S-26-134 over Jenkins Swamp

--- JenkinsSwamp.g04 (geometry) --- (continued)

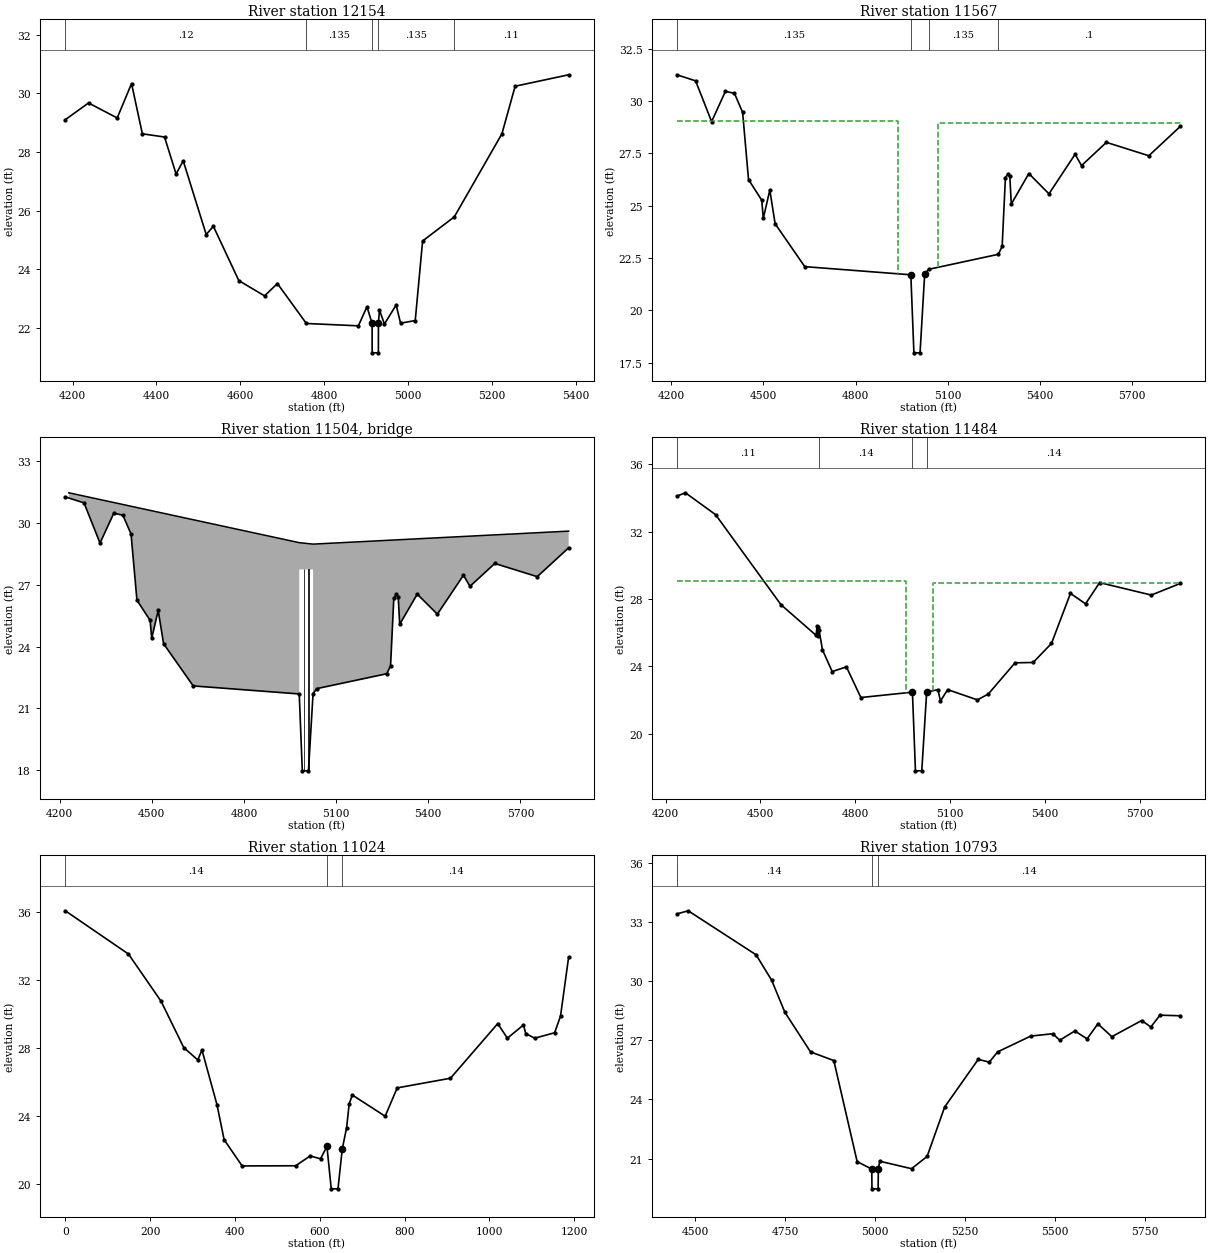
Type RM Length L Ch R = 1 ,12154   ,615,615,615
BEGIN DESCRIPTION:
Jenkins Swamp 16.0
END DESCRIPTION:
XS GIS Cut Line= 3
2563095.10002963728817.365649656      2563305.95       729525.83
2563467.58498439729957.612243324
#Sta/Elev= 30
 4182.54    29.1 4237.94   29.67 4306.34   29.16 4340.54   30.33 4366.34   28.62
 4419.24   28.51 4446.74   27.25 4463.74    27.7 4518.54   25.19 4535.64   25.47
 4596.34   23.62 4657.74    23.1 4688.34   23.52 4757.34   22.16 4881.34   22.08
 4901.84   22.73  4914.1   22.16  4914.2   21.16  4929.1   21.16  4929.2   22.16
 4931.64   22.62 4943.44   22.14 4971.44   22.79 4981.94   22.17 5016.94   22.26
 5034.54   24.97 5110.04   25.79 5223.64   28.62 5255.14   30.24 5382.74   30.63
#Mann= 5 ,-1,0
 4182.54     .12       0 4757.34    .135       0  4914.1     .05       0
  4929.2    .135       0 5110.04     .11       0
Bank Sta=4914.1,4929.2
XS Rating Curve= 0 ,0
Exp/Cntr=0.5,0.3

Type RM Length L Ch R = 1 ,11567   ,114.3,110.4,124.1
BEGIN DESCRIPTION:
Jenkins Swamp (SR-134) US
END DESCRIPTION:
XS GIS Cut Line= 4
      2562412.02       729186.12      2562800.34        729867.2
2562955.80631845730115.6700219832563253.24786549730594.875202905
#Sta/Elev= 30
  4218.3   31.26  4279.3   30.97  4331.4   29.02  4376.4   30.47  4405.9   30.37
  4432.4   29.46  4451.6   26.25  4494.5   25.27  4499.7    24.4  4520.9   25.75
  4538.2   24.14  4634.7   22.09    4980    21.7    4990   17.97    5010   17.97
    5025   21.72 5037.63   21.96  5264.9   22.68  5277.3   23.06  5287.9   26.34
  5295.9   26.53  5302.3    26.4    5307   25.08  5364.2   26.54  5429.7   25.57
  5514.7   27.46  5535.7   26.92  5616.7   28.03  5754.8   27.39  5857.1   28.79
#Mann= 4 ,-1,0
  4218.3    .135       0    4980     .05       0 5037.63    .135       0
  5264.9      .1       0
#XS Ineff= 2 , 0
            4937   29.04    5068           28.97
Permanent Ineff=
       F       F
Bank Sta=4980,5025
XS Rating Curve= 0 ,0
Exp/Cntr=0.5,0.3

Type RM Length L Ch R = 3 ,11504   ,,,
BEGIN DESCRIPTION:
Jenkins Swamp (SR-134) TOR
Structure ID: LDS_JKS_01
Approximate Survey Structure
END DESCRIPTION:
Bridge Culvert--1,0,-1,-1, 0
Deck Dist Width WeirC Skew NumUp NumDn MinLoCord MaxHiCord MaxSubmerge Is_Ogee
42.7675,28.2,3,0, 6, 6, , , 0.95, 0, 2,2,,
  4229.8    4980    4980    5025    5025  5857.1
   31.46   29.04   29.04   28.97   28.97    29.6
      .1      .1   27.74   27.74      .1      .1
  4229.8  4980.5  4980.5  5025.5  5025.5  5857.1
   31.46   29.04   29.04   28.97   28.97    29.6
      .1      .1   27.74   27.74      .1      .1
Pier Skew, UpSta & Num, DnSta & Num=  ,4995, 2 ,4995.5, 2 , 0 , 0 , 0 ,0,0
       1       1
    17.2   27.74
       1       1
   16.95   27.74
Pier Skew, UpSta & Num, DnSta & Num=  ,5010, 2 ,5010.5, 2 , 0 , 0 , 0 ,0,0
       1       1
    17.2   27.74
       1       1
   16.95   27.74
BR Coef=-1 ,-1 ,-1 ,0.9, 0 ,,,0.8,0,1.2,0,
WSPro=,,,, 1 ,,,, 0 ,,,, 0 ,,,,-1 ,-1 ,-1 , 0 , 0 , 0 , 0 , 0
BC Design=,, 0 ,, 0 ,,,,,,
BC HTab HWMax=31.67
BC Use User HTab Curves=0
BC User HTab FreeFlow(D)= 0

Type RM Length L Ch R = 1 ,11484   ,327.1,616.1,304.3
BEGIN DESCRIPTION:
Jenkins Swamp (SR-134) DS
END DESCRIPTION:
XS GIS Cut Line= 4
      2562313.94       729263.63      2562704.99       729920.09
2562836.13467104730165.6524739492563092.79790551730650.551768219
#Sta/Elev= 30
  4235.9    34.1  4262.8    34.3  4358.4      33  4564.9   27.66    4676   25.84
  4679.1    26.4  4682.5   25.81  4683.1   26.33  4685.3   26.16  4696.1   24.98
  4726.9   23.69  4771.8   23.97  4817.5   22.15  4980.5   22.47    4990    17.8
    5010    17.8  5025.5   22.47    5061   22.62  5069.1   21.94  5091.8   22.62
    5186   22.01  5220.4   22.36  5304.9   24.21    5362   24.23    5420   25.36
    5480   28.33  5527.6   27.71  5572.2   28.97  5735.5   28.23    5827   28.92
#Mann= 4 ,-1,0
  4235.9     .11       0  4685.3     .14       0  4980.5     .05       0
  5025.5     .14       0
#XS Ineff= 2 , 0
          4959.5   29.04  5046.5           28.97
Permanent Ineff=
       F       F
Bank Sta=4980.5,5025.5
XS Rating Curve= 0 ,0
Exp/Cntr=0.5,0.3

Type RM Length L Ch R = 1 ,11024   ,326.5,351.4,314.6
BEGIN DESCRIPTION:
Jenkins Swamp 14.0
END DESCRIPTION:
XS GIS Cut Line= 4
2562133.76558067729579.5977762082562432.23548892 730070.44556418
 2562472.0997569730137.5165138572562741.06228857730599.359913352
#Sta/Elev= 30
       0   36.09     149   33.54   225.8   30.76   279.5   28.02   312.4    27.3
   322.3   27.88   357.8   24.65   374.5    22.6     417   21.05   543.3   21.06
   577.4   21.64   601.8   21.47     617    22.2   627.1    19.7     643    19.7
   653.1   22.05   663.4   23.31  669.41   24.71   676.8   25.23   754.2   23.98
   782.6   25.65   908.3   26.22  1019.7   29.44  1042.4   28.58  1080.4   29.36
  1085.8   28.85    1107   28.58  1153.8    28.9  1167.7   29.88  1186.9   33.37
#Mann= 3 ,-1,0
       0     .14       0     617     .05       0   653.1     .14       0
Bank Sta=617,653.1
XS Rating Curve= 0 ,0
Exp/Cntr=0.3,0.1

Type RM Length L Ch R = 1 ,10793   ,640,640,640
BEGIN DESCRIPTION:
Jenkins Swamp 13.0
END DESCRIPTION:
XS GIS Cut Line= 4
      2561862.41       729791.79      2562169.99       730249.19
      2562368.63       730545.04      2562469.87       731026.97
#Sta/Elev= 30
  4448.8    33.4  4480.3   33.56  4669.1   31.33  4712.4   30.04  4749.1   28.42
  4820.5   26.41  4885.3   25.97  4950.2   20.85  4990.9   20.47  4991.4   19.47
  5008.6   19.47  5009.1   20.47    5013   20.87  5101.5   20.49  5144.7   21.11
  5193.7   23.62    5287   26.03  5317.7   25.89  5340.9   26.41  5432.9   27.21
  5494.3   27.33  5513.7      27  5555.6   27.47  5589.7   27.07  5619.7   27.83
  5658.5   27.18  5741.7      28    5767   27.67  5792.4   28.27  5848.8   28.24
#Mann= 3 ,-1,0
  4448.8     .14       0  4990.9     .05       0  5009.1     .14       0
Bank Sta=4990.9,5009.1
XS Rating Curve= 0 ,0
Exp/Cntr=0.3,0.1

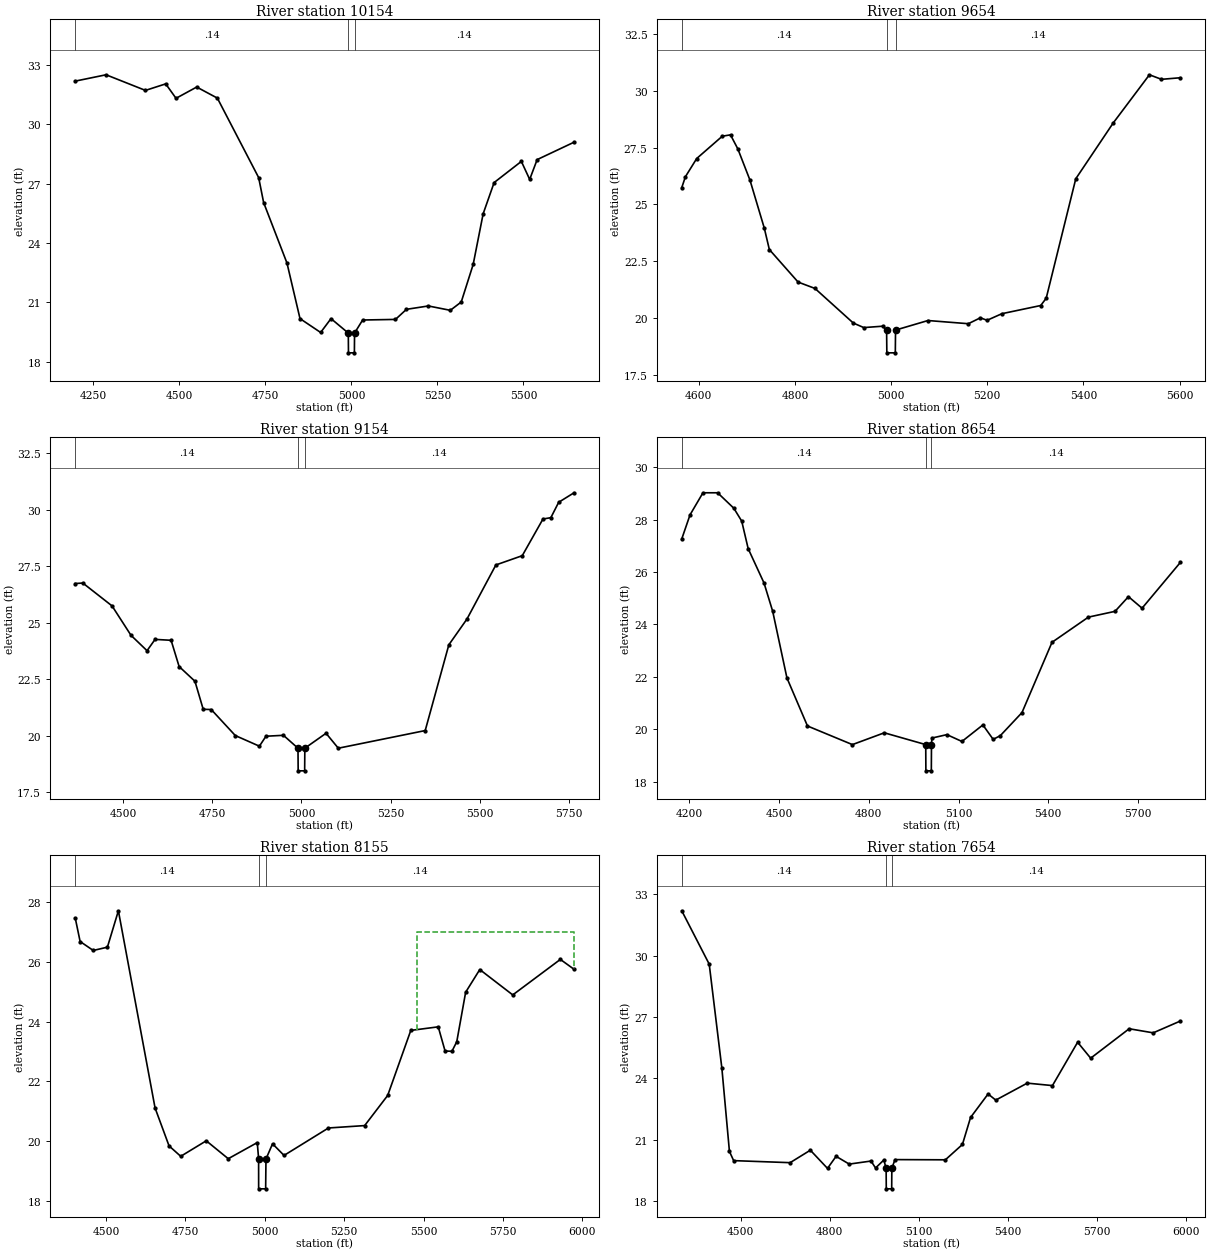
Type RM Length L Ch R = 1 ,10154   ,500,500,500
BEGIN DESCRIPTION:
Jenkins Swamp 12.0
END DESCRIPTION:
XS GIS Cut Line= 3
      2561568.81       729727.41      2561608.09       730529.35
      2561826.13       731138.72
#Sta/Elev= 30
  4197.1   32.19  4286.6   32.51  4401.1   31.72    4460   32.05    4490   31.32
  4550.1   31.89  4610.2   31.33  4730.3   27.31  4744.7   26.05  4812.6   22.99
  4850.5   20.18  4910.5   19.48  4940.6   20.18  4990.9   19.45  4991.4   18.45
  5008.6   18.45  5009.1   19.45  5032.6   20.11  5128.1   20.14    5160   20.65
  5223.7   20.82  5287.5    20.6  5319.3   21.02    5354   22.92    5383   25.48
  5414.9   27.06  5494.1   28.13  5518.3   27.22    5540   28.22  5647.2    29.1
#Mann= 3 ,-1,0
  4197.1     .14       0  4990.9     .05       0  5009.1     .14       0
Bank Sta=4990.9,5009.1
XS Rating Curve= 0 ,0
Exp/Cntr=0.3,0.1

Type RM Length L Ch R = 1 ,9654    ,500,500,500
BEGIN DESCRIPTION:
Jenkins Swamp 11.0
END DESCRIPTION:
XS GIS Cut Line= 3
      2560906.07       730293.49      2561132.95        730665.1
      2561264.72        731252.5
#Sta/Elev= 30
  4564.6   25.74  4572.2   26.22  4595.7   27.02  4648.9      28    4666   28.06
  4681.3   27.44  4706.5   26.07  4736.3   23.96  4746.8   23.02  4806.6   21.59
  4841.7   21.31  4921.4   19.79  4943.2   19.59  4982.3   19.65  4990.7   19.48
  4991.2   18.48  5008.8   18.48  5009.3   19.48  5076.8    19.9  5160.7   19.76
  5185.8   20.02  5199.7   19.91  5230.5    20.2  5311.3   20.56  5322.7   20.88
  5384.2   26.13    5462   28.58  5537.4    30.7  5562.5    30.5    5602   30.57
#Mann= 3 ,-1,0
  4564.6     .14       0  4990.7     .05       0  5009.3     .14       0
Bank Sta=4990.7,5009.3
XS Rating Curve= 0 ,0
Exp/Cntr=0.3,0.1

Type RM Length L Ch R = 1 ,9154    ,500,500,500
BEGIN DESCRIPTION:
Jenkins Swamp 10.0
END DESCRIPTION:
XS GIS Cut Line= 3
      2560414.85       730316.89      2560687.43       730889.74
      2561061.97       731556.56
#Sta/Elev= 30
  4365.6   26.73  4386.8   26.75  4468.7   25.74  4521.9   24.44  4566.9   23.76
  4589.4   24.26  4634.4   24.22  4656.9   23.06  4701.3   22.41  4724.5   21.17
    4747   21.16  4814.5   20.01  4882.1   19.54  4900.6   19.98  4949.6   20.02
  4990.4   19.45  4990.9   18.45  5009.1   18.45  5009.6   19.45  5069.1   20.11
  5103.5   19.45  5347.3   20.23  5413.6   24.02  5464.5   25.16  5545.6   27.55
  5619.6   27.96  5677.7   29.58  5699.8   29.64  5721.8   30.32  5764.8   30.74
#Mann= 3 ,-1,0
  4365.6     .14       0  4990.4     .05       0  5009.6     .14       0
Bank Sta=4990.4,5009.6
XS Rating Curve= 0 ,0
Exp/Cntr=0.3,0.1

Type RM Length L Ch R = 1 ,8654    ,472.9,499.3,503.2
BEGIN DESCRIPTION:
Jenkins Swamp 9.0
END DESCRIPTION:
XS GIS Cut Line= 3
      2559788.82        730452.7      2560253.39       731134.58
      2560756.75       731809.43
#Sta/Elev= 30
  4174.9   27.26  4202.6   28.18  4245.8   29.02  4294.8   29.02    4349   28.43
  4375.3   27.94  4396.9   26.89  4449.9   25.58  4478.9    24.5  4526.5   21.96
  4595.1   20.13  4745.3   19.42  4851.9   19.87  4990.4   19.42  4990.9   18.42
  5009.1   18.42  5009.6   19.42  5011.1   19.67  5061.2    19.8  5111.4   19.54
  5181.4   20.17  5215.8   19.62  5239.6   19.76  5312.1   20.64  5412.5   23.32
  5534.2   24.28  5623.1    24.5    5668   25.06  5713.5   24.62  5841.9   26.37
#Mann= 3 ,-1,0
  4174.9     .14       0  4990.4     .05       0  5009.6     .14       0
Bank Sta=4990.4,5009.6
XS Rating Curve= 0 ,0
Exp/Cntr=0.3,0.1

Type RM Length L Ch R = 1 ,8155    ,471,500.7,424.1
XS GIS Cut Line= 3
2559496.31472247730812.5897831962559786.75621856 731311.08609382
2560337.11977576732125.092174148
#Sta/Elev= 30
  4403.2   27.47  4418.4   26.69  4459.8   26.39  4504.3    26.5  4538.9   27.72
  4654.4   21.11  4698.4   19.84  4735.2   19.49  4815.6   20.01  4884.8   19.41
  4976.2   19.95  4980.4   19.41 4980.53    18.4 5002.57    18.4 5003.61    19.4
  5024.3   19.91  5060.5   19.52  5200.4   20.44  5314.3   20.52  5386.8   21.53
  5459.6   23.71    5546   23.83  5567.5   23.02  5589.1   23.01  5604.3   23.33
  5632.3   24.99  5676.8   25.75  5780.6    24.9  5930.5   26.09  5973.5   25.76
#Mann= 3 ,-1,0
  4403.2     .14       0  4980.4     .05       0 5003.61     .14       0
#XS Ineff= 2 , 0
                            5480              27
Permanent Ineff=
       F       F
Bank Sta=4980.4,5003.61
XS Rating Curve= 0 ,0
Exp/Cntr(USF)=0,0
Exp/Cntr=0.3,0.1

Type RM Length L Ch R = 1 ,7654    ,500,500,500
BEGIN DESCRIPTION:
Jenkins Swamp 7.0
END DESCRIPTION:
XS GIS Cut Line= 3
      2559097.11       731018.58       2559428.2       731633.17
      2560109.99       732339.92
#Sta/Elev= 30
  4301.9    32.2  4394.4   29.59  4437.1   24.49  4462.5   20.43  4476.7   19.98
    4667   19.88  4735.1   20.49  4792.9    19.6  4821.8   20.19  4866.1   19.81
  4939.6   19.96  4954.7   19.62  4982.7   20.01  4990.4    19.6  4990.9    18.6
  5009.1    18.6  5009.6    19.6  5020.2   20.03    5190   20.02  5247.4   20.77
  5274.8   22.09  5333.9   23.24  5359.7   22.94  5465.8   23.77  5550.7   23.65
  5635.5   25.77  5679.5   24.99  5809.2   26.43  5890.1   26.23    5982   26.81
#Mann= 3 ,-1,0
  4301.9     .14       0  4990.4     .05       0  5009.6     .14       0
Bank Sta=4990.4,5009.6
XS Rating Curve= 0 ,0
Exp/Cntr=0.3,0.1

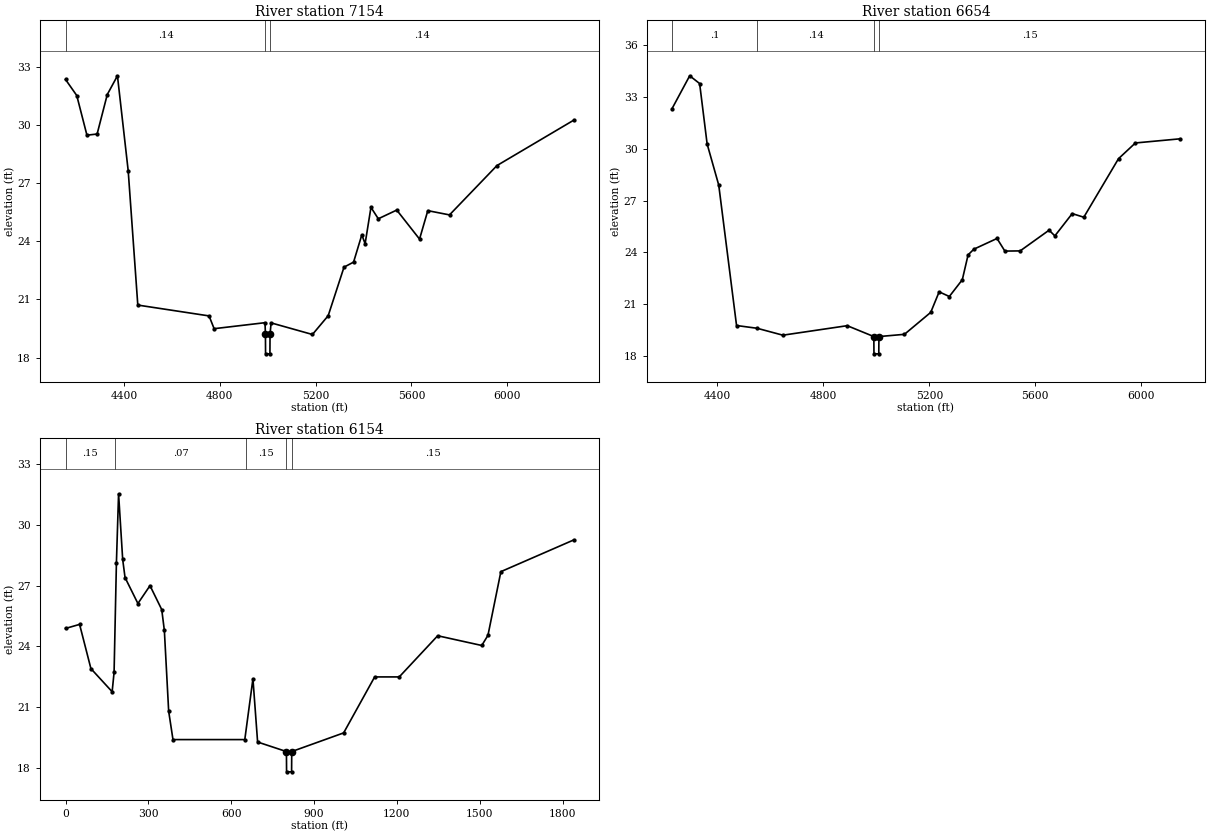
Type RM Length L Ch R = 1 ,7154    ,500,500,500
BEGIN DESCRIPTION:
Jenkins Swamp 6.0
END DESCRIPTION:
XS GIS Cut Line= 3
      2558465.56       731268.12      2559028.34       731897.77
      2559655.48       733010.17
#Sta/Elev= 30
  4155.5   32.37  4202.5   31.54    4245   29.49  4287.5   29.55  4329.9   31.59
  4372.4   32.56  4417.3   27.65  4457.4   20.71  4754.9   20.15  4776.1   19.49
  4988.6    19.8  4990.4   19.19  4990.9   18.19  5009.1   18.19  5009.6   19.19
    5014   19.79  5186.6   19.19  5252.4   20.16  5318.5   22.67  5358.4   22.93
  5392.9   24.34  5406.6   23.88    5431   25.76  5461.7   25.17  5538.7   25.62
  5633.9   24.12  5668.4   25.59    5759   25.37  5957.2   27.92    6277   30.26
#Mann= 3 ,-1,0
  4155.5     .14       0  4990.4     .05       0  5009.6     .14       0
Bank Sta=4990.4,5009.6
XS Rating Curve= 0 ,0
Exp/Cntr=0.3,0.1

Type RM Length L Ch R = 1 ,6654    ,500,500,500
BEGIN DESCRIPTION:
Jenkins Swamp 5.0
END DESCRIPTION:
XS GIS Cut Line= 3
      2558278.41       731579.98      2558669.65       732244.81
      2559265.11       733223.85
#Sta/Elev= 30
  4228.6   32.32  4295.5   34.23    4333   33.78  4361.3   30.28  4405.1    27.9
  4472.3   19.77    4550   19.61  4647.1   19.21    4890   19.76  4990.4   19.13
  4990.9   18.13  5009.1   18.13  5009.6   19.13  5105.9   19.26  5205.1   20.53
  5236.9   21.72  5275.3   21.45  5324.3   22.42  5346.1   23.86  5367.9   24.19
  5455.3   24.81  5484.9   24.08  5542.6   24.09  5651.8   25.29  5673.6   24.96
  5739.1   26.25  5782.8   26.04  5913.8   29.43  5977.5   30.34  6145.9   30.58
#Mann= 4 ,-1,0
  4228.6      .1       0    4550     .14       0  4990.4     .05       0
  5009.6     .15       0
Bank Sta=4990.4,5009.6
XS Rating Curve= 0 ,0
Exp/Cntr=0.3,0.1

Type RM Length L Ch R = 1 ,6154    ,500,500,500
BEGIN DESCRIPTION:
Jenkins Swamp 4.0
END DESCRIPTION:
XS GIS Cut Line= 3
      2557748.77       731896.08      2558259.27       732524.57
       2558806.4       733397.48
#Sta/Elev= 30
       0   24.89      51   25.09      92   22.91   168.9   21.77   175.9   22.72
   184.4   28.14   192.2   31.53   207.1   28.29   215.6    27.4   262.2   26.12
     306      27   348.5   25.82     358   24.79   373.6   20.81   389.2   19.41
   649.3   19.41   678.8   22.41   695.7   19.29800.1001   18.82800.6001   17.82
818.8003   17.82819.3003   18.82  1007.3   19.74  1119.6    22.5  1208.6    22.5
  1347.9   24.53  1507.5   24.05  1529.9   24.55  1576.7   27.69  1839.9   29.25
#Mann= 5 ,-1,0
       0     .15       0179.7002     .07       0654.7002     .15       0
800.1001     .05       0819.3003     .15       0
Bank Sta=800.1001,819.3003
XS Rating Curve= 0 ,0
Exp/Cntr=0.3,0.1