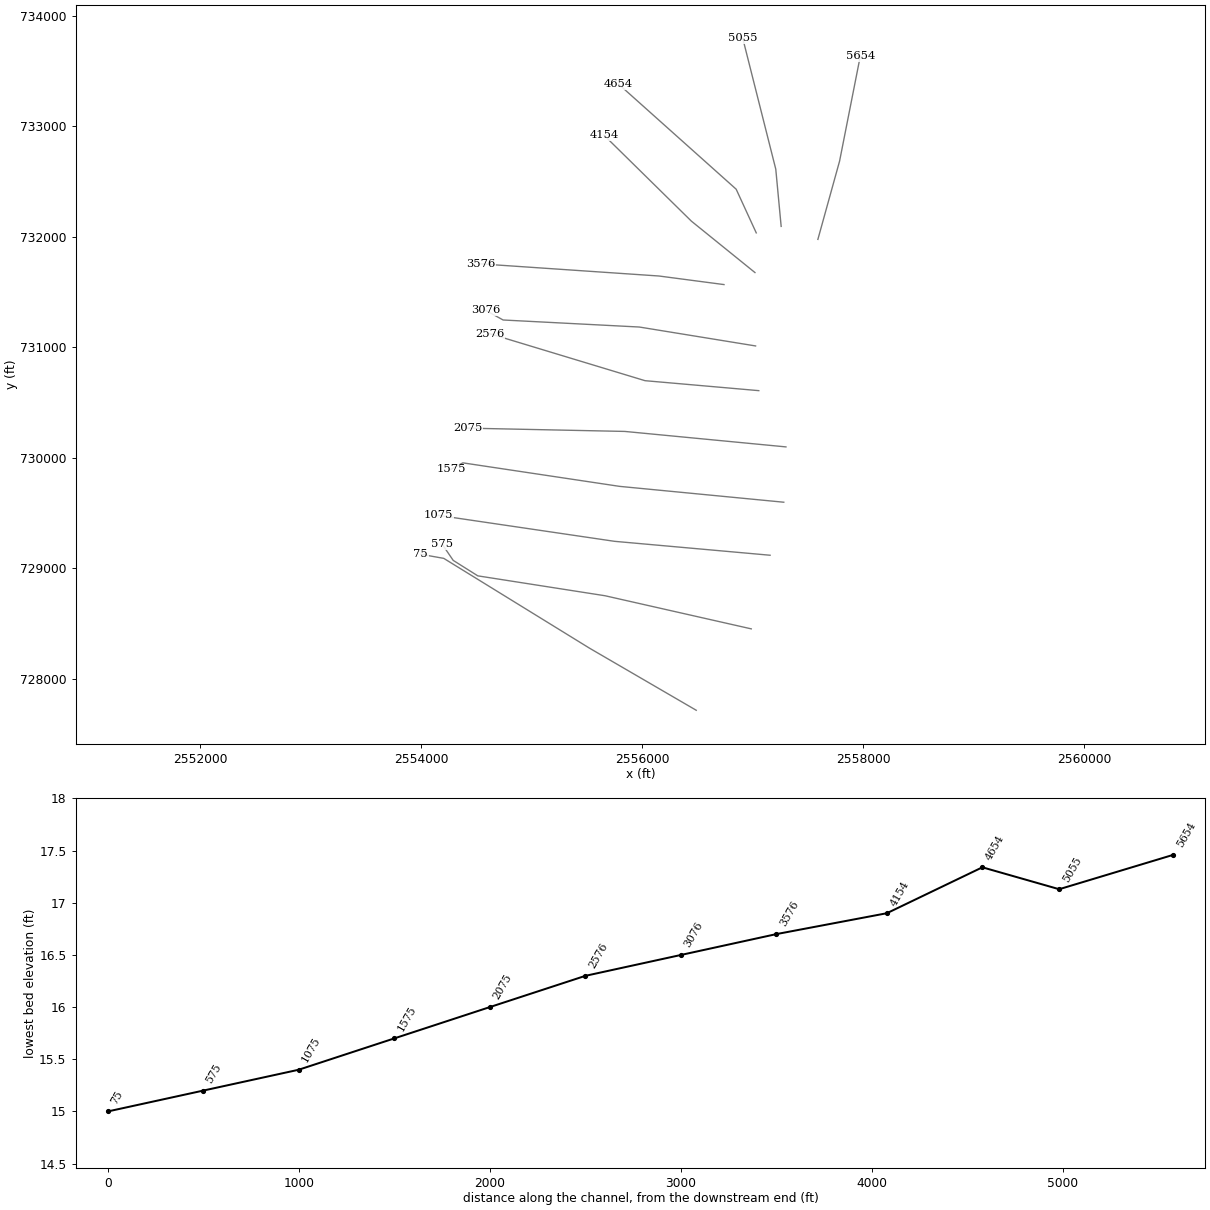
HEC-RAS study JenkinsSwamp.prj: S-26-134 over Jenkins Swamp

--- JenkinsSwamp.g04 (geometry) --- (continued)

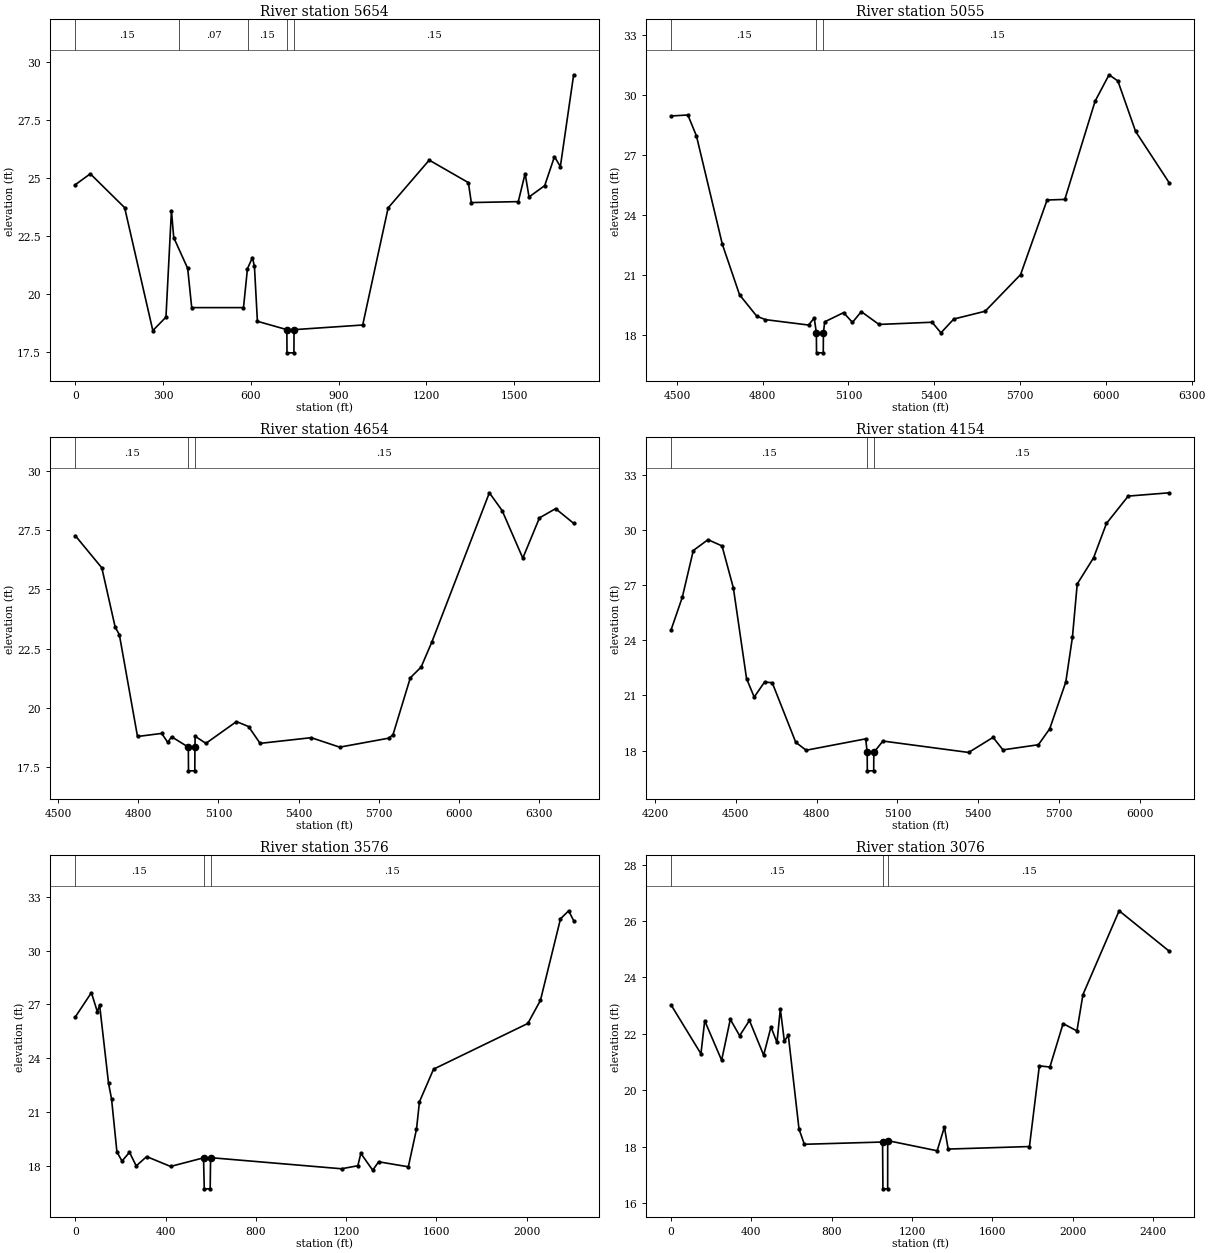
Type RM Length L Ch R = 1 ,5654    ,598,598,598
BEGIN DESCRIPTION:
Jenkins Swamp 3.0
END DESCRIPTION:
XS GIS Cut Line= 3
      2557589.24       731974.08      2557785.69       732682.65
      2557972.97       733632.05
#Sta/Elev= 30
       0   24.71    51.4   25.18   168.7   23.72     265   18.42   309.9      19
   328.6   23.59   336.5   22.43   384.1    21.1   397.9   19.41   574.8   19.41
   588.4   21.09   605.4   21.57   612.2   21.19   622.4   18.82     723   18.46
   723.5   17.46747.0996   17.46747.5996   18.46   982.2   18.66  1069.1   23.71
  1209.5   25.77  1343.3    24.8  1353.3   23.94  1513.8   23.98  1537.2   25.19
  1550.6   24.18  1604.1   24.67  1637.5   25.92  1657.6   25.49    1703   29.45
#Mann= 5 ,-1,0
       0     .15       0355.2998     .07       0590.2998     .15       0
     723     .05       0747.5996     .15       0
Bank Sta=723,747.5996
XS Rating Curve= 0 ,0
Exp/Cntr=0.3,0.1

Type RM Length L Ch R = 1 ,5055    ,402,402,402
BEGIN DESCRIPTION:
Jenkins Swamp 2.0
END DESCRIPTION:
XS GIS Cut Line= 3
      2557256.91       732091.65      2557208.17       732609.66
      2556909.05        733794.9
#Sta/Elev= 30
  4479.7   28.97  4538.3   29.02  4568.4   27.97  4658.8   22.56  4719.1   20.03
  4779.4   18.96  4809.5   18.79  4960.2   18.52  4980.2   18.87  4987.7   18.13
  4988.2   17.13  5011.8   17.13  5012.3   18.13  5016.8   18.68  5082.9   19.14
  5113.8   18.65  5144.7   19.19  5206.6   18.55  5392.3   18.66  5423.2   18.13
  5468.2   18.82  5577.9   19.21  5701.7   21.04  5794.5   24.77  5856.4    24.8
  5962.3   29.71  6011.1   31.03    6042   30.72  6103.9    28.2  6222.4   25.61
#Mann= 3 ,-1,0
  4479.7     .15       0  4987.7     .05       0  5012.3     .15       0
Bank Sta=4987.7,5012.3
XS Rating Curve= 0 ,0
Exp/Cntr=0.3,0.1

Type RM Length L Ch R = 1 ,4654    ,500,500,500
BEGIN DESCRIPTION:
Jenkins Swamp 1.0
END DESCRIPTION:
XS GIS Cut Line= 3
       2557031.5       732032.91      2556849.74       732428.22
      2555784.73       733379.96
#Sta/Elev= 30
  4564.9   27.27  4664.2   25.91    4714   23.41  4729.7   23.09  4797.6   18.79
    4888   18.92  4910.7   18.54  4924.9   18.78  4987.7   18.34  4988.2   17.34
  5011.8   17.34  5012.3   18.34  5013.1    18.8  5053.3    18.5  5167.7   19.42
  5212.8   19.21    5256    18.5  5447.2   18.74  5553.5   18.34  5737.3   18.72
    5753   18.87  5817.7   21.27    5858   21.72  5898.2   22.78  6113.2   29.08
  6160.9   28.33  6238.2   26.32  6300.5   28.02  6360.9   28.41  6428.3   27.79
#Mann= 3 ,-1,0
  4564.9     .15       0  4987.7     .05       0  5012.3     .15       0
Bank Sta=4987.7,5012.3
XS Rating Curve= 0 ,0
Exp/Cntr=0.3,0.1

Type RM Length L Ch R = 1 ,4154    ,577.9,577.9,577.9
BEGIN DESCRIPTION:
Jenkins Swamp 0.0
END DESCRIPTION:
XS GIS Cut Line= 3
      2557019.79       731673.95      2556444.28       732139.28
      2555653.21       732917.37
#Sta/Elev= 30
  4259.9   24.57  4301.3   26.33  4342.3   28.88  4396.8   29.47  4448.9   29.13
  4491.1   26.84  4539.9   21.92  4568.3   20.91  4606.8   21.73  4635.3   21.69
  4722.6   18.45  4761.2   18.02  4982.2   18.64  4987.7    17.9  4988.2    16.9
  5011.8    16.9  5012.3    17.9    5046   18.52  5364.2    17.9  5454.9   18.72
  5491.5   18.04  5623.2   18.32  5665.2   19.19  5724.8   21.73  5749.4   24.16
  5767.2   27.06  5828.1   28.49  5875.6   30.35  5956.5   31.84  6109.6   32.02
#Mann= 3 ,-1,0
  4259.9     .15       0  4987.7     .05       0  5012.3     .15       0
#XS Ineff= 2 , 0
          4606.8   21.73
Permanent Ineff=
       F       F
Bank Sta=4987.7,5012.3
XS Rating Curve= 0 ,0
Exp/Cntr=0.3,0.1

Type RM Length L Ch R = 1 ,3576    ,499.8,499.8,499.8
XS GIS Cut Line= 3
2556739.68503593731565.0851722642556150.67666649731642.726698669
2554540.90625435731752.216178577
#Sta/Elev= 30
       0   26.29    71.4   27.65    97.8   26.58   107.8   26.96   147.5   22.58
   160.7   21.72   184.5   18.76     207   18.25   240.2   18.74   269.9   17.98
   316.2    18.5   422.1   17.95  568.14   18.43  571.39    16.7  597.59    16.7
  599.42   18.44  1179.4   17.82  1251.7   17.99  1264.9   18.68  1317.5   17.74
  1343.8   18.21  1475.3   17.93  1511.5   20.03  1524.6   21.56  1587.1   23.38
  2004.6   25.93  2060.5   27.22  2149.3   31.77  2185.5   32.222207.593   31.67
#Mann= 3 ,0,0
       0     .15       0  568.14     .05       0  599.42     .15       0
Bank Sta=568.14,599.42
XS Rating Curve= 0 ,0
Exp/Cntr(USF)=0,0
Exp/Cntr=0.3,0.1

Type RM Length L Ch R = 1 ,3076    ,500,500,500
XS GIS Cut Line= 4
2557025.56629845731009.7215136762555973.09854723731180.958933814
 2554740.6429284731244.605850191 2554580.9809528731332.667929342
#Sta/Elev= 30
       0   23.02   148.6   21.29   167.4   22.46   251.7   21.06   294.9   22.51
   341.4   21.93   390.3   22.47     461   21.24   497.6   22.24   527.5   21.69
   544.1   22.88   564.1   21.74     584   21.94   637.2   18.62   663.8   18.08
  1053.5   18.16 1055.27    16.5 1078.89    16.5    1079   18.21  1325.4   17.85
  1361.5   18.69  1380.2   17.91  1785.2      18  1834.5   20.86  1887.1   20.82
  1952.8   22.36  2021.7    22.1  2051.8   23.39    2232   26.362482.742   24.92
#Mann= 3 ,-1,0
       0     .15       0  1053.5     .05       0    1079     .15       0
Bank Sta=1053.5,1079
XS Rating Curve= 0 ,0
Exp/Cntr(USF)=0,0
Exp/Cntr=0.3,0.1

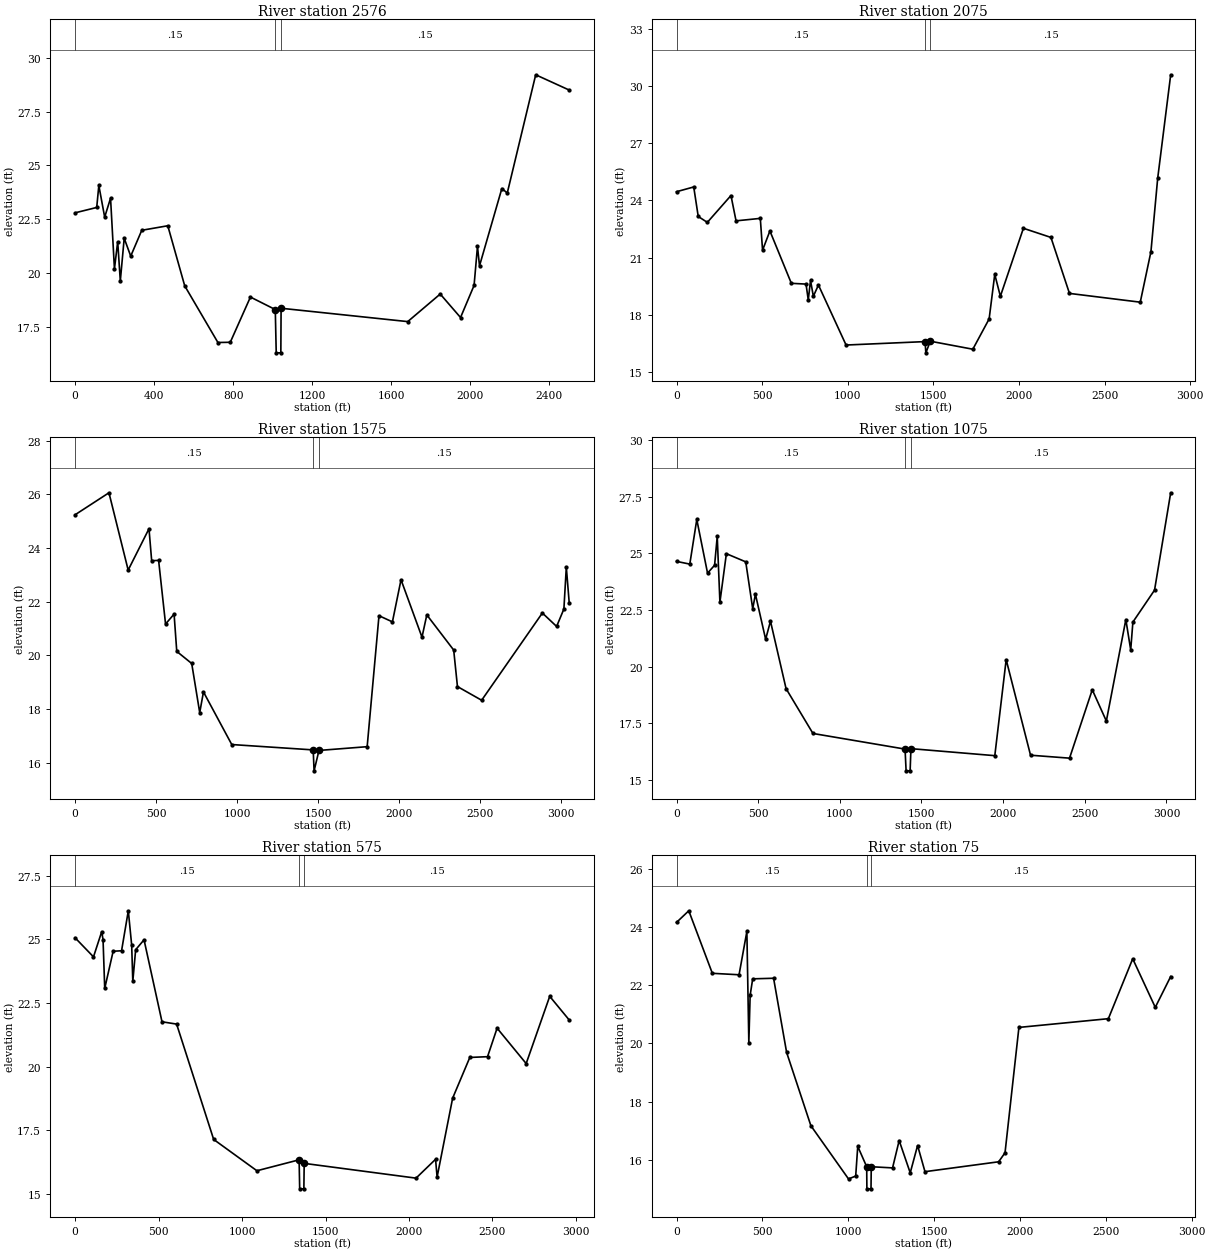
Type RM Length L Ch R = 1 ,2576    ,501,501,501
XS GIS Cut Line= 3
2557054.47442401730605.1635051362556025.01241033730695.342794545
2554620.34546111731120.481101162
#Sta/Elev= 30
       0    22.8   109.6   23.05   120.3   24.07   149.9    22.6   179.6   23.48
   199.3    20.2   215.8   21.46     229   19.64   248.7   21.62   281.7   20.79
   337.6   21.99   469.3    22.2     555   19.41   722.9   16.78   785.5   16.79
   887.5   18.89  1013.3   18.31 1018.07    16.3 1041.46    16.3  1042.7   18.37
  1683.6   17.75  1848.1   19.03  1950.9   17.94  2019.4   19.43  2036.6   21.24
  2046.9   20.34    2160   23.93  2187.4   23.72  2331.3   29.212500.998    28.5
#Mann= 3 ,-1,0
       0     .15       0  1013.3     .05       0  1042.7     .15       0
Bank Sta=1013.3,1042.7
XS Rating Curve= 0 ,0
Exp/Cntr(USF)=0,0
Exp/Cntr=0.3,0.1

Type RM Length L Ch R = 1 ,2075    ,500,500,500
XS GIS Cut Line= 3
2557300.35784583 730096.133109882555841.52050934 730236.15497734
2554421.35983252730265.804901756
#Sta/Elev= 30
       0   24.46   100.5   24.71   126.8   23.16   179.9   22.85     318   24.26
   347.6   22.93   489.3   23.06   502.5   21.39   545.4    22.4   670.6   19.65
   756.3   19.61   769.4   18.78   782.6    19.8   799.1   18.97   828.8   19.56
   990.2   16.41  1451.6   16.59 1456.08      16 1482.24   16.61  1730.5   16.19
  1825.7   17.78  1858.5   20.12  1891.3   18.97  2025.8   22.54  2186.6   22.06
  2294.9   19.12  2708.3   18.66  2770.6   21.31    2810   25.162886.012    30.6
#Mann= 3 ,-1,0
       0     .15       0  1451.6     .05       0 1482.24     .15       0
Bank Sta=1451.6,1482.24
XS Rating Curve= 0 ,0
Exp/Cntr(USF)=0,0
Exp/Cntr=0.3,0.1

Type RM Length L Ch R = 1 ,1575    ,499.8,499.8,499.8
XS GIS Cut Line= 4
2557280.61495061729595.4593735282555794.94080733729738.917471225
2554376.11716265729951.847054484 2554268.3603662729892.855441721
#Sta/Elev= 30
       0   25.24   209.2   26.06   327.8   23.18   456.3   24.72   472.8   23.53
   515.7   23.54   558.5   21.17   611.2   21.54   627.7   20.15     720    19.7
   769.4   17.87   792.5   18.64   967.2   16.68 1469.77   16.48 1475.31    15.7
 1505.42   16.46  1802.9    16.6  1875.9   21.48  1958.8   21.25  2011.9   22.82
  2141.3   20.68  2171.1   21.51    2337    20.2  2360.2   18.84  2509.5   18.33
  2884.3   21.58  2972.3   21.08  3017.2   21.73  3032.1   23.293050.144   21.95
#Mann= 3 ,-1,0
       0     .15       0 1469.77     .05       0 1505.42     .15       0
Bank Sta=1469.77,1505.42
XS Rating Curve= 0 ,0
Exp/Cntr(USF)=0,0
Exp/Cntr=0.3,0.1

Type RM Length L Ch R = 1 ,1075    ,500,500,500
XS GIS Cut Line= 3
 2557156.6779397729115.6564380572555749.64832934729241.531911907
2554153.49920101729476.678947924
#Sta/Elev= 30
       0   24.65    81.3   24.53   124.1    26.5     190   24.13   233.1   24.48
   249.3   25.75   265.7   22.85   305.3   24.99   423.8   24.63   466.6   22.56
   483.1    23.2   545.7   21.21   575.3   22.01   670.8   19.03   835.5   17.05
 1399.39   16.36 1405.82    15.4 1430.49    15.4 1435.42   16.38    1949   16.07
  2018.6   20.31  2167.8   16.09  2406.6   15.96  2545.8   18.98    2632    17.6
  2751.4   22.08  2781.2   20.74  2794.5   21.97  2927.1   23.383026.026   27.68
#Mann= 3 ,-1,0
       0     .15       0 1399.39     .05       0 1435.42     .15       0
Bank Sta=1399.39,1435.42
XS Rating Curve= 0 ,0
Exp/Cntr(USF)=0,0
Exp/Cntr=0.3,0.1

Type RM Length L Ch R = 1 ,575     ,499.8,499.8,499.8
XS GIS Cut Line= 5
2556986.51786171 728449.325138752555663.24220042728749.069766777
2554511.49411288728929.1325313572554288.77010278729069.231253435
2554190.74657671729212.989203991
#Sta/Elev= 30
       0   25.06   110.4   24.31   159.6    25.3   167.6   24.99   177.6   23.07
   228.1   24.53   278.5   24.55   318.9   26.12   339.1   24.77   345.8   23.35
   362.9   24.59   413.1   24.98   520.7   21.76   608.2   21.67   830.1   17.14
  1089.1   15.91  1341.9   16.34 1345.27    15.2 1370.31    15.2 1372.31    16.2
  2042.1   15.62  2159.1   16.36  2168.3   15.66  2261.3   18.76  2364.2   20.36
  2470.4   20.39  2527.6   21.51  2701.8   20.12  2842.8   22.762959.658   21.83
#Mann= 3 ,-1,0
       0     .15       0  1341.9     .05       0 1372.31     .15       0
Bank Sta=1341.9,1372.31
XS Rating Curve= 0 ,0
Exp/Cntr(USF)=0,0
Exp/Cntr=0.3,0.1

Type RM Length L Ch R = 1 ,75      ,,,
XS GIS Cut Line= 4
2556488.36668207727712.6384557512555522.93973002728274.293769369
2554203.18402074 729087.443169382553995.62639705729124.310912642
#Sta/Elev= 30
       0   24.16    71.4   24.56   208.6   22.41   364.2   22.36   409.7   23.85
   421.1   20.02   428.7   21.65   443.6   22.22   565.3   22.24   641.2   19.69
   782.5   17.17  1001.7   15.34  1043.5   15.44  1055.4   16.46 1107.45   15.76
 1108.66      15  1132.6      15 1134.08   15.76  1258.1   15.72  1296.6   16.66
    1361   15.55  1403.9   16.49  1446.9   15.59  1875.9   15.93  1913.1   16.24
    1994   20.55  2514.9   20.85  2656.7   22.91  2788.1   21.242877.875    22.3
#Mann= 3 ,-1,0
       0     .15       0 1108.66     .05       0 1134.08     .15       0
Bank Sta=1107.45,1134.08
XS Rating Curve= 0 ,0
Exp/Cntr(USF)=0,0
Exp/Cntr=0.3,0.1
LCMann Table=0

Chan Stop Cuts=-1
Use User Specified Reach Order=0
Composite Channel Slope=5

--- JenkinsSwamp.g02 (geometry) ---

Geom Title=Proposed
Program Version=6.60

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
River Reach=Jenkins Swamp   ,Reach-1

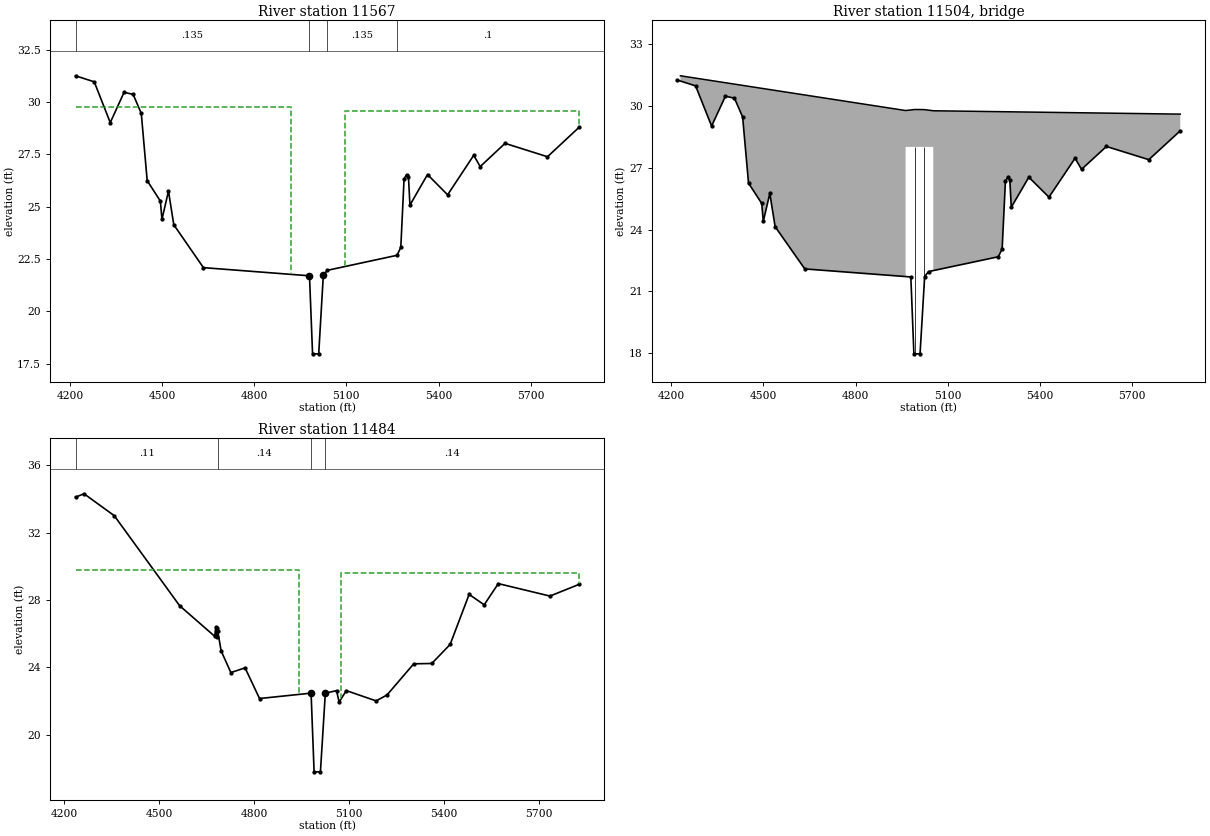
Type RM Length L Ch R = 1 ,11567   ,114.3,110.4,124.1
BEGIN DESCRIPTION:
Jenkins Swamp (SR-134) US
END DESCRIPTION:
XS GIS Cut Line= 4
      2562412.02       729186.12      2562800.34        729867.2
2562955.80631845730115.6700219832563253.24786549730594.875202905
#Sta/Elev= 30
  4218.3   31.26  4279.3   30.97  4331.4   29.02  4376.4   30.47  4405.9   30.37
  4432.4   29.46  4451.6   26.25  4494.5   25.27  4499.7    24.4  4520.9   25.75
  4538.2   24.14  4634.7   22.09    4980    21.7    4990   17.97    5010   17.97
    5025   21.72 5037.63   21.96  5264.9   22.68  5277.3   23.06  5287.9   26.34
  5295.9   26.53  5302.3    26.4    5307   25.08  5364.2   26.54  5429.7   25.57
  5514.7   27.46  5535.7   26.92  5616.7   28.03  5754.8   27.39  5857.1   28.79
#Mann= 4 ,-1,0
  4218.3    .135       0    4980     .05       0 5037.63    .135       0
  5264.9      .1       0
#XS Ineff= 2 , 0
       0    4920  29.774    5096       0    29.6
Permanent Ineff=
       F       F
Bank Sta=4980,5025
XS Rating Curve= 0 ,0
Exp/Cntr=0.5,0.3

Type RM Length L Ch R = 3 ,11504   ,,,
BEGIN DESCRIPTION:
Jenkins Swamp S-26-134
END DESCRIPTION:
Bridge Culvert--1,0,-1,-1, 0
Deck Dist Width WeirC Skew NumUp NumDn MinLoCord MaxHiCord MaxSubmerge Is_Ogee
42.7675,42.25,3,0, 8, 8, , , 0.95, 0, 2,2,,
  4229.8    4963    4963    4993    5023    5053    5053  5857.1
   31.46  29.774  29.774  29.824   29.82  29.763  29.763    29.6
      .1      .1   28.01   28.01   28.01   28.01      .1      .1
  4229.8  4963.5  4963.5  4993.5  5023.5  5053.5  5053.5  5857.1
   31.46  29.774  29.774  29.824   29.82  29.763  29.763    29.6
      .1      .1   28.01   28.01   28.01   28.01      .1      .1
Pier Skew, UpSta & Num, DnSta & Num=  ,4993, 2 ,4993.5, 2 , 0 , 0 , 0 ,0,0
       2       2
    17.2   28.01
       2       2
   16.95   28.01
Pier Skew, UpSta & Num, DnSta & Num=  ,5023, 2 ,5023.5, 2 , 0 , 0 , 0 ,0,0
       2       2
    17.2   28.01
       2       2
   16.95   28.01
Abutment Skew #Up #Dn= , 3 , 3
    4963    4965  4973.6
   26.01   26.01    21.7
  4963.5  4965.5  4974.1
   26.01   26.01    21.7
Abutment Skew #Up #Dn= , 3 , 3
 5042.92    5051    5053
   21.96   26.01   26.01
 5043.42  5051.5  5053.5
   21.96   26.01   26.01
BR Coef=-1 ,-1 ,-1 ,1.25, 0 ,,,0.8,0,2,0,
WSPro=,,,, 1 ,,,, 0 ,,,, 0 ,,,,-1 ,-1 ,-1 , 0 , 0 , 0 , 0 , 0
BC Design=,, 0 ,, 0 ,,,,,,
BC HTab HWMax=31.67
BC Use User HTab Curves=0
BC User HTab FreeFlow(D)= 0

Type RM Length L Ch R = 1 ,11484   ,327.1,616.1,304.3
BEGIN DESCRIPTION:
Jenkins Swamp (SR-134) DS
END DESCRIPTION:
XS GIS Cut Line= 4
      2562313.94       729263.63      2562704.99       729920.09
2562836.13467104730165.6524739492563092.79790551730650.551768219
#Sta/Elev= 30
  4235.9    34.1  4262.8    34.3  4358.4      33  4564.9   27.66    4676   25.84
  4679.1    26.4  4682.5   25.81  4683.1   26.33  4685.3   26.16  4696.1   24.98
  4726.9   23.69  4771.8   23.97  4817.5   22.15  4980.5   22.47    4990    17.8
    5010    17.8  5025.5   22.47    5061   22.62  5069.1   21.94  5091.8   22.62
    5186   22.01  5220.4   22.36  5304.9   24.21    5362   24.23    5420   25.36
    5480   28.33  5527.6   27.71  5572.2   28.97  5735.5   28.23    5827   28.92
#Mann= 4 ,-1,0
  4235.9     .11       0  4685.3     .14       0  4980.5     .05       0
  5025.5     .14       0
#XS Ineff= 2 , 0
       0  4942.5  29.774  5074.5       0    29.6
Permanent Ineff=
       F       F
Bank Sta=4980.5,5025.5
XS Rating Curve= 0 ,0
Exp/Cntr=0.5,0.3

--- JenkinsSwamp.g03 (geometry) ---

Geom Title=Natural
Program Version=6.60

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
River Reach=Jenkins Swamp   ,Reach-1

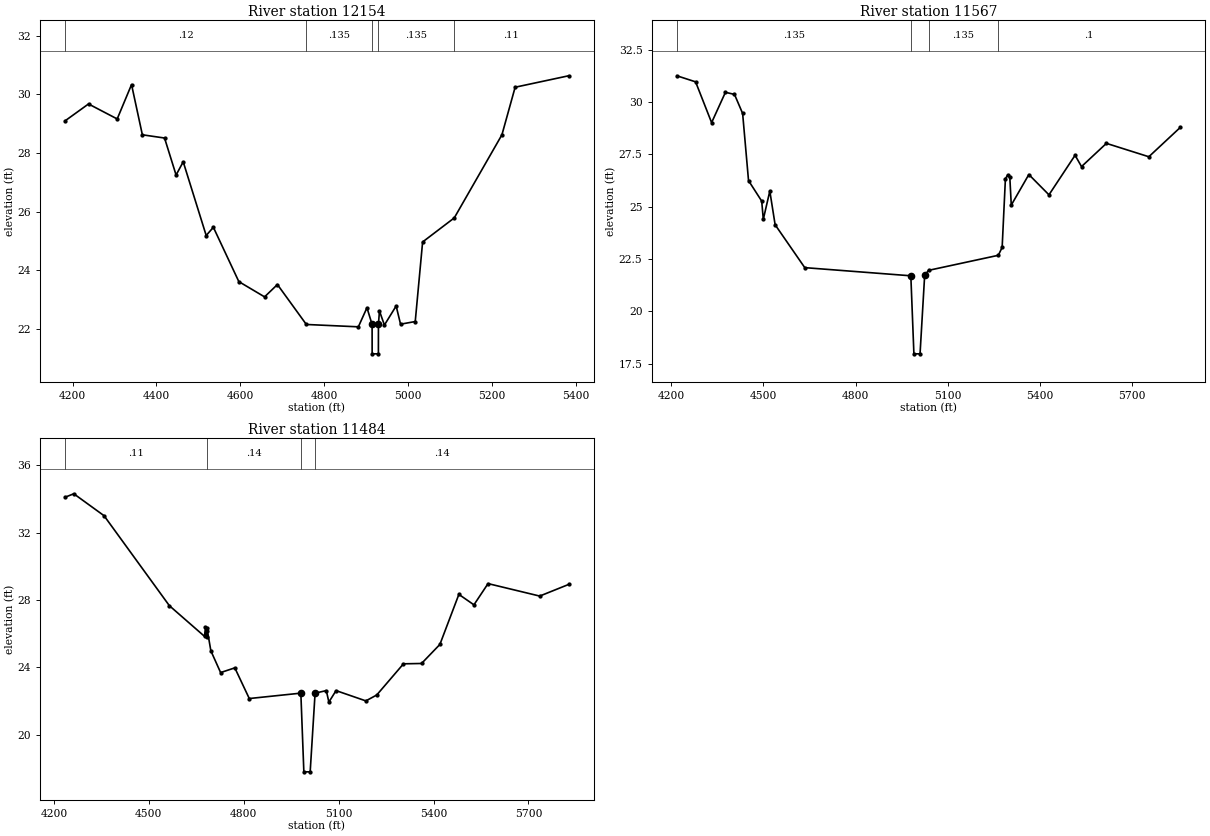
Type RM Length L Ch R = 1 ,12154   ,615,615,615
BEGIN DESCRIPTION:
Jenkins Swamp 16.0
END DESCRIPTION:
XS GIS Cut Line= 3
2563095.10002963728817.365649656      2563305.95       729525.83
2563467.58498439729957.612243324
#Sta/Elev= 30
 4182.54    29.1 4237.94   29.67 4306.34   29.16 4340.54   30.33 4366.34   28.62
 4419.24   28.51 4446.74   27.25 4463.74    27.7 4518.54   25.19 4535.64   25.47
 4596.34   23.62 4657.74    23.1 4688.34   23.52 4757.34   22.16 4881.34   22.08
 4901.84   22.73  4914.1   22.16  4914.2   21.16  4929.1   21.16  4929.2   22.16
 4931.64   22.62 4943.44   22.14 4971.44   22.79 4981.94   22.17 5016.94   22.26
 5034.54   24.97 5110.04   25.79 5223.64   28.62 5255.14   30.24 5382.74   30.63
#Mann= 5 ,-1,0
 4182.54     .12       0 4757.34    .135       0  4914.1     .05       0
  4929.2    .135       0 5110.04     .11       0
Bank Sta=4914.1,4929.2
XS Rating Curve= 0 ,0
Exp/Cntr=0.3,0.1

Type RM Length L Ch R = 1 ,11567   ,114.3,110.4,124.1
BEGIN DESCRIPTION:
Jenkins Swamp (SR-134) US
END DESCRIPTION:
XS GIS Cut Line= 4
      2562412.02       729186.12      2562800.34        729867.2
2562955.80631845730115.6700219832563253.24786549730594.875202905
#Sta/Elev= 30
  4218.3   31.26  4279.3   30.97  4331.4   29.02  4376.4   30.47  4405.9   30.37
  4432.4   29.46  4451.6   26.25  4494.5   25.27  4499.7    24.4  4520.9   25.75
  4538.2   24.14  4634.7   22.09    4980    21.7    4990   17.97    5010   17.97
    5025   21.72 5037.63   21.96  5264.9   22.68  5277.3   23.06  5287.9   26.34
  5295.9   26.53  5302.3    26.4    5307   25.08  5364.2   26.54  5429.7   25.57
  5514.7   27.46  5535.7   26.92  5616.7   28.03  5754.8   27.39  5857.1   28.79
#Mann= 4 ,-1,0
  4218.3    .135       0    4980     .05       0 5037.63    .135       0
  5264.9      .1       0
Bank Sta=4980,5025
XS Rating Curve= 0 ,0
Exp/Cntr=0.3,0.1

Type RM Length L Ch R = 1 ,11484   ,327.1,616.1,304.3
BEGIN DESCRIPTION:
Jenkins Swamp (SR-134) DS
END DESCRIPTION:
XS GIS Cut Line= 4
      2562313.94       729263.63      2562704.99       729920.09
2562836.13467104730165.6524739492563092.79790551730650.551768219
#Sta/Elev= 30
  4235.9    34.1  4262.8    34.3  4358.4      33  4564.9   27.66    4676   25.84
  4679.1    26.4  4682.5   25.81  4683.1   26.33  4685.3   26.16  4696.1   24.98
  4726.9   23.69  4771.8   23.97  4817.5   22.15  4980.5   22.47    4990    17.8
    5010    17.8  5025.5   22.47    5061   22.62  5069.1   21.94  5091.8   22.62
    5186   22.01  5220.4   22.36  5304.9   24.21    5362   24.23    5420   25.36
    5480   28.33  5527.6   27.71  5572.2   28.97  5735.5   28.23    5827   28.92
#Mann= 4 ,-1,0
  4235.9     .11       0  4685.3     .14       0  4980.5     .05       0
  5025.5     .14       0
Bank Sta=4980.5,5025.5
XS Rating Curve= 0 ,0
Exp/Cntr=0.3,0.1

--- JenkinsSwamp.g05 (geometry) ---

Geom Title=Duplicate Effective
Program Version=6.60

River Reach=Jenkins Swamp   ,Reach-1
Reach XY= 30
      2578677.66       726699.11      2578115.11       726547.31
       2577257.9        726511.6       2576463.2        726574.1
      2574713.06       726913.41      2573484.98        727346.7
      2571827.56       728511.84      2570885.52       728049.09
      2570234.04       727584.19      2569341.76       727704.54
      2568880.96       727908.88      2567990.63       728748.12
      2567633.78       729432.19      2567511.81       730052.51
      2566951.07        730479.1      2565992.19        730476.3
      2565658.55       730187.51      2565284.25       730184.43
      2564943.94       729856.73      2563838.54       729320.95
      2563104.96       729629.58      2561860.65       730464.31
      2561237.85       730607.93      2559875.92       731266.37
      2559573.76       731577.42      2559199.64       731708.55
      2558728.45       732200.43      2558169.67       732562.97
      2557414.57       732696.47      2556444.11       732139.12

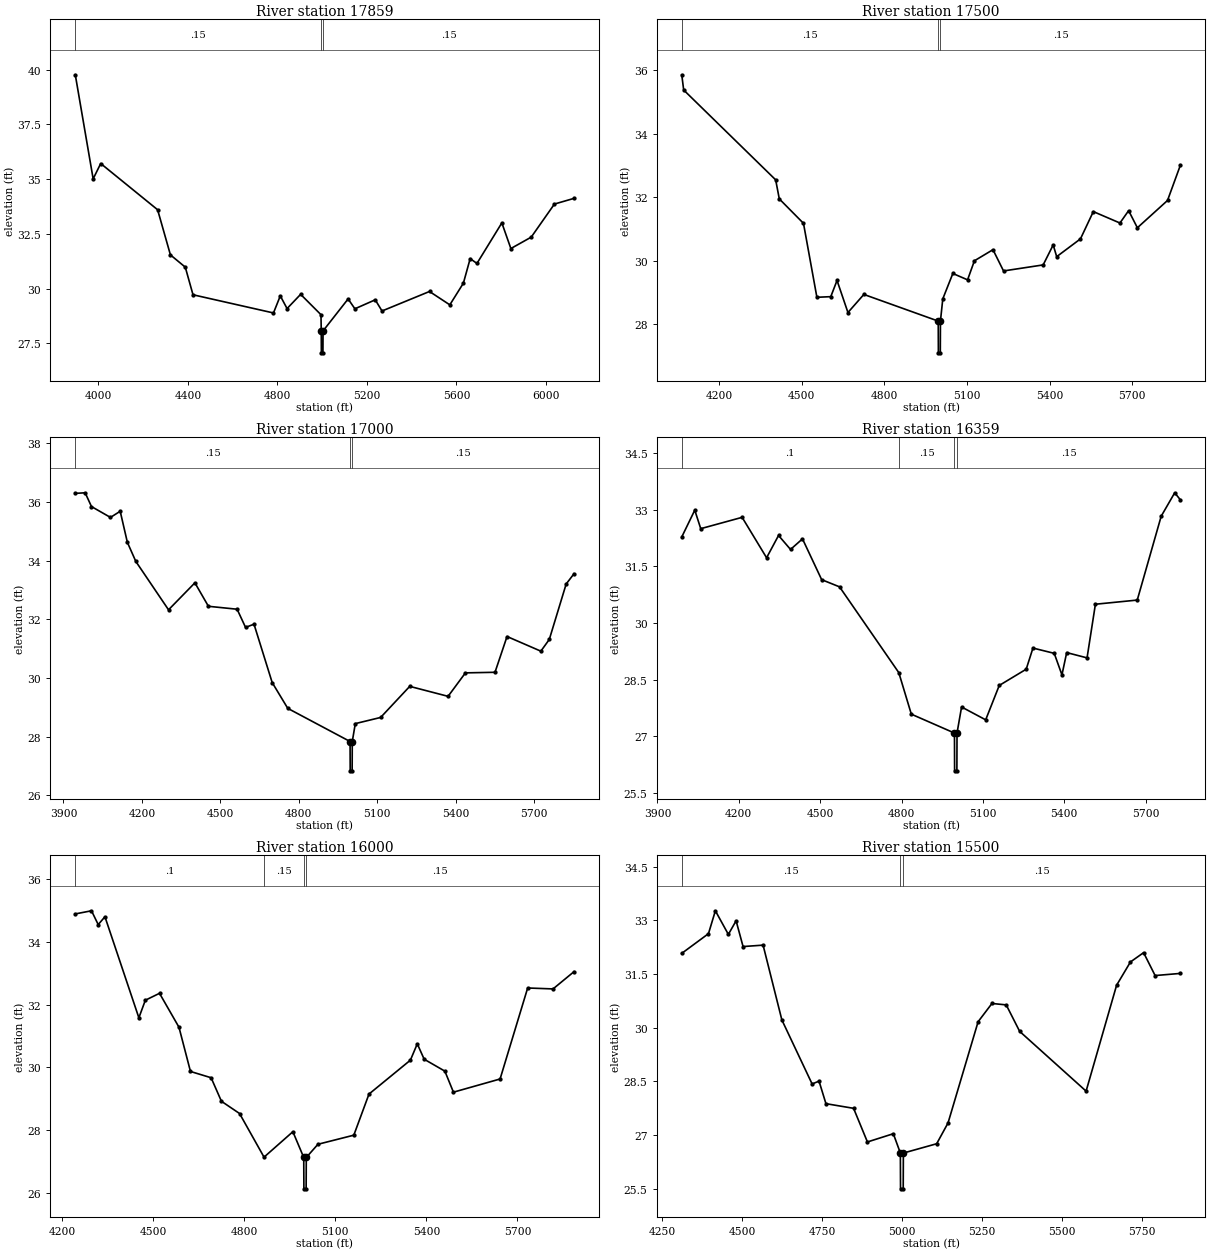
Type RM Length L Ch R = 1 ,17859   ,359,359,359
BEGIN DESCRIPTION:
Jenkins Swamp 36.0
END DESCRIPTION:
XS GIS Cut Line= 3
        2571139.       727013.57      2570982.04       728105.14
      2570825.07       729219.34
#Sta/Elev= 30
  3897.2   39.76    3977   35.01  4010.8   35.71    4265    33.6  4322.2   31.54
  4388.6   30.98  4423.1   29.72  4782.6   28.89    4813   29.67  4843.3   29.09
  4903.9   29.74  4994.8   28.81    4996   28.07  4996.5   27.07  5003.5   27.07
    5004   28.07    5116   29.53  5146.3   29.08  5237.2   29.49  5267.5   28.98
  5479.6   29.87  5570.4   29.26    5631   30.25  5661.3   31.37  5691.6   31.15
  5802.8      33  5843.1   31.83    5934   32.35  6037.7   33.86  6125.2   34.12
#Mann= 3 ,-1,0
  3897.2     .15       0    4996     .05       0    5004     .15       0
Bank Sta=4996,5004
XS Rating Curve= 0 ,0
Exp/Cntr=0.3,0.1

Type RM Length L Ch R = 1 ,17500   ,500,500,500
BEGIN DESCRIPTION:
Jenkins Swamp 35.0
END DESCRIPTION:
XS GIS Cut Line= 4
      2570933.11       727008.86      2570682.21       727909.67
      2570310.59       728449.04       2570101.5       728518.73
#Sta/Elev= 30
  4064.9   35.86  4071.9   35.38  4405.8   32.55    4419   31.95  4506.8   31.18
  4555.5   28.85  4605.9   28.87  4628.6   29.38  4668.2   28.37    4726   28.94
    4996    28.1  4996.5    27.1  5003.5    27.1    5004    28.1  5012.5    28.8
    5049    29.6  5102.5    29.4  5127.3      30  5194.7   30.35    5233   29.68
  5376.9   29.87  5413.3    30.5    5426   30.13  5512.3   30.69    5559   31.55
  5655.6   31.19  5687.2   31.58  5718.9   31.04  5828.3    31.9  5875.4   33.02
#Mann= 3 ,-1,0
  4064.9     .15       0    4996     .05       0    5004     .15       0
Bank Sta=4996,5004
XS Rating Curve= 0 ,0
Exp/Cntr=0.3,0.1

Type RM Length L Ch R = 1 ,17000   ,641,641,641
BEGIN DESCRIPTION:
Jenkins Swamp 34.0
END DESCRIPTION:
XS GIS Cut Line= 3
      2570677.87       726624.97      2570288.54       727605.29
       2569976.1       728397.93
#Sta/Elev= 30
  3945.2   36.29  3982.9   36.31  4007.1   35.84  4079.7   35.47  4116.9   35.68
  4144.3   34.62  4176.6   33.97  4301.7   32.32  4402.5   33.24  4454.2   32.44
  4563.9   32.34  4596.2   31.72  4628.5   31.83    4698   29.84  4757.6   28.96
  4995.8   27.83  4996.3   26.83  5003.7   26.83  5004.2   27.83  5015.8   28.44
  5112.6   28.65  5223.9   29.71  5370.5   29.37  5436.8   30.17  5549.9   30.19
  5595.9   31.41  5725.2   30.91  5757.5   31.31    5822    33.2    5852   33.55
#Mann= 3 ,-1,0
  3945.2     .15       0  4995.8     .05       0  5004.2     .15       0
Bank Sta=4995.8,5004.2
XS Rating Curve= 0 ,0
Exp/Cntr=0.3,0.1

Type RM Length L Ch R = 1 ,16359   ,359,359,359
BEGIN DESCRIPTION:
Jenkins Swamp 33.0
END DESCRIPTION:
XS GIS Cut Line= 4
      2569037.98       726906.81      2569463.34       727142.55
      2569657.78       727629.12      2569850.66       728435.06
#Sta/Elev= 30
  3989.7   32.28  4037.7   32.99  4059.7    32.5  4212.3    32.8  4302.5   31.73
  4346.6   32.32  4390.8   31.95  4434.9   32.23  4505.6   31.15  4571.5   30.96
    4790   28.69  4836.2   27.59  4995.3   27.09  4995.8   26.09  5004.2   26.09
  5004.7   27.09  5021.5   27.78  5110.4   27.44  5160.4   28.35  5259.8   28.78
  5284.7   29.34  5363.2    29.2  5391.6   28.63  5409.1   29.22  5484.2   29.08
    5515    30.5  5669.3   30.61  5757.6   32.83  5807.4   33.45  5828.7   33.26
#Mann= 4 ,-1,0
  3989.7      .1       0    4790     .15       0  4995.3     .05       0
  5004.7     .15       0
Bank Sta=4995.3,5004.7
XS Rating Curve= 0 ,0
Exp/Cntr=0.3,0.1

Type RM Length L Ch R = 1 ,16000   ,500,500,500
BEGIN DESCRIPTION:
Jenkins Swamp 32.0
END DESCRIPTION:
XS GIS Cut Line= 3
      2568952.67       727045.14      2569308.83       727713.01
      2569668.33       728523.13
#Sta/Elev= 30
  4243.1   34.89  4296.5   34.99  4318.6   34.55  4340.8    34.8  4452.6   31.58
  4473.9   32.14  4520.6   32.36  4584.7   31.28  4622.6   29.87  4690.6   29.67
  4724.6   28.92  4784.3   28.53    4865   27.14    4960   27.95  4995.8   27.13
  4996.3   26.13  5003.7   26.13  5004.2   27.13  5042.6   27.55  5160.8   27.84
  5210.8   29.15  5347.2   30.23  5369.9   30.75  5392.6   30.26  5460.8   29.88
    5489   29.21  5642.7   29.63  5733.6   32.53  5817.2    32.5  5886.3   33.05
#Mann= 4 ,-1,0
  4243.1      .1       0    4865     .15       0  4995.8     .05       0
  5004.2     .15       0
Bank Sta=4995.8,5004.2
XS Rating Curve= 0 ,0
Exp/Cntr=0.3,0.1

Type RM Length L Ch R = 1 ,15500   ,500,500,500
BEGIN DESCRIPTION:
Jenkins Swamp 31.0
END DESCRIPTION:
XS GIS Cut Line= 3
      2568484.86       727349.26      2568869.95       727919.64
      2569350.61       728646.12
#Sta/Elev= 30
  4311.8   32.08  4395.3   32.63  4416.9   33.27  4457.5   32.61  4481.7   32.99
  4503.5   32.27  4566.1   32.31  4624.8   30.22  4719.4   28.43    4741   28.51
  4762.6   27.88    4849   27.75  4892.3   26.81  4973.3   27.04  4995.3    26.5
  4995.8    25.5  5004.2    25.5  5004.7    26.5  5108.8   26.76  5144.3   27.34
  5238.4   30.17  5281.7   30.68  5326.3   30.64  5368.3    29.9    5576   28.23
  5671.4   31.19  5714.7   31.84  5755.8    32.1  5791.8   31.46  5871.1   31.52
#Mann= 3 ,-1,0
  4311.8     .15       0  4995.3     .05       0  5004.7     .15       0
Bank Sta=4995.3,5004.7
XS Rating Curve= 0 ,0
Exp/Cntr=0.3,0.1

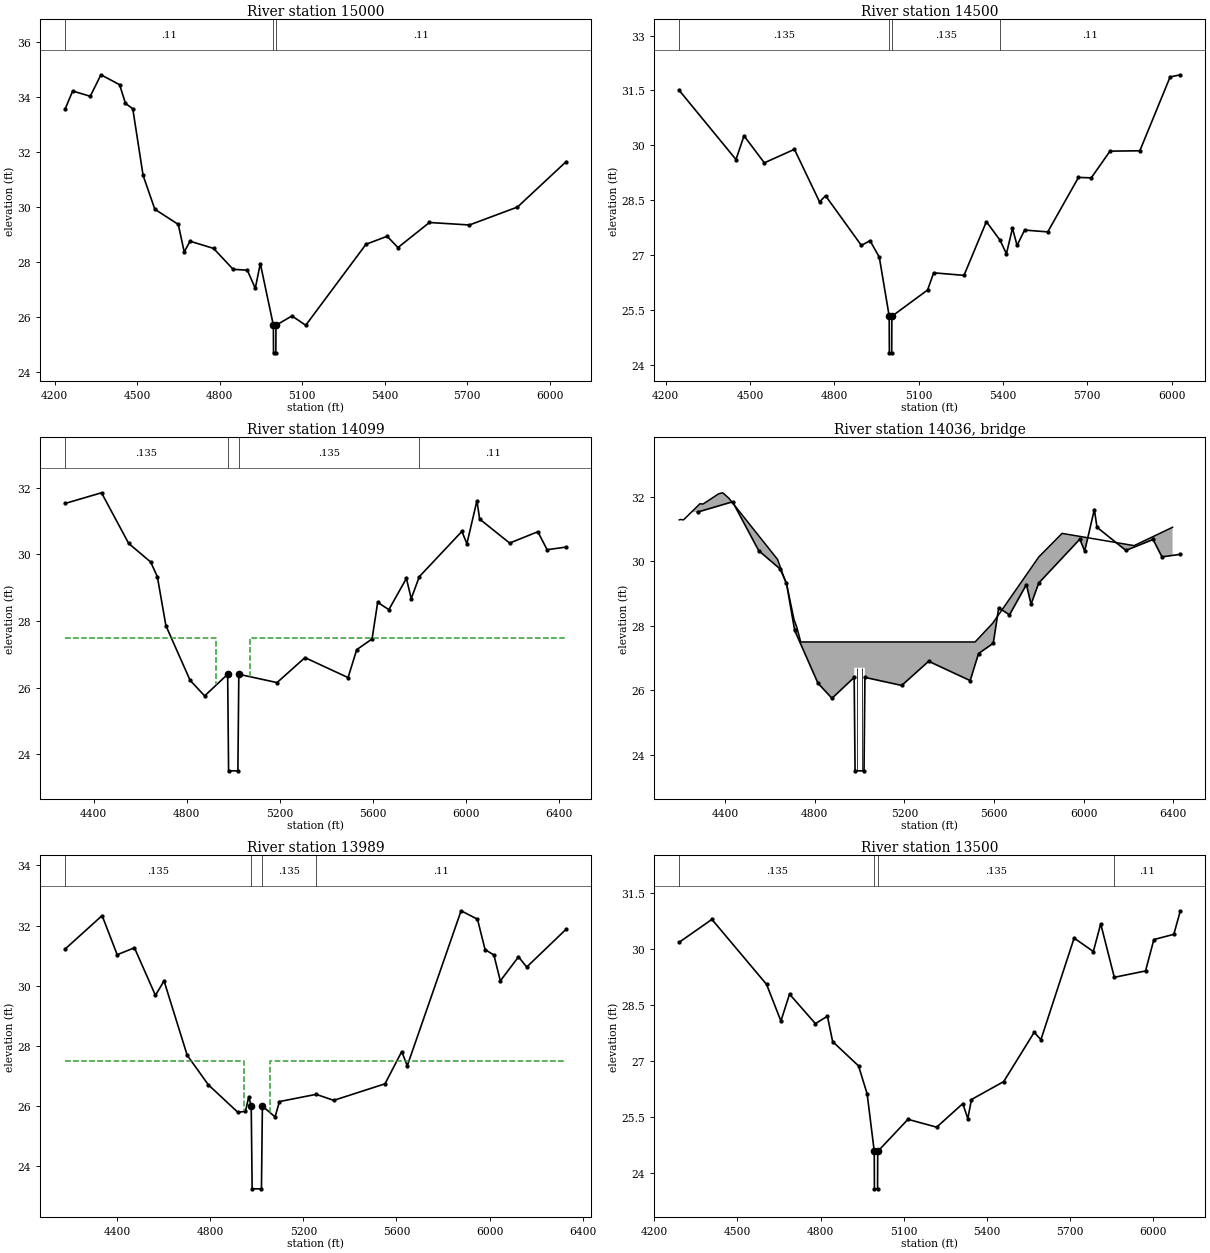
Type RM Length L Ch R = 1 ,15000   ,500,500,500
BEGIN DESCRIPTION:
Jenkins Swamp 30.0
END DESCRIPTION:
XS GIS Cut Line= 4
      2568032.66       727668.98      2568511.63       728260.86
      2568926.19       728778.88      2569074.83       729145.84
#Sta/Elev= 30
  4238.6   33.56  4265.9   34.21  4329.9   34.02  4368.5    34.8  4436.5   34.44
  4457.8   33.76  4484.3   33.57  4521.8   31.15  4564.5   29.92  4649.8   29.37
  4671.2   28.37  4692.5   28.76  4777.8    28.5  4849.1   27.74  4900.6   27.71
  4929.5   27.05  4947.8   27.95  4995.3   25.71  4995.8   24.71  5004.2   24.71
  5004.7   25.71  5062.9   26.05  5112.8   25.71  5331.9   28.65  5408.8   28.94
    5448   28.53  5562.4   29.44  5707.8   29.35  5882.3      30  6059.4   31.65
#Mann= 3 ,-1,0
  4238.6     .11       0  4995.3     .05       0  5004.7     .11       0
Bank Sta=4995.3,5004.7
XS Rating Curve= 0 ,0
Exp/Cntr=0.3,0.1

Type RM Length L Ch R = 1 ,14500   ,401,401,401
BEGIN DESCRIPTION:
Jenkins Swamp 29.0
END DESCRIPTION:
XS GIS Cut Line= 3
      2567635.94       728029.14      2568138.89       728587.66
      2568988.85       729171.92
#Sta/Elev= 30
  4248.4    31.5  4450.1   29.61  4478.6   30.26  4550.9   29.52    4658   29.89
  4747.5   28.45  4768.8   28.62  4896.2   27.26  4926.9   27.39    4960   26.94
  4995.3   25.32  4995.8   24.32  5004.2   24.32  5004.7   25.32  5131.9   26.04
  5153.5   26.51  5261.4   26.44  5341.1   27.91    5390    27.4  5412.4   27.03
    5434   27.73  5450.3   27.26  5477.1   27.68  5559.5   27.63  5668.8   29.12
  5714.4   29.11    5781   29.84  5887.2   29.85  5994.9   31.87  6031.4   31.93
#Mann= 4 ,-1,0
  4248.4    .135       0  4995.3     .05       0  5004.7    .135       0
    5390     .11       0
Bank Sta=4995.3,5004.7
XS Rating Curve= 0 ,0
Exp/Cntr=0.5,0.3

Type RM Length L Ch R = 1 ,14099   ,110,110,110
BEGIN DESCRIPTION:
Jenkins Swamp (Shad Rd) US
END DESCRIPTION:
XS GIS Cut Line= 5
      2567307.04        728573.5      2567450.04       728754.97
      2567917.51       728907.63      2568671.43       729136.79
      2569038.68       729665.59
#Sta/Elev= 30
  4277.2   31.53  4433.5   31.85  4550.3   30.33    4645   29.77  4673.7   29.33
  4710.4   27.86  4814.4   26.22    4877   25.75    4976    26.4    4980    23.5
    5020    23.5    5024    26.4  5188.3   26.15  5308.5    26.9  5493.8    26.3
  5531.1   27.14    5597   27.46  5621.1   28.56  5669.2   28.34  5744.7   29.28
  5765.4   28.67    5800   29.33  5983.3   30.69  6004.8   30.32  6047.9   31.61
  6059.7   31.06  6188.7   30.34  6309.9   30.68  6349.7   30.14  6431.8   30.22
#Mann= 4 ,-1,0
  4277.2    .135       0    4976     .05       0    5024    .135       0
    5800     .11       0
#XS Ineff= 2 , 0
       0  4927.5    27.5  5072.5       0    27.5
Permanent Ineff=
       F       F
Bank Sta=4976,5024
XS Rating Curve= 0 ,0
Exp/Cntr=0.5,0.3

Type RM Length L Ch R = 3 ,14036   ,,,
BEGIN DESCRIPTION:
Jenkins Swamp (Shad Rd) TOR
Structure ID: LDS_JKS_03
Approximate Survey Structure
END DESCRIPTION:
Bridge Culvert--1,0,-1,-1, 0
Deck Dist Width WeirC Skew NumUp NumDn MinLoCord MaxHiCord MaxSubmerge Is_Ogee
49,28,3,0, 24, 24, , , 0.95, 0, 1,1,,
  4195.7  4201.4  4214.6  4287.7  4300.6  4305.8  4371.7  4389.6  4416.9  4634.3
    4676  4707.2  4720.8  4737.6  4976.5  4976.5  5023.5  5023.5  5515.7    5594
  5800.1  5903.9  6225.5  6397.1
   31.29    31.3   31.29   31.79   31.78    31.8    32.1   32.13   31.96   30.06
   29.25   28.21   27.94    27.5    27.5    27.5    27.5    27.5    27.5   28.08
   30.14   30.87   30.49   31.06
    3.39    3.39    3.39    3.39    3.39    3.39    3.39    3.39    3.39    3.39
    3.39    3.39    3.39    3.39    3.39    26.7    26.7    3.39    3.39    3.39
    3.39    3.39    3.39    3.39
  4195.7  4201.4  4214.6  4287.7  4300.6  4305.8  4371.7  4389.6  4416.9  4634.3
    4676  4707.2  4720.8  4737.6  4976.5  4976.5  5023.5  5023.5  5515.7    5594
  5800.1  5903.9  6225.5  6397.1
   31.29    31.3   31.29   31.79   31.78    31.8    32.1   32.13   31.96   30.06
   29.25   28.21   27.94    27.5    27.5    27.5    27.5    27.5    27.5   28.08
   30.14   30.87   30.49   31.06
    3.39    3.39    3.39    3.39    3.39    3.39    3.39    3.39    3.39    3.39
    3.39    3.39    3.39    3.39    3.39    26.7    26.7    3.39    3.39    3.39
    3.39    3.39    3.39    3.39
Pier Skew, UpSta & Num, DnSta & Num=  ,4988.3, 2 ,4988.3, 2 , 0 , 0 , 0 ,0,0
       1       1
    18.5    26.7
       1       1
   18.25    26.7
Pier Skew, UpSta & Num, DnSta & Num=  ,5011.8, 2 ,5011.8, 2 , 0 , 0 , 0 ,0,0
       1       1
    18.5    26.7
       1       1
   18.25    26.7
Abutment Skew #Up #Dn= , 2 , 2
  4976.5  4979.5
    26.7   19.05
  4976.5  4979.5
    26.7    18.8
Abutment Skew #Up #Dn= , 2 , 2
  5020.5  5023.5
   19.05    26.7
  5020.5  5023.5
    18.8    26.7
BR Coef= 1 , 1 , 0 ,1.25, 0 ,,,0.8,0,2,0,
WSPro=,,,, 1 ,,,, 0 ,,,, 0 ,,,,-1 ,-1 ,-1 , 0 , 0 , 0 , 0 , 0
BC Design=,, 0 ,, 0 ,,,,,,
BC HTab HWMax=31.87
BC Use User HTab Curves=0
BC User HTab FreeFlow(D)= 0

Type RM Length L Ch R = 1 ,13989   ,489,489,489
BEGIN DESCRIPTION:
Jenkins Swamp (Shad Rd) DS
END DESCRIPTION:
XS GIS Cut Line= 5
      2567191.15        728631.2      2567296.18       728776.71
      2567895.24       729012.65      2568590.65       729234.29
      2568905.07       729744.39
#Sta/Elev= 30
  4176.7   31.22  4335.5   32.33  4400.2   31.03  4474.3   31.26  4564.5   29.68
  4601.5   30.16  4700.9   27.69  4791.5   26.71  4919.1   25.79  4951.4   25.83
  4965.5   26.31    4976      26    4980   23.25    5020   23.25    5024      26
  5078.5   25.64  5097.2   26.15    5255   26.39  5330.4   26.19  5550.8   26.74
  5622.5   27.81  5646.4   27.34  5877.6   32.49    5948   32.21  5980.6    31.2
  6018.5   31.02  6046.1   30.16  6124.2   30.96  6159.5   30.62  6329.1   31.88
#Mann= 4 ,-1,0
  4176.7    .135       0    4976     .05       0    5024    .135       0
    5255     .11       0
#XS Ineff= 2 , 0
       0  4943.5    27.5  5056.5       0    27.5
Permanent Ineff=
       F       F
Bank Sta=4976,5024
XS Rating Curve= 0 ,0
Exp/Cntr=0.5,0.3

Type RM Length L Ch R = 1 ,13500   ,500,500,500
BEGIN DESCRIPTION:
Jenkins Swamp 27.0
END DESCRIPTION:
XS GIS Cut Line= 3
      2566956.61       729236.17      2567640.77       729424.84
       2568690.1       729749.46
#Sta/Elev= 30
  4290.3   30.18  4407.9   30.79  4605.2   29.05  4656.9   28.07    4688   28.79
  4781.4      28  4824.7    28.2  4843.6   27.52    4937   26.87  4968.1   26.12
  4993.8   24.58  4994.3   23.58  5005.7   23.58  5006.2   24.58  5115.4   25.44
    5219   25.23  5313.2   25.86  5331.3   25.46  5344.6   25.97  5460.9   26.45
  5571.1   27.77  5595.1   27.57    5715   30.29  5784.3   29.93    5811   30.67
    5860   29.24  5972.7   29.41  6002.8   30.25  6074.8   30.39  6098.4   31.02
#Mann= 4 ,-1,0
  4290.3    .135       0  4993.8     .05       0  5006.2    .135       0
    5860     .11       0
Bank Sta=4993.8,5006.2
XS Rating Curve= 0 ,0
Exp/Cntr=0.3,0.1