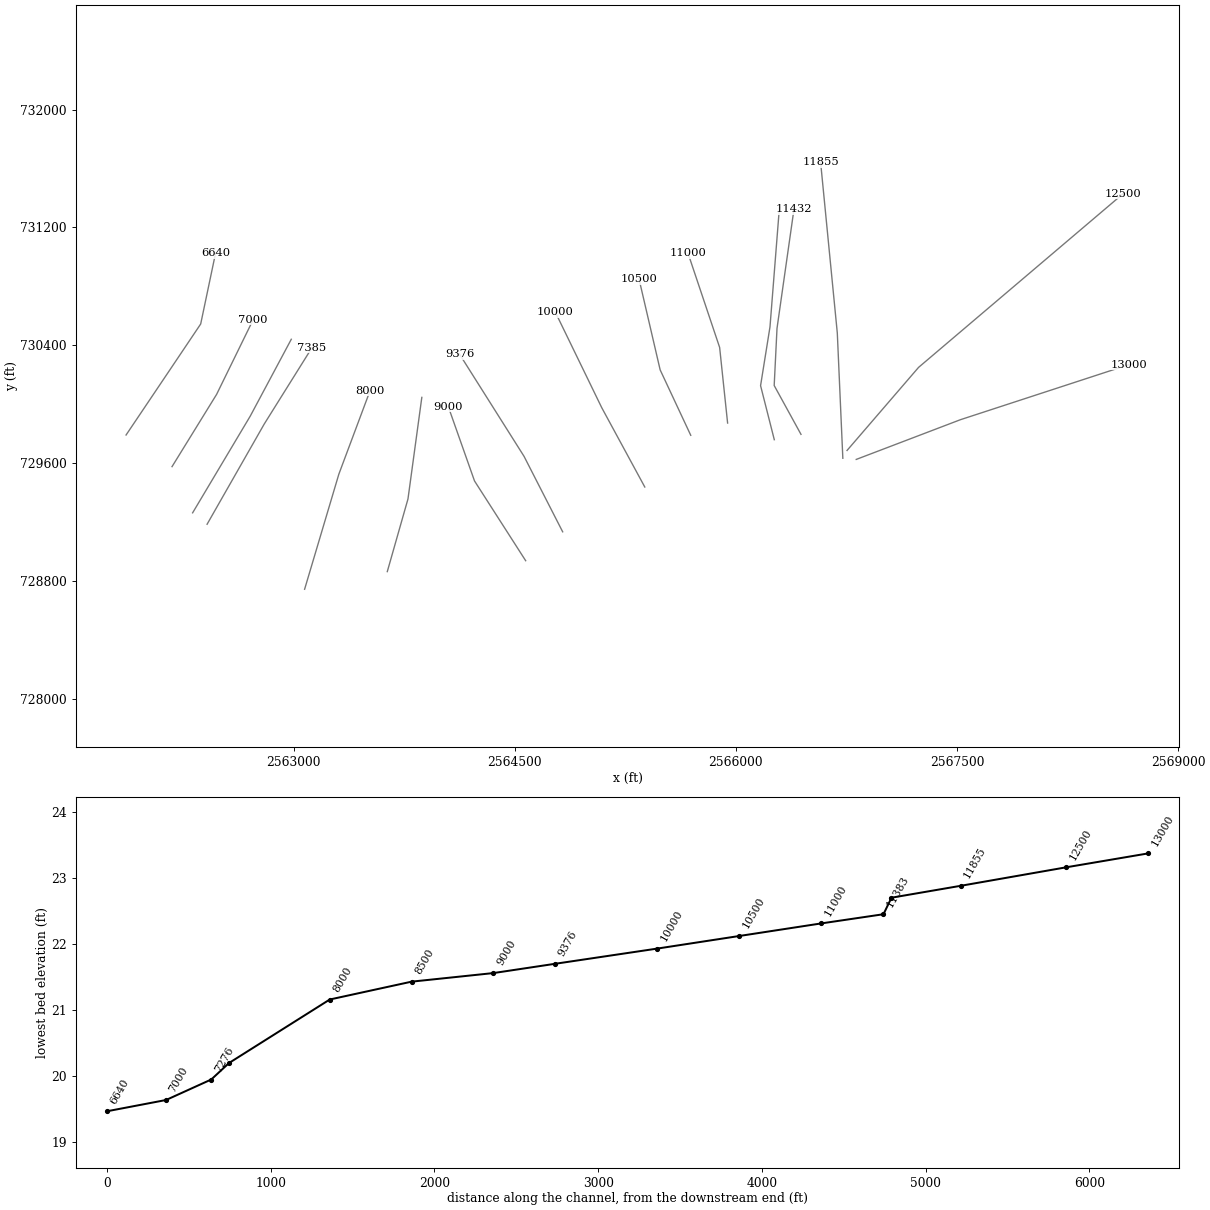
HEC-RAS study JenkinsSwamp.prj: S-26-134 over Jenkins Swamp

--- JenkinsSwamp.g05 (geometry) --- (continued)

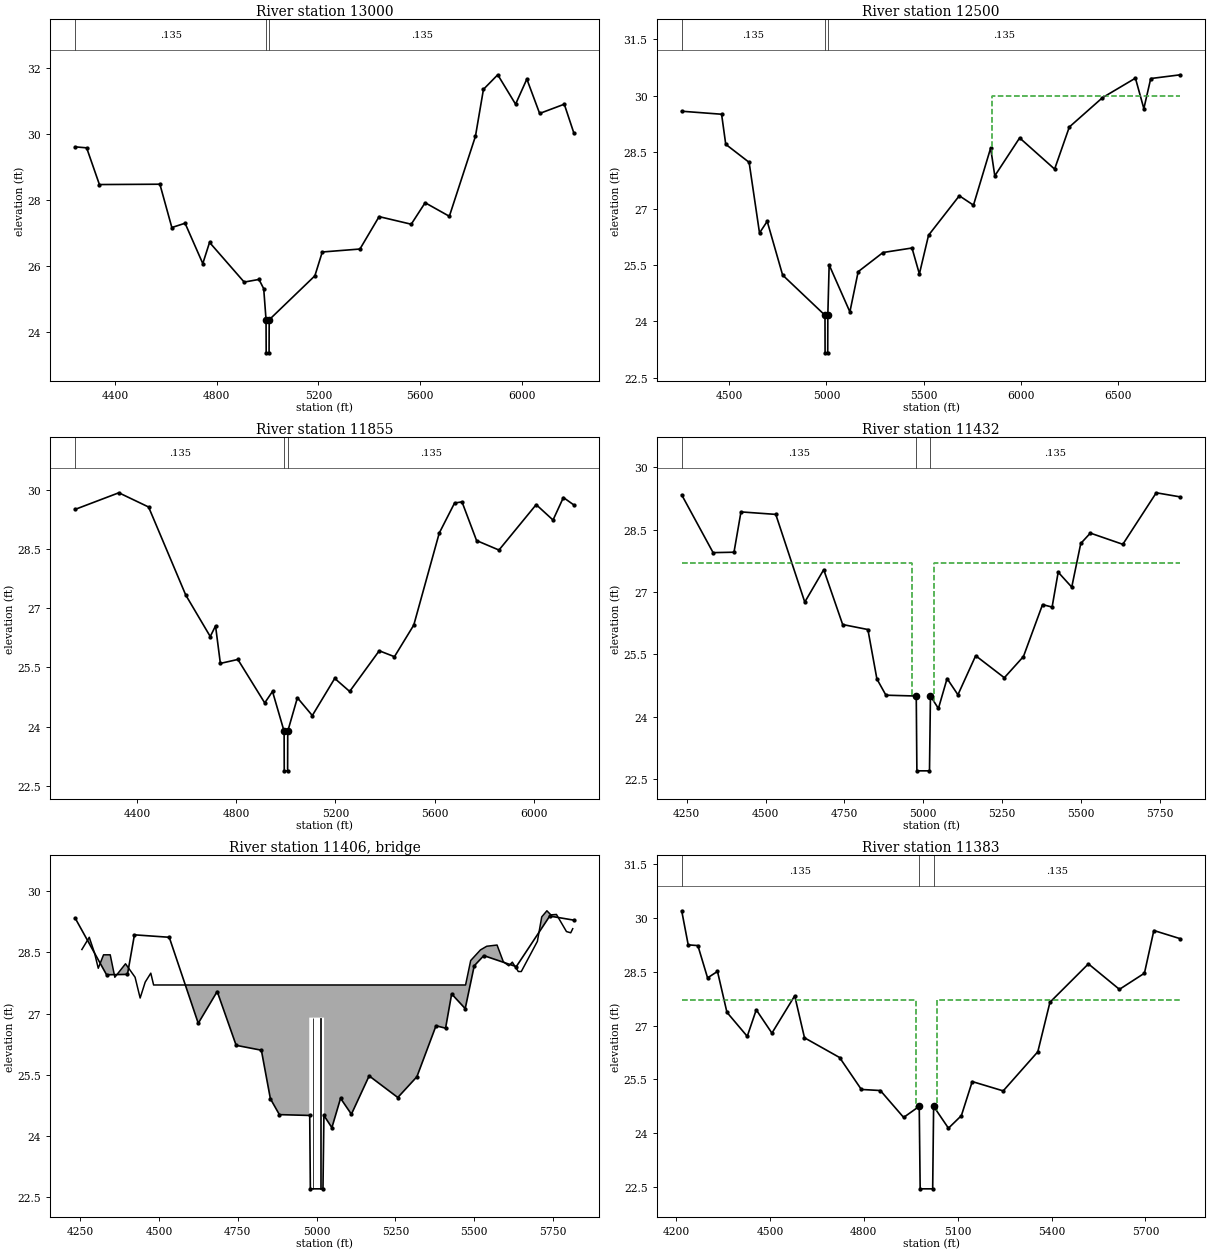
Type RM Length L Ch R = 1 ,13000   ,500,500,500
BEGIN DESCRIPTION:
Jenkins Swamp 26.0
END DESCRIPTION:
XS GIS Cut Line= 3
       2566816.3       729626.04      2567523.35       729895.65
       2568668.2       730269.67
#Sta/Elev= 30
  4243.3    29.6  4288.4   29.57  4338.6   28.46  4576.4   28.47  4623.4   27.16
  4675.4   27.29  4745.1   26.07  4771.7   26.71  4907.8   25.51    4966   25.59
  4984.6   25.31  4993.8   24.37  4994.3   23.37  5005.7   23.37  5006.2   24.37
  5185.8    25.7  5214.9   26.42    5363   26.51  5438.3   27.49  5564.6   27.26
  5619.3   27.91  5714.5    27.5  5817.1   29.92  5848.6   31.34  5904.8   31.78
  5974.9   30.89  6019.2   31.65  6069.5   30.61  6166.4   30.89  6204.4   30.01
#Mann= 3 ,-1,0
  4243.3    .135       0  4993.8     .05       0  5006.2    .135       0
Bank Sta=4993.8,5006.2
XS Rating Curve= 0 ,0
Exp/Cntr=0.3,0.1

Type RM Length L Ch R = 1 ,12500   ,645,645,645
BEGIN DESCRIPTION:
Jenkins Swamp 25.0
END DESCRIPTION:
XS GIS Cut Line= 3
       2566753.9       729686.85      2567239.24       730250.62
      2568626.51       731428.86
#Sta/Elev= 30
  4256.1   29.59  4461.2   29.51  4482.5   28.71  4602.7   28.23  4656.1   26.35
  4695.7   26.66  4774.9   25.23  4992.7   24.16  4993.2   23.16  5006.8   23.16
  5007.3   24.16  5014.1    25.5  5120.7   24.25  5163.3   25.32    5291   25.83
    5440   25.95  5477.9   25.26  5525.1   26.29  5683.2   27.34    5756   27.09
  5844.3   28.61  5865.6   27.87  5993.3   28.88  6173.1   28.05  6248.7   29.17
    6419   29.95  6588.5   30.47  6631.8   29.66  6667.2   30.46  6820.1   30.56
#Mann= 3 ,-1,0
  4256.1    .135       0  4992.7     .05       0  5007.3    .135       0
#XS Ineff= 2 , 0
       0                    5850       0      30
Permanent Ineff=
       F       F
Bank Sta=4992.7,5007.3
XS Rating Curve= 0 ,0
Exp/Cntr=0.3,0.1

Type RM Length L Ch R = 1 ,11855   ,423,423,423
BEGIN DESCRIPTION:
Jenkins Swamp 24.0
END DESCRIPTION:
XS GIS Cut Line= 3
      2566725.36       729633.89      2566687.81       730483.96
      2566574.64       731641.24
#Sta/Elev= 30
  4149.1    29.5  4325.4   29.92  4445.5   29.56  4595.6   27.33  4694.5   26.28
  4715.8   26.55  4735.3    25.6  4805.9    25.7  4914.4    24.6  4945.8   24.89
  4992.7   23.88  4993.2   22.88  5006.8   22.88  5007.3   23.88  5046.3   24.73
  5106.5   24.28    5197   25.22  5257.3   24.89  5376.7   25.92  5438.1   25.77
  5516.1   26.57    5619    28.9  5680.8   29.66  5710.8   29.69  5769.7   28.71
  5860.1   28.47  6010.3   29.62  6078.3   29.23  6120.2    29.8  6162.8   29.61
#Mann= 3 ,-1,0
  4149.1    .135       0  4992.7     .05       0  5007.3    .135       0
Bank Sta=4992.7,5007.3
XS Rating Curve= 0 ,0
Exp/Cntr=0.5,0.3

Type RM Length L Ch R = 1 ,11432   ,49,49,49
BEGIN DESCRIPTION:
Jenkins Swamp (HWY-134) US
END DESCRIPTION:
XS GIS Cut Line= 4
       2566441.4        729796.2      2566259.63       730127.47
      2566278.73       730515.14      2566393.72        731323.1
#Sta/Elev= 30
    4234   29.34  4333.6   27.95  4399.9   27.96    4422   28.93  4532.4   28.87
  4624.4   26.76  4684.5   27.54  4744.6   26.22  4824.6    26.1  4853.2   24.91
  4881.8   24.52    4978    24.5    4980    22.7    5020    22.7    5023    24.5
  5048.3    24.2  5075.8   24.92  5110.2   24.53  5166.5   25.47  5257.4   24.94
    5318   25.45  5378.6    26.7  5408.9   26.64  5428.2   27.48  5471.2   27.12
  5499.8   28.17  5530.2   28.42  5633.2   28.15  5739.3   29.39  5816.1   29.29
#Mann= 3 ,-1,0
    4234    .135       0    4978     .05       0    5023    .135       0
#XS Ineff= 2 , 0
       0  4964.5    27.7  5035.5       0    27.7
Permanent Ineff=
       F       F
Bank Sta=4978,5023
XS Rating Curve= 0 ,0
Exp/Cntr=0.5,0.3

Type RM Length L Ch R = 3 ,11406   ,,,
BEGIN DESCRIPTION:
Jenkins Swamp (HWY-134) TOR
Structure ID: LDS_JKS_02
Approximate Survey Structure
END DESCRIPTION:
Bridge Culvert--1,0,-1,-1, 0
Deck Dist Width WeirC Skew NumUp NumDn MinLoCord MaxHiCord MaxSubmerge Is_Ogee
12,28,3,0, 35, 35, , , 0.95, 0, 1,1,,
  4255.3  4278.7  4295.6  4307.2    4324  4345.2  4359.8  4393.7    4424  4440.1
  4456.1  4473.9  4482.8  4976.5  4976.5  5023.5  5023.5  5472.3  5488.6  5519.5
  5539.4  5572.2  5592.1  5609.5  5620.6  5639.7  5649.1  5700.1  5713.9  5730.3
  5742.9  5760.6  5792.4  5805.9  5812.2
   28.57   28.87   28.48   28.11   28.44   28.44   27.89   28.22   27.89   27.38
   27.77   27.99    27.7    27.7    27.7    27.7    27.7    27.7    28.3   28.56
   28.65   28.68   28.27   28.17   28.26   28.03   28.03   28.77   29.37   29.52
   29.42   29.43   29.01   28.98   29.08
    2.64    2.64    2.64    2.64    2.64    2.64    2.64    2.64    2.64    2.64
    2.64    2.64    2.64    2.64    26.9    26.9    2.64    2.64    2.64    2.64
    2.64    2.64    2.64    2.64    2.64    2.64    2.64    2.64    2.64    2.64
    2.64    2.64    2.64    2.64    2.64
  4255.3  4278.7  4295.6  4307.2    4324  4345.2  4359.8  4393.7    4424  4440.1
  4456.1  4473.9  4482.8  4976.5  4976.5  5023.5  5023.5  5472.3  5488.6  5519.5
  5539.4  5572.2  5592.1  5609.5  5620.6  5639.7  5649.1  5700.1  5713.9  5730.3
  5742.9  5760.6  5792.4  5805.9  5812.2
   28.57   28.87   28.48   28.11   28.44   28.44   27.89   28.22   27.89   27.38
   27.77   27.99    27.7    27.7    27.7    27.7    27.7    27.7    28.3   28.56
   28.65   28.68   28.27   28.17   28.26   28.03   28.03   28.77   29.37   29.52
   29.42   29.43   29.01   28.98   29.08
    2.64    2.64    2.64    2.64    2.64    2.64    2.64    2.64    2.64    2.64
    2.64    2.64    2.64    2.64    26.9    26.9    2.64    2.64    2.64    2.64
    2.64    2.64    2.64    2.64    2.64    2.64    2.64    2.64    2.64    2.64
    2.64    2.64    2.64    2.64    2.64
Pier Skew, UpSta & Num, DnSta & Num=  ,4988.3, 2 ,4988.3, 2 , 0 , 0 , 0 ,0,0
       1       1
    17.7    26.9
       1       1
   17.45    26.9
Pier Skew, UpSta & Num, DnSta & Num=  ,5011.8, 2 ,5011.8, 2 , 0 , 0 , 0 ,0,0
       1       1
    17.7    26.9
       1       1
   17.45    26.9
Abutment Skew #Up #Dn= , 2 , 2
  4976.5  4979.5
    26.9   18.25
  4976.5  4979.5
    26.9      18
Abutment Skew #Up #Dn= , 2 , 2
  5020.5  5023.5
   18.25    26.9
  5020.5  5023.5
      18    26.9
BR Coef= 1 , 1 , 0 ,1.25, 0 ,,,0.8,0,2,0,
WSPro=,,,, 1 ,,,, 0 ,,,, 0 ,,,,-1 ,-1 ,-1 , 0 , 0 , 0 , 0 , 0
BC Design=,, 0 ,, 0 ,,,,,,
BC HTab HWMax=29.45
BC Use User HTab Curves=0
BC User HTab FreeFlow(D)= 0

Type RM Length L Ch R = 1 ,11383   ,383,383,383
BEGIN DESCRIPTION:
Jenkins Swamp (HWY-134) DS
END DESCRIPTION:
XS GIS Cut Line= 4
      2566260.33       729759.87      2566167.24       730126.52
      2566231.07       730525.36      2566295.07       731334.84
#Sta/Elev= 30
  4217.8    30.2  4238.6   29.25  4269.5   29.23  4300.5   28.33  4332.2   28.51
  4362.4   27.37  4427.3    26.7  4456.1   27.44  4506.2   26.79    4579   27.83
  4610.3   26.66  4722.5   26.11    4792   25.22  4852.8   25.19  4927.2   24.44
    4977   24.75    4980   22.45    5020   22.45    5023   24.75  5070.4   24.14
  5111.7   24.49  5146.4   25.44  5245.4   25.18    5356   26.27  5394.8   27.65
  5517.7   28.72  5616.9   28.01  5696.8   28.46  5726.9   29.65    5812   29.42
#Mann= 3 ,-1,0
  4217.8    .135       0    4977     .05       0    5023    .135       0
#XS Ineff= 2 , 0
       0  4967.5    27.7  5032.5       0    27.7
Permanent Ineff=
       F       F
Bank Sta=4977,5023
XS Rating Curve= 0 ,0
Exp/Cntr=0.5,0.3

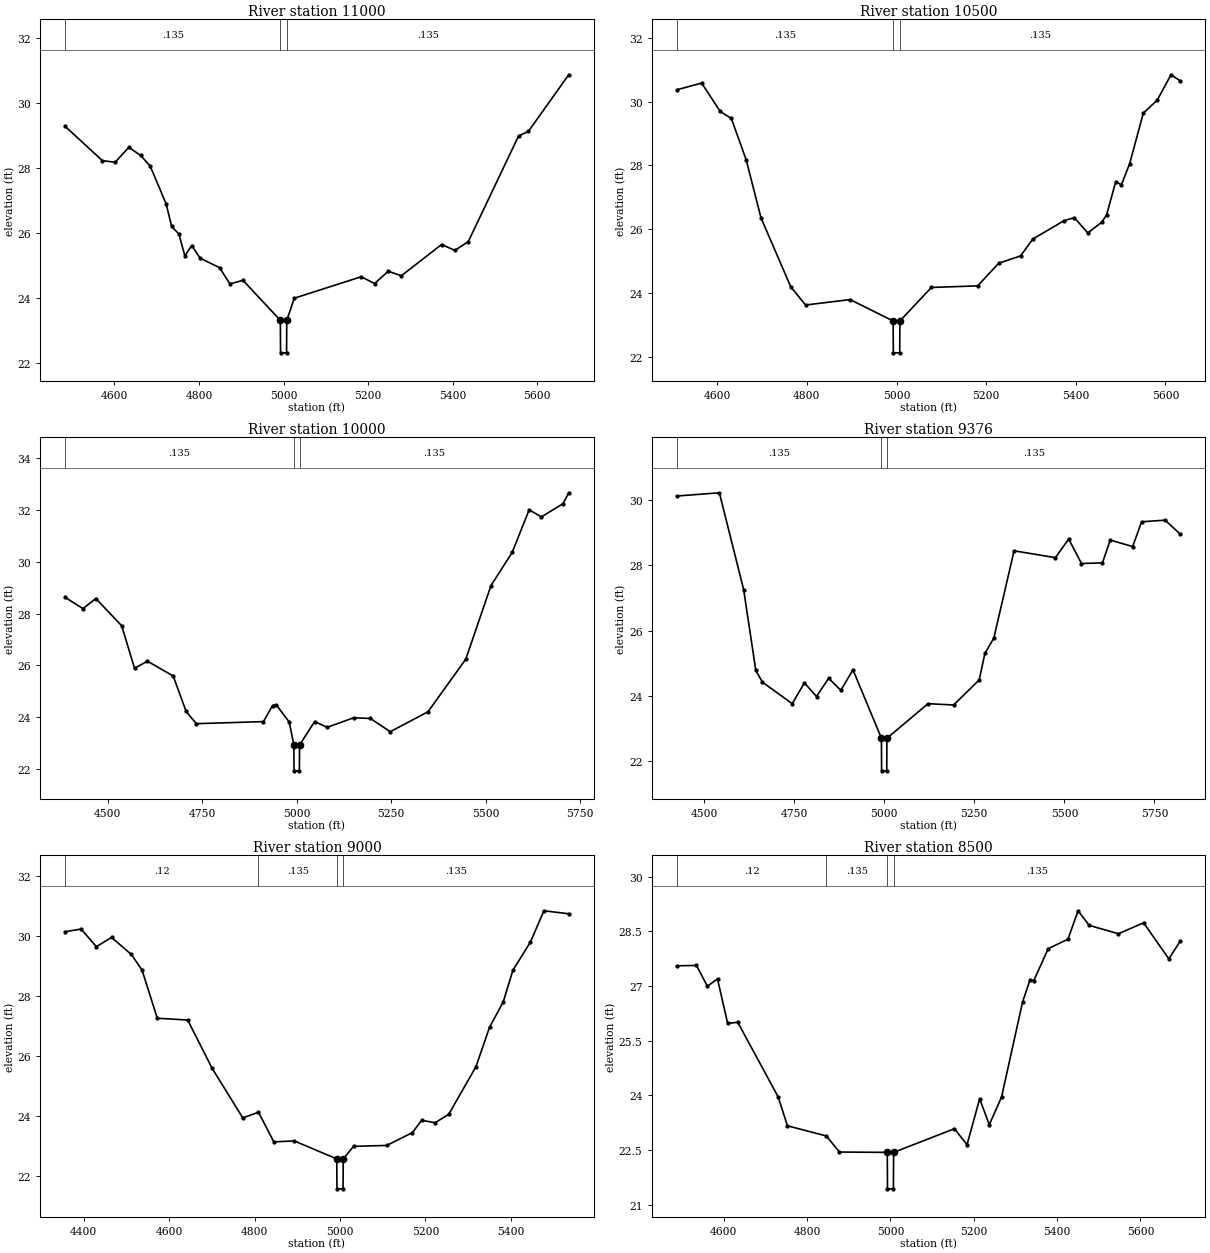
Type RM Length L Ch R = 1 ,11000   ,500,500,500
BEGIN DESCRIPTION:
Jenkins Swamp 22.0
END DESCRIPTION:
XS GIS Cut Line= 3
      2565943.58        729872.8      2565889.48       730385.95
      2565674.99       731025.02
#Sta/Elev= 30
    4484   29.27  4571.7   28.22  4601.9   28.17  4634.2   28.63  4662.2   28.38
  4684.8   28.05  4722.5   26.89  4735.4    26.2  4752.7   25.96  4766.7   25.29
  4782.9   25.61  4802.8   25.22  4848.6   24.93  4873.4   24.43    4904   24.54
  4992.4   23.31  4992.9   22.31  5007.1   22.31  5007.6   23.31  5025.4   23.99
  5183.6   24.65  5215.2   24.44  5247.6   24.82  5278.5   24.68  5373.5   25.64
  5405.1   25.46  5436.7   25.73  5555.6   28.98  5578.8   29.12  5674.1   30.86
#Mann= 3 ,-1,0
    4484    .135       0  4992.4     .05       0  5007.6    .135       0
Bank Sta=4992.4,5007.6
XS Rating Curve= 0 ,0
Exp/Cntr=0.3,0.1

Type RM Length L Ch R = 1 ,10500   ,500,500,500
BEGIN DESCRIPTION:
Jenkins Swamp 21.0
END DESCRIPTION:
XS GIS Cut Line= 3
       2565693.5       729789.75       2565485.9       730233.71
      2565342.62       730850.18
#Sta/Elev= 30
  4509.9   30.37  4565.4   30.58  4606.8   29.69  4631.6   29.47  4664.7   28.17
  4697.8   26.35  4764.1   24.19  4797.2   23.62  4896.5   23.79  4992.4   23.12
  4992.9   22.12  5007.1   22.12  5007.6   23.12  5077.7   24.17    5181   24.22
  5227.9   24.93  5276.7   25.16  5304.2   25.69  5373.1   26.26  5396.6   26.36
  5426.7   25.88  5458.2   26.22  5468.7   26.45    5489   27.49  5501.6   27.39
  5519.8   28.04  5550.6   29.64  5581.4   30.04  5612.2   30.84  5632.9   30.65
#Mann= 3 ,-1,0
  4509.9    .135       0  4992.4     .05       0  5007.6    .135       0
Bank Sta=4992.4,5007.6
XS Rating Curve= 0 ,0
Exp/Cntr=0.3,0.1

Type RM Length L Ch R = 1 ,10000   ,624,624,624
BEGIN DESCRIPTION:
Jenkins Swamp 20.0
END DESCRIPTION:
XS GIS Cut Line= 3
      2565381.63       729438.86      2565089.47       729977.31
        2564775.         730625.
#Sta/Elev= 30
  4387.4   28.62  4434.2   28.19  4468.3   28.58  4536.6   27.53  4570.7   25.89
  4604.9   26.16  4673.1   25.59  4707.3   24.22  4734.4   23.75    4912   23.83
    4936   24.45  4946.2   24.47  4980.3   23.81  4992.4   22.93  4992.9   21.93
  5007.1   21.93  5007.6   22.93  5047.5   23.83  5080.8   23.61  5151.1   23.98
  5195.2   23.95  5247.6   23.44  5347.6   24.21  5447.6   26.24  5514.3   29.08
  5570.3   30.36  5615.2      32  5647.7   31.73    5705   32.24    5720   32.66
#Mann= 3 ,-1,0
  4387.4    .135       0  4992.4     .05       0  5007.6    .135       0
Bank Sta=4992.4,5007.6
XS Rating Curve= 0 ,0
Exp/Cntr=0.3,0.1

Type RM Length L Ch R = 1 ,9376    ,376,376,376
BEGIN DESCRIPTION:
Jenkins Swamp 19.0
END DESCRIPTION:
XS GIS Cut Line= 3
      2564824.53       729134.82       2564562.4       729647.05
      2564123.88       730341.72
#Sta/Elev= 30
  4424.6   30.13  4542.7   30.23  4610.1   27.26  4643.8   24.78  4662.2   24.42
  4744.9   23.76  4778.6    24.4  4812.3   23.98  4845.9   24.54  4879.7   24.17
  4913.4    24.8  4992.4    22.7  4992.9    21.7  5007.1    21.7  5007.6    22.7
  5121.7   23.76  5192.7   23.72  5263.7   24.49  5279.4    25.3  5304.2   25.77
  5360.4   28.45  5475.1   28.24    5512   28.81  5547.5   28.06  5605.6   28.08
  5627.3   28.78  5689.4   28.58  5714.3   29.34  5779.6   29.39  5821.5   28.96
#Mann= 3 ,-1,0
  4424.6    .135       0  4992.4     .05       0  5007.6    .135       0
Bank Sta=4992.4,5007.6
XS Rating Curve= 0 ,0
Exp/Cntr=0.3,0.1

Type RM Length L Ch R = 1 ,9000    ,500,500,500
BEGIN DESCRIPTION:
Jenkins Swamp 18.0
END DESCRIPTION:
XS GIS Cut Line= 3
      2564573.44        728938.8       2564226.4       729479.99
       2564048.3       729984.69
#Sta/Elev= 30
  4357.1   30.15  4394.2   30.24  4429.8   29.65  4465.4   29.96  4511.7   29.39
  4536.7   28.87  4572.4   27.26  4643.6    27.2  4700.6   25.59  4772.5   23.93
  4809.2   24.12  4845.1   23.13  4893.1   23.16  4992.4   22.56  4992.9   21.56
  5007.1   21.56  5007.6   22.56  5031.8   22.98  5109.4   23.01  5169.6   23.44
  5190.9   23.85  5222.7   23.77  5254.5   24.05  5318.1   25.64    5350   26.96
  5381.8    27.8  5404.8   28.87  5445.4    29.8  5477.2   30.85  5535.2   30.75
#Mann= 4 ,-1,0
  4357.1     .12       0  4809.2    .135       0  4992.4     .05       0
  5007.6    .135       0
Bank Sta=4992.4,5007.6
XS Rating Curve= 0 ,0
Exp/Cntr=0.3,0.1

Type RM Length L Ch R = 1 ,8500    ,500,500,500
BEGIN DESCRIPTION:
Jenkins Swamp 17.0
END DESCRIPTION:
XS GIS Cut Line= 3
      2563634.63       728864.63      2563775.02       729357.84
      2563868.96       730047.07
#Sta/Elev= 30
  4487.2   27.55  4534.4   27.56  4560.6   26.99  4584.9   27.19  4609.2   25.97
  4633.5      26  4730.6   23.95  4752.7   23.16  4846.3   22.88  4877.5   22.44
  4992.4   22.43  4992.9   21.43  5007.1   21.43  5007.6   22.43  5153.6   23.08
  5183.8   22.64  5214.1    23.9  5237.3   23.19  5266.7   23.95  5317.2   26.56
  5335.2   27.17  5343.9   27.14  5378.7   28.02  5426.1   28.28  5450.4   29.06
  5477.1   28.66  5547.2   28.43  5607.7   28.73  5668.3   27.74  5695.6   28.23
#Mann= 4 ,-1,0
  4487.2     .12       0  4846.3    .135       0  4992.4     .05       0
  5007.6    .135       0
Bank Sta=4992.4,5007.6
XS Rating Curve= 0 ,0
Exp/Cntr=0.3,0.1

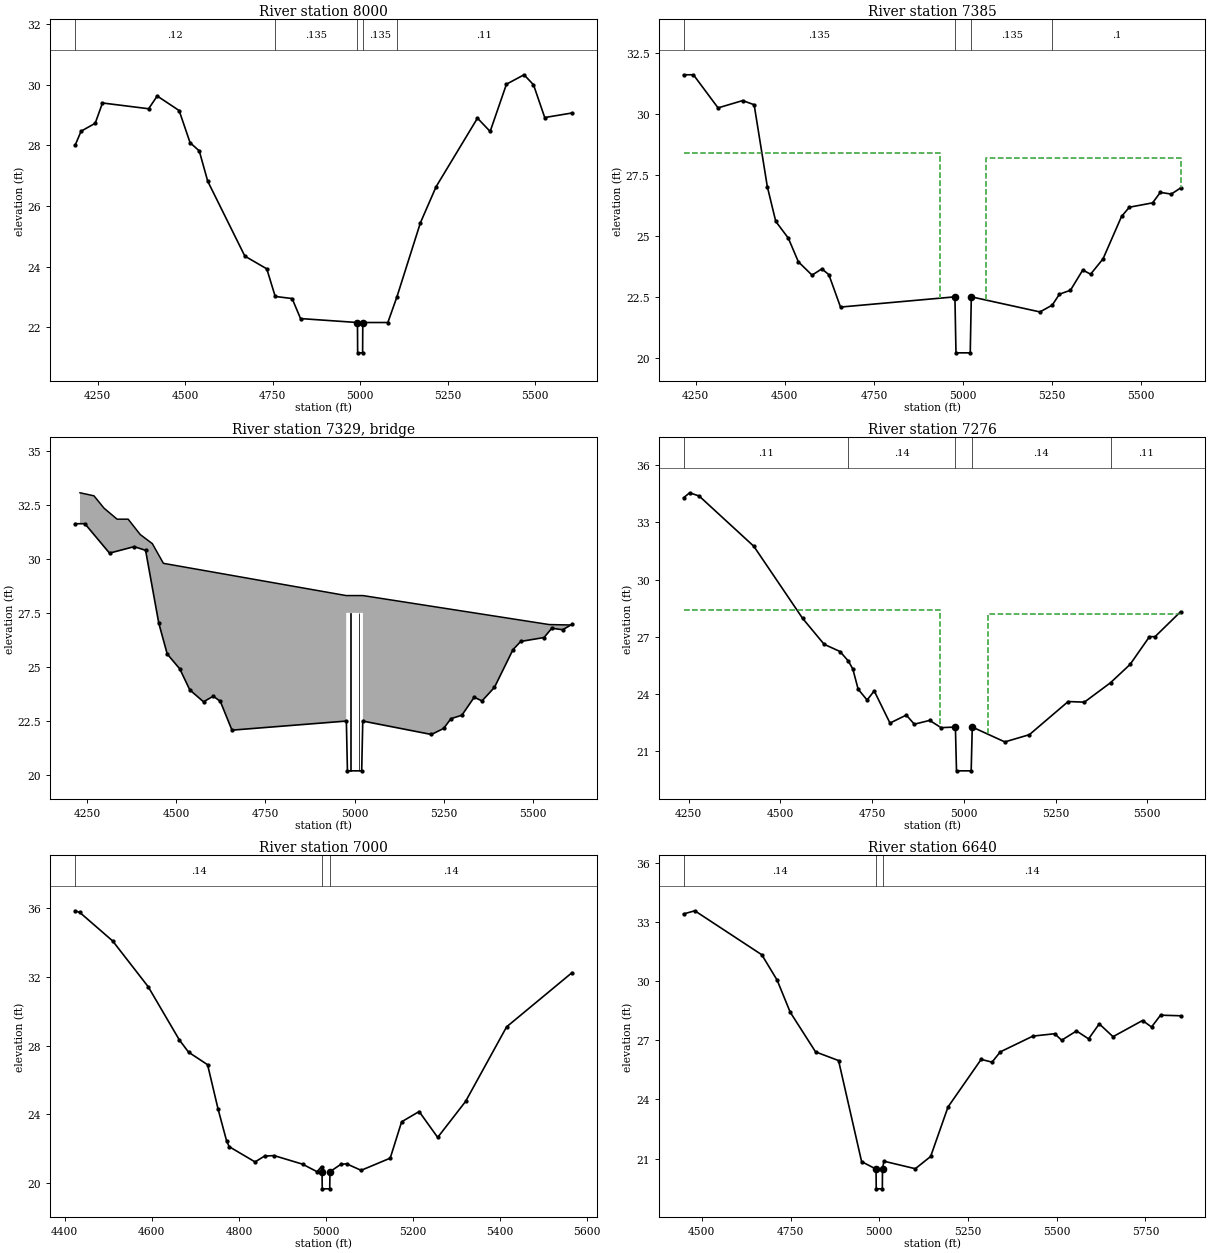
Type RM Length L Ch R = 1 ,8000    ,615,615,615
BEGIN DESCRIPTION:
Jenkins Swamp 16.0
END DESCRIPTION:
XS GIS Cut Line= 3
      2563073.65       728744.95      2563305.95       729525.83
      2563518.01       730093.09
#Sta/Elev= 30
  4185.3      28  4202.5   28.47  4242.8   28.73  4263.6    29.4  4395.5   29.21
  4420.1   29.63  4482.7   29.15    4514   28.09  4540.2   27.82  4564.4   26.82
  4670.5   24.35  4733.2   23.93  4757.3   23.02  4805.6   22.95  4829.7   22.29
  4992.4   22.16  4992.9   21.16  5007.1   21.16  5007.6   22.16  5079.2   22.16
    5105      23  5172.3   25.45  5217.2   26.64  5335.4    28.9  5371.6   28.46
  5418.2   30.02  5468.5   30.33  5495.5      30  5527.6   28.92  5605.6   29.07
#Mann= 5 ,-1,0
  4185.3     .12       0  4757.3    .135       0  4992.4     .05       0
  5007.6    .135       0    5105     .11       0
Bank Sta=4992.4,5007.6
XS Rating Curve= 0 ,0
Exp/Cntr=0.5,0.3

Type RM Length L Ch R = 1 ,7385    ,109,109,109
BEGIN DESCRIPTION:
Jenkins Swamp (SR-134) US
END DESCRIPTION:
XS GIS Cut Line= 3
      2562412.02       729186.12      2562800.34        729867.2
      2563123.82       730384.36
#Sta/Elev= 30
    4216   31.62  4243.5   31.62  4312.6   30.26  4381.6   30.56  4413.8   30.39
  4450.7   27.03  4474.4    25.6  4509.7   24.91  4537.8   23.94  4576.3   23.39
  4603.7   23.65  4623.4   23.41  4656.1   22.08    4977    22.5    4980    20.2
    5020    20.2    5023    22.5  5215.6   21.88    5250   22.16  5270.3   22.61
  5301.1   22.77  5335.6    23.6  5357.6   23.43  5392.5   24.06  5444.4    25.8
  5466.2   26.18  5531.5   26.36  5553.3   26.79  5583.9   26.72    5610   26.97
#Mann= 4 ,-1,0
    4216    .135       0    4977     .05       0    5023    .135       0
    5250      .1       0
#XS Ineff= 2 , 0
       0  4934.5   28.41  5065.5       0   28.19
Permanent Ineff=
       F       F
Bank Sta=4977,5023
XS Rating Curve= 0 ,0
Exp/Cntr=0.5,0.3

Type RM Length L Ch R = 3 ,7329    ,,,
BEGIN DESCRIPTION:
Jenkins Swamp (SR-134) TOR
Structure ID: LDS_JKS_01
Approximate Survey Structure
END DESCRIPTION:
Bridge Culvert--1,0,-1,-1, 0
Deck Dist Width WeirC Skew NumUp NumDn MinLoCord MaxHiCord MaxSubmerge Is_Ogee
42,28,3,0, 14, 14, , , 0.95, 0, 1,1,,
  4229.8    4269  4297.1  4333.9  4364.9  4398.8  4432.7  4463.8  4976.5  4976.5
  5023.5  5023.5  5546.1  5607.6
   33.05   32.91   32.34   31.83   31.83   31.12    30.7   29.79    28.3    28.3
    28.3    28.3   26.96   26.94
      .1      .1      .1      .1      .1      .1      .1      .1      .1    27.5
    27.5      .1      .1      .1
  4229.8    4269  4297.1  4333.9  4364.9  4398.8  4432.7  4463.8  4976.5  4976.5
  5023.5  5023.5  5546.1  5607.6
   33.05   32.91   32.34   31.83   31.83   31.12    30.7   29.79    28.3    28.3
    28.3    28.3   26.96   26.94
      .1      .1      .1      .1      .1      .1      .1      .1      .1    27.5
    27.5      .1      .1      .1
Pier Skew, UpSta & Num, DnSta & Num=  ,4988.3, 2 ,4988.3, 2 , 0 , 0 , 0 ,0,0
       1       1
    17.2    27.5
       1       1
   16.95    27.5
Pier Skew, UpSta & Num, DnSta & Num=  ,5011.8, 2 ,5011.8, 2 , 0 , 0 , 0 ,0,0
       1       1
    17.2    27.5
       1       1
   16.95    27.5
Abutment Skew #Up #Dn= , 2 , 2
  4976.5  4979.5
    27.5   17.75
  4976.5  4979.5
    27.5    17.5
Abutment Skew #Up #Dn= , 2 , 2
  5020.5  5023.5
   17.75    27.5
  5020.5  5023.5
    17.5    27.5
BR Coef= 1 , 1 , 0 ,1.25, 0 ,,,0.8,0,2,0,
WSPro=,,,, 1 ,,,, 0 ,,,, 0 ,,,,-1 ,-1 ,-1 , 0 , 0 , 0 , 0 , 0
BC Design=,, 0 ,, 0 ,,,,,,
BC HTab HWMax=31.67
BC Use User HTab Curves=0
BC User HTab FreeFlow(D)= 0

Type RM Length L Ch R = 1 ,7276    ,276,276,276
BEGIN DESCRIPTION:
Jenkins Swamp (SR-134) DS
END DESCRIPTION:
XS GIS Cut Line= 3
      2562313.94       729263.63      2562704.99       729920.09
      2562983.33       730441.44
#Sta/Elev= 30
  4235.9    34.3  4252.3   34.56  4278.2   34.39  4427.3   31.75  4560.4   27.96
    4619    26.6  4662.3   26.22    4685   25.72  4697.3    25.3  4711.8   24.24
  4736.2   23.67  4755.6   24.15  4798.6   22.46  4843.1   22.88    4865    22.4
  4906.8    22.6  4937.9   22.22    4977   22.25    4980   19.95    5020   19.95
    5023   22.25  5111.8   21.47  5178.7   21.85  5284.5   23.59  5328.8   23.56
    5400   24.58  5453.3   25.54  5506.2      27  5521.4      27    5591   28.31
#Mann= 5 ,-1,0
  4235.9     .11       0    4685     .14       0    4977     .05       0
    5023     .14       0    5400     .11       0
#XS Ineff= 2 , 0
       0    4935    28.4    5065       0   28.19
Permanent Ineff=
       F       F
Bank Sta=4977,5023
XS Rating Curve= 0 ,0
Exp/Cntr=0.5,0.3

Type RM Length L Ch R = 1 ,7000    ,360,360,360
BEGIN DESCRIPTION:
Jenkins Swamp 14.0
END DESCRIPTION:
XS GIS Cut Line= 3
      2562174.21       729577.07      2562476.71       730067.47
        2562725.         730575.
#Sta/Elev= 30
  4423.8   35.86  4434.8   35.76  4510.1    34.1  4591.7   31.43  4663.4   28.32
  4684.5   27.61  4728.1   26.88  4752.3   24.28  4771.7   22.44  4777.7    22.1
  4837.1   21.21  4858.9   21.55  4880.7   21.58  4946.1   21.08  4979.5   20.64
  4989.7   20.94  4990.9   20.64  4991.4   19.64  5008.6   19.64  5009.1   20.64
  5034.2   21.07  5047.3    21.1  5080.7   20.72  5147.5   21.43  5173.7   23.55
  5213.9   24.15  5256.5   22.64  5320.6   24.74  5414.8   29.09    5565   32.25
#Mann= 3 ,-1,0
  4423.8     .14       0  4990.9     .05       0  5009.1     .14       0
Bank Sta=4990.9,5009.1
XS Rating Curve= 0 ,0
Exp/Cntr=0.3,0.1

Type RM Length L Ch R = 1 ,6640    ,640,640,640
BEGIN DESCRIPTION:
Jenkins Swamp 13.0
END DESCRIPTION:
XS GIS Cut Line= 4
      2561862.41       729791.79      2562169.99       730249.19
      2562368.63       730545.04      2562469.87       731026.97
#Sta/Elev= 30
  4448.8    33.4  4480.3   33.56  4669.1   31.33  4712.4   30.04  4749.1   28.42
  4820.5   26.41  4885.3   25.97  4950.2   20.85  4990.9   20.47  4991.4   19.47
  5008.6   19.47  5009.1   20.47    5013   20.87  5101.5   20.49  5144.7   21.11
  5193.7   23.62    5287   26.03  5317.7   25.89  5340.9   26.41  5432.9   27.21
  5494.3   27.33  5513.7      27  5555.6   27.47  5589.7   27.07  5619.7   27.83
  5658.5   27.18  5741.7      28    5767   27.67  5792.4   28.27  5848.8   28.24
#Mann= 3 ,-1,0
  4448.8     .14       0  4990.9     .05       0  5009.1     .14       0
Bank Sta=4990.9,5009.1
XS Rating Curve= 0 ,0
Exp/Cntr=0.3,0.1