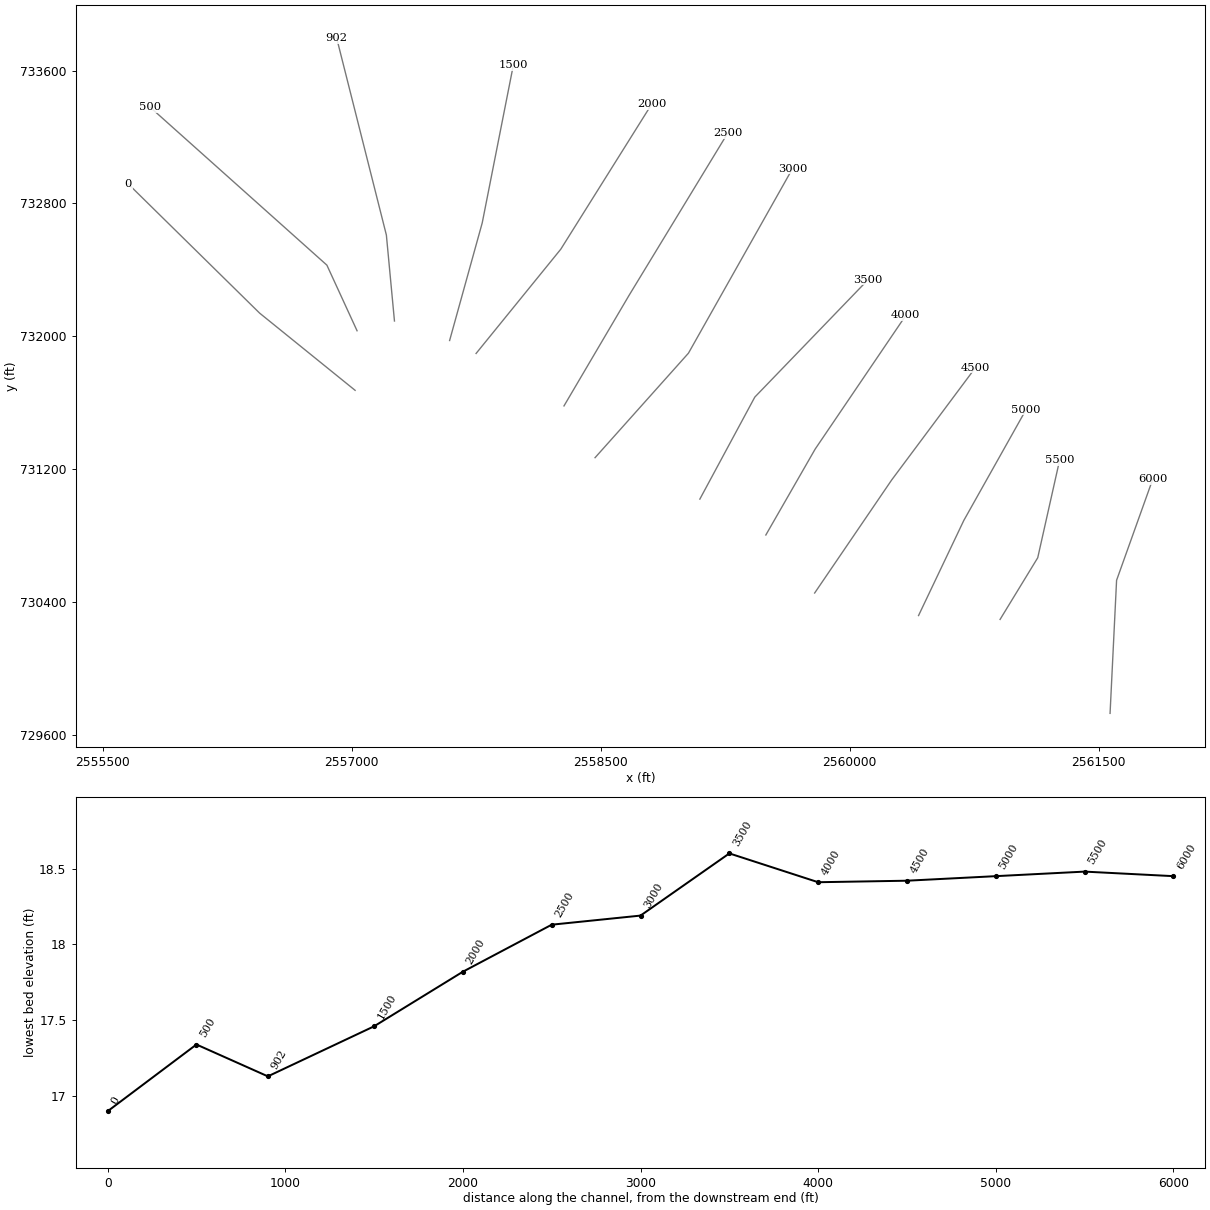
HEC-RAS study JenkinsSwamp.prj: S-26-134 over Jenkins Swamp

--- JenkinsSwamp.g05 (geometry) --- (continued)

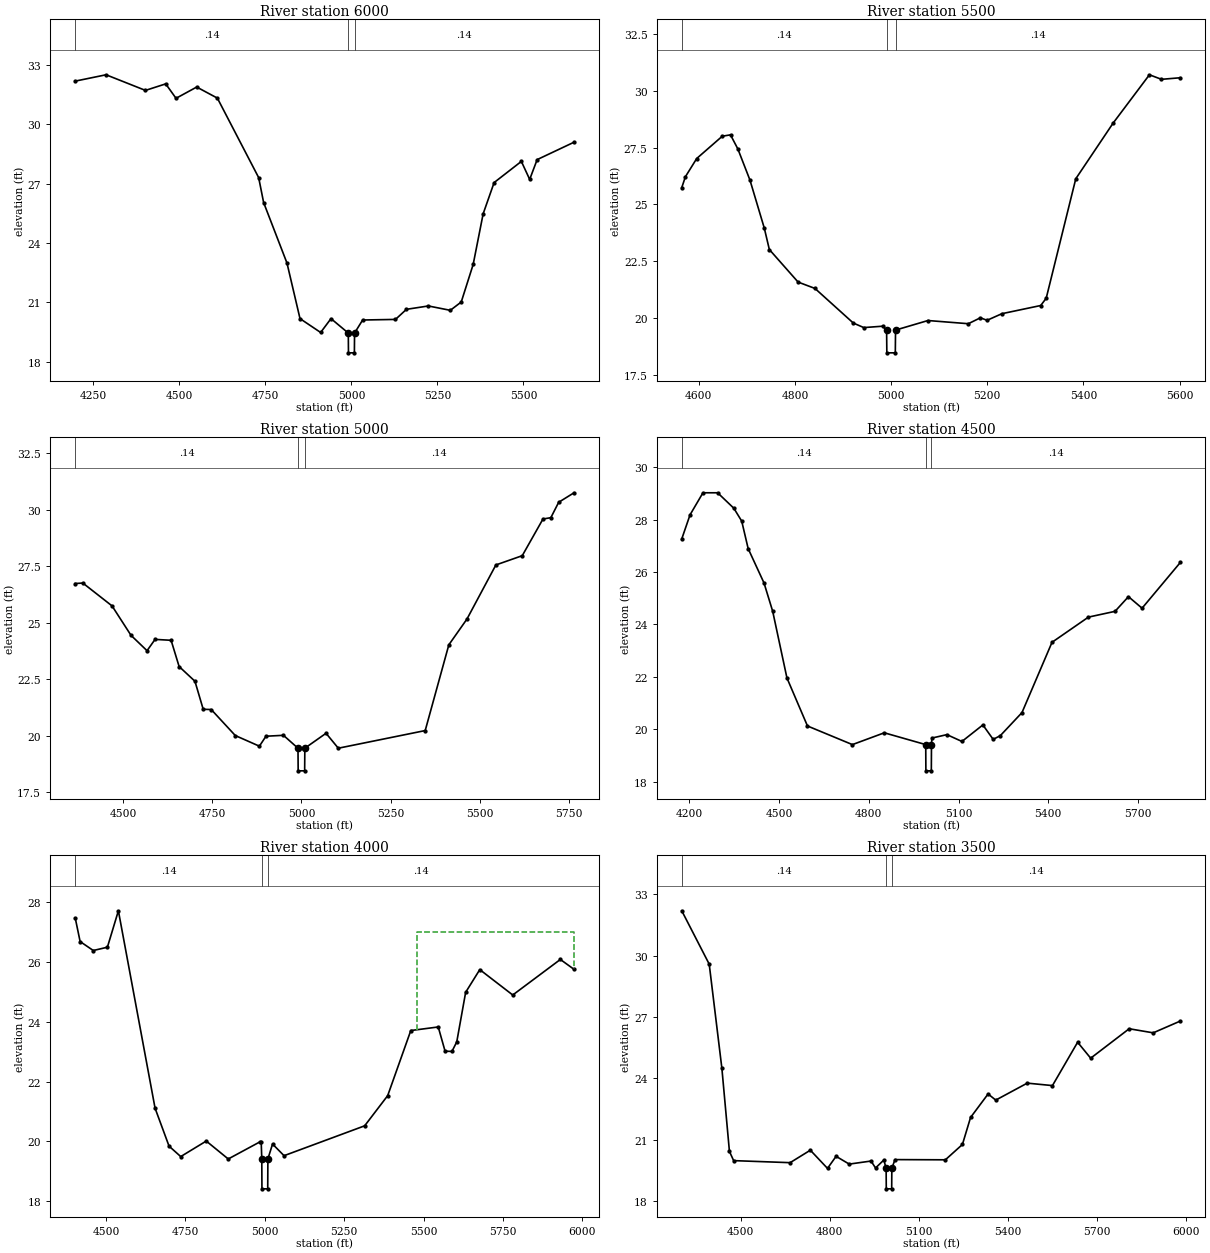
Type RM Length L Ch R = 1 ,6000    ,500,500,500
BEGIN DESCRIPTION:
Jenkins Swamp 12.0
END DESCRIPTION:
XS GIS Cut Line= 3
      2561568.81       729727.41      2561608.09       730529.35
      2561826.13       731138.72
#Sta/Elev= 30
  4197.1   32.19  4286.6   32.51  4401.1   31.72    4460   32.05    4490   31.32
  4550.1   31.89  4610.2   31.33  4730.3   27.31  4744.7   26.05  4812.6   22.99
  4850.5   20.18  4910.5   19.48  4940.6   20.18  4990.9   19.45  4991.4   18.45
  5008.6   18.45  5009.1   19.45  5032.6   20.11  5128.1   20.14    5160   20.65
  5223.7   20.82  5287.5    20.6  5319.3   21.02    5354   22.92    5383   25.48
  5414.9   27.06  5494.1   28.13  5518.3   27.22    5540   28.22  5647.2    29.1
#Mann= 3 ,-1,0
  4197.1     .14       0  4990.9     .05       0  5009.1     .14       0
Bank Sta=4990.9,5009.1
XS Rating Curve= 0 ,0
Exp/Cntr=0.3,0.1

Type RM Length L Ch R = 1 ,5500    ,500,500,500
BEGIN DESCRIPTION:
Jenkins Swamp 11.0
END DESCRIPTION:
XS GIS Cut Line= 3
      2560906.07       730293.49      2561132.95        730665.1
      2561264.72        731252.5
#Sta/Elev= 30
  4564.6   25.74  4572.2   26.22  4595.7   27.02  4648.9      28    4666   28.06
  4681.3   27.44  4706.5   26.07  4736.3   23.96  4746.8   23.02  4806.6   21.59
  4841.7   21.31  4921.4   19.79  4943.2   19.59  4982.3   19.65  4990.7   19.48
  4991.2   18.48  5008.8   18.48  5009.3   19.48  5076.8    19.9  5160.7   19.76
  5185.8   20.02  5199.7   19.91  5230.5    20.2  5311.3   20.56  5322.7   20.88
  5384.2   26.13    5462   28.58  5537.4    30.7  5562.5    30.5    5602   30.57
#Mann= 3 ,-1,0
  4564.6     .14       0  4990.7     .05       0  5009.3     .14       0
Bank Sta=4990.7,5009.3
XS Rating Curve= 0 ,0
Exp/Cntr=0.3,0.1

Type RM Length L Ch R = 1 ,5000    ,500,500,500
BEGIN DESCRIPTION:
Jenkins Swamp 10.0
END DESCRIPTION:
XS GIS Cut Line= 3
      2560414.85       730316.89      2560687.43       730889.74
      2561061.97       731556.56
#Sta/Elev= 30
  4365.6   26.73  4386.8   26.75  4468.7   25.74  4521.9   24.44  4566.9   23.76
  4589.4   24.26  4634.4   24.22  4656.9   23.06  4701.3   22.41  4724.5   21.17
    4747   21.16  4814.5   20.01  4882.1   19.54  4900.6   19.98  4949.6   20.02
  4990.4   19.45  4990.9   18.45  5009.1   18.45  5009.6   19.45  5069.1   20.11
  5103.5   19.45  5347.3   20.23  5413.6   24.02  5464.5   25.16  5545.6   27.55
  5619.6   27.96  5677.7   29.58  5699.8   29.64  5721.8   30.32  5764.8   30.74
#Mann= 3 ,-1,0
  4365.6     .14       0  4990.4     .05       0  5009.6     .14       0
Bank Sta=4990.4,5009.6
XS Rating Curve= 0 ,0
Exp/Cntr=0.3,0.1

Type RM Length L Ch R = 1 ,4500    ,500,500,500
BEGIN DESCRIPTION:
Jenkins Swamp 9.0
END DESCRIPTION:
XS GIS Cut Line= 3
      2559788.82        730452.7      2560253.39       731134.58
      2560756.75       731809.43
#Sta/Elev= 30
  4174.9   27.26  4202.6   28.18  4245.8   29.02  4294.8   29.02    4349   28.43
  4375.3   27.94  4396.9   26.89  4449.9   25.58  4478.9    24.5  4526.5   21.96
  4595.1   20.13  4745.3   19.42  4851.9   19.87  4990.4   19.42  4990.9   18.42
  5009.1   18.42  5009.6   19.42  5011.1   19.67  5061.2    19.8  5111.4   19.54
  5181.4   20.17  5215.8   19.62  5239.6   19.76  5312.1   20.64  5412.5   23.32
  5534.2   24.28  5623.1    24.5    5668   25.06  5713.5   24.62  5841.9   26.37
#Mann= 3 ,-1,0
  4174.9     .14       0  4990.4     .05       0  5009.6     .14       0
Bank Sta=4990.4,5009.6
XS Rating Curve= 0 ,0
Exp/Cntr=0.3,0.1

Type RM Length L Ch R = 1 ,4000    ,500,500,500
BEGIN DESCRIPTION:
Jenkins Swamp 8.0
END DESCRIPTION:
XS GIS Cut Line= 3
       2559494.7       730802.32      2559791.83       731319.89
      2560338.27       732125.56
#Sta/Elev= 30
  4403.2   27.47  4418.4   26.69  4459.8   26.39  4504.3    26.5  4538.9   27.72
  4654.4   21.11  4698.4   19.84  4735.2   19.49  4815.6   20.01  4884.8   19.41
  4984.1   19.98  4988.6   19.97  4990.4   19.41  4990.9   18.41  5009.1   18.41
  5009.6   19.41  5024.3   19.91  5060.5   19.52  5314.3   20.52  5386.8   21.53
  5459.6   23.71    5546   23.83  5567.5   23.02  5589.1   23.01  5604.3   23.33
  5632.3   24.99  5676.8   25.75  5780.6    24.9  5930.5   26.09  5973.5   25.76
#Mann= 3 ,-1,0
  4403.2     .14       0  4990.4     .05       0  5009.6     .14       0
#XS Ineff= 2 , 0
       0                    5480       0      27
Permanent Ineff=
       F       F
Bank Sta=4990.4,5009.6
XS Rating Curve= 0 ,0
Exp/Cntr=0.3,0.1

Type RM Length L Ch R = 1 ,3500    ,500,500,500
BEGIN DESCRIPTION:
Jenkins Swamp 7.0
END DESCRIPTION:
XS GIS Cut Line= 3
      2559097.11       731018.58       2559428.2       731633.17
      2560109.99       732339.92
#Sta/Elev= 30
  4301.9    32.2  4394.4   29.59  4437.1   24.49  4462.5   20.43  4476.7   19.98
    4667   19.88  4735.1   20.49  4792.9    19.6  4821.8   20.19  4866.1   19.81
  4939.6   19.96  4954.7   19.62  4982.7   20.01  4990.4    19.6  4990.9    18.6
  5009.1    18.6  5009.6    19.6  5020.2   20.03    5190   20.02  5247.4   20.77
  5274.8   22.09  5333.9   23.24  5359.7   22.94  5465.8   23.77  5550.7   23.65
  5635.5   25.77  5679.5   24.99  5809.2   26.43  5890.1   26.23    5982   26.81
#Mann= 3 ,-1,0
  4301.9     .14       0  4990.4     .05       0  5009.6     .14       0
Bank Sta=4990.4,5009.6
XS Rating Curve= 0 ,0
Exp/Cntr=0.3,0.1

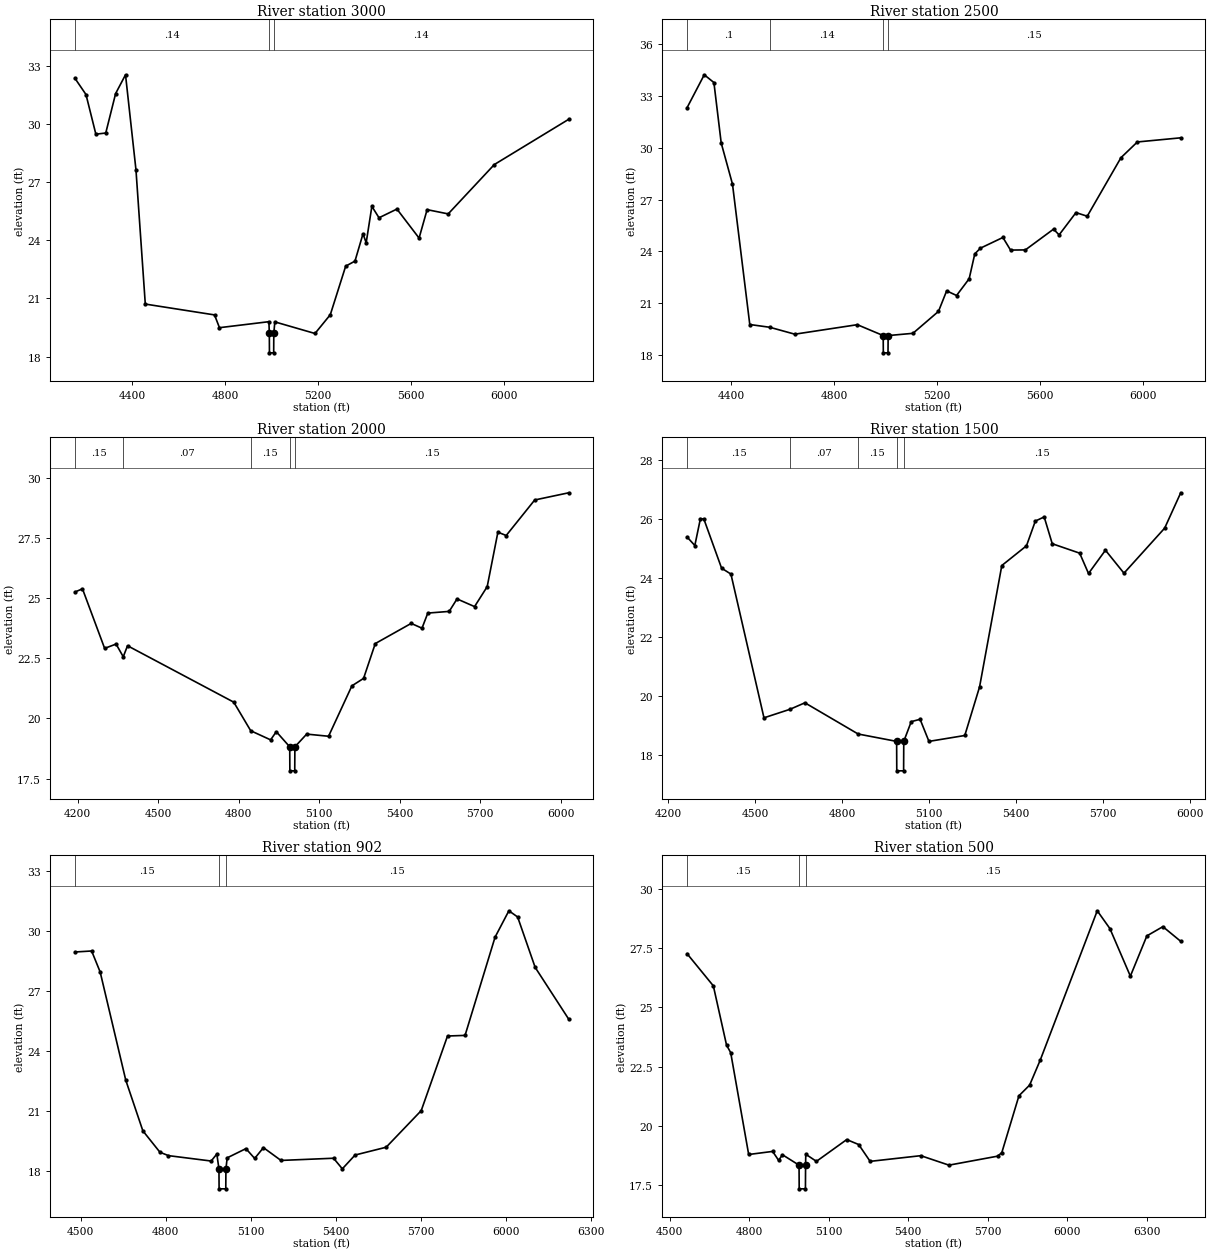
Type RM Length L Ch R = 1 ,3000    ,500,500,500
BEGIN DESCRIPTION:
Jenkins Swamp 6.0
END DESCRIPTION:
XS GIS Cut Line= 3
      2558465.56       731268.12      2559028.34       731897.77
      2559655.48       733010.17
#Sta/Elev= 30
  4155.5   32.37  4202.5   31.54    4245   29.49  4287.5   29.55  4329.9   31.59
  4372.4   32.56  4417.3   27.65  4457.4   20.71  4754.9   20.15  4776.1   19.49
  4988.6    19.8  4990.4   19.19  4990.9   18.19  5009.1   18.19  5009.6   19.19
    5014   19.79  5186.6   19.19  5252.4   20.16  5318.5   22.67  5358.4   22.93
  5392.9   24.34  5406.6   23.88    5431   25.76  5461.7   25.17  5538.7   25.62
  5633.9   24.12  5668.4   25.59    5759   25.37  5957.2   27.92    6277   30.26
#Mann= 3 ,-1,0
  4155.5     .14       0  4990.4     .05       0  5009.6     .14       0
Bank Sta=4990.4,5009.6
XS Rating Curve= 0 ,0
Exp/Cntr=0.3,0.1

Type RM Length L Ch R = 1 ,2500    ,500,500,500
BEGIN DESCRIPTION:
Jenkins Swamp 5.0
END DESCRIPTION:
XS GIS Cut Line= 3
      2558278.41       731579.98      2558669.65       732244.81
      2559265.11       733223.85
#Sta/Elev= 30
  4228.6   32.32  4295.5   34.23    4333   33.78  4361.3   30.28  4405.1    27.9
  4472.3   19.77    4550   19.61  4647.1   19.21    4890   19.76  4990.4   19.13
  4990.9   18.13  5009.1   18.13  5009.6   19.13  5105.9   19.26  5205.1   20.53
  5236.9   21.72  5275.3   21.45  5324.3   22.42  5346.1   23.86  5367.9   24.19
  5455.3   24.81  5484.9   24.08  5542.6   24.09  5651.8   25.29  5673.6   24.96
  5739.1   26.25  5782.8   26.04  5913.8   29.43  5977.5   30.34  6145.9   30.58
#Mann= 4 ,-1,0
  4228.6      .1       0    4550     .14       0  4990.4     .05       0
  5009.6     .15       0
Bank Sta=4990.4,5009.6
XS Rating Curve= 0 ,0
Exp/Cntr=0.3,0.1

Type RM Length L Ch R = 1 ,2000    ,500,500,500
BEGIN DESCRIPTION:
Jenkins Swamp 4.0
END DESCRIPTION:
XS GIS Cut Line= 3
      2557748.77       731896.08      2558259.27       732524.57
       2558806.4       733397.48
#Sta/Elev= 30
  4190.3   25.27    4218    25.4  4300.6   22.92  4343.2    23.1    4370   22.57
  4385.9   23.03  4781.8   20.68    4845   19.49  4919.1   19.11  4940.4   19.45
  4990.4   18.82  4990.9   17.82  5009.1   17.82  5009.6   18.82  5053.6   19.35
  5135.1   19.26  5222.1   21.36  5265.6   21.67  5309.2   23.12  5443.1   23.96
  5483.3   23.76    5505   24.39  5584.7   24.46  5613.9   24.98  5679.2   24.66
  5726.3   25.49  5766.2   27.76  5797.1   27.62  5903.4    29.1  6030.2    29.4
#Mann= 5 ,-1,0
  4190.3     .15       0    4370     .07       0    4845     .15       0
  4990.4     .05       0  5009.6     .15       0
Bank Sta=4990.4,5009.6
XS Rating Curve= 0 ,0
Exp/Cntr=0.3,0.1

Type RM Length L Ch R = 1 ,1500    ,598,598,598
BEGIN DESCRIPTION:
Jenkins Swamp 3.0
END DESCRIPTION:
XS GIS Cut Line= 3
      2557589.24       731974.08      2557785.69       732682.65
      2557972.97       733632.05
#Sta/Elev= 30
  4264.7    25.4  4291.6   25.11  4310.8   26.02  4322.7   26.01  4383.9   24.34
  4416.1   24.14  4530.1   19.26    4620   19.55  4671.3   19.77    4855   18.71
  4987.7   18.46  4988.2   17.46  5011.8   17.46  5012.3   18.46  5038.1   19.13
  5068.6   19.21  5099.2   18.46  5222.8   18.66  5273.8   20.31  5350.5   24.43
  5435.6    25.1  5466.2   25.94  5496.7   26.08  5524.5   25.17  5619.1   24.85
  5649.6   24.16    5708   24.95  5771.9   24.17  5912.3    25.7  5967.7    26.9
#Mann= 5 ,-1,0
  4264.7     .15       0    4620     .07       0    4855     .15       0
  4987.7     .05       0  5012.3     .15       0
Bank Sta=4987.7,5012.3
XS Rating Curve= 0 ,0
Exp/Cntr=0.3,0.1

Type RM Length L Ch R = 1 ,902     ,402,402,402
BEGIN DESCRIPTION:
Jenkins Swamp 2.0
END DESCRIPTION:
XS GIS Cut Line= 3
      2557256.91       732091.65      2557208.17       732609.66
      2556909.05        733794.9
#Sta/Elev= 30
  4479.7   28.97  4538.3   29.02  4568.4   27.97  4658.8   22.56  4719.1   20.03
  4779.4   18.96  4809.5   18.79  4960.2   18.52  4980.2   18.87  4987.7   18.13
  4988.2   17.13  5011.8   17.13  5012.3   18.13  5016.8   18.68  5082.9   19.14
  5113.8   18.65  5144.7   19.19  5206.6   18.55  5392.3   18.66  5423.2   18.13
  5468.2   18.82  5577.9   19.21  5701.7   21.04  5794.5   24.77  5856.4    24.8
  5962.3   29.71  6011.1   31.03    6042   30.72  6103.9    28.2  6222.4   25.61
#Mann= 3 ,-1,0
  4479.7     .15       0  4987.7     .05       0  5012.3     .15       0
Bank Sta=4987.7,5012.3
XS Rating Curve= 0 ,0
Exp/Cntr=0.3,0.1

Type RM Length L Ch R = 1 ,500     ,500,500,500
BEGIN DESCRIPTION:
Jenkins Swamp 1.0
END DESCRIPTION:
XS GIS Cut Line= 3
       2557031.5       732032.91      2556849.74       732428.22
      2555784.73       733379.96
#Sta/Elev= 30
  4564.9   27.27  4664.2   25.91    4714   23.41  4729.7   23.09  4797.6   18.79
    4888   18.92  4910.7   18.54  4924.9   18.78  4987.7   18.34  4988.2   17.34
  5011.8   17.34  5012.3   18.34  5013.1    18.8  5053.3    18.5  5167.7   19.42
  5212.8   19.21    5256    18.5  5447.2   18.74  5553.5   18.34  5737.3   18.72
    5753   18.87  5817.7   21.27    5858   21.72  5898.2   22.78  6113.2   29.08
  6160.9   28.33  6238.2   26.32  6300.5   28.02  6360.9   28.41  6428.3   27.79
#Mann= 3 ,-1,0
  4564.9     .15       0  4987.7     .05       0  5012.3     .15       0
Bank Sta=4987.7,5012.3
XS Rating Curve= 0 ,0
Exp/Cntr=0.3,0.1

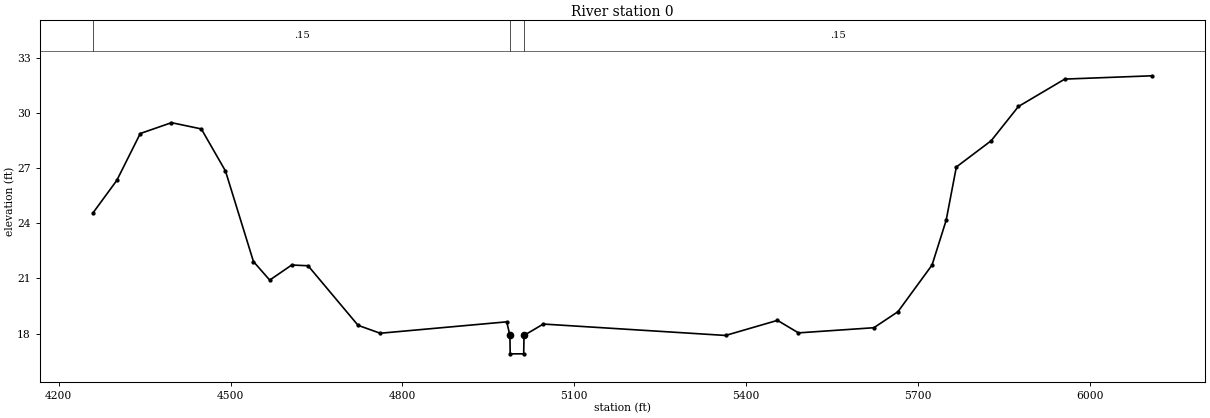
Type RM Length L Ch R = 1 ,0       ,0,0,0
BEGIN DESCRIPTION:
Jenkins Swamp 0.0
END DESCRIPTION:
XS GIS Cut Line= 3
      2557019.79       731673.95      2556444.28       732139.28
      2555653.21       732917.37
#Sta/Elev= 30
  4259.9   24.57  4301.3   26.33  4342.3   28.88  4396.8   29.47  4448.9   29.13
  4491.1   26.84  4539.9   21.92  4568.3   20.91  4606.8   21.73  4635.3   21.69
  4722.6   18.45  4761.2   18.02  4982.2   18.64  4987.7    17.9  4988.2    16.9
  5011.8    16.9  5012.3    17.9    5046   18.52  5364.2    17.9  5454.9   18.72
  5491.5   18.04  5623.2   18.32  5665.2   19.19  5724.8   21.73  5749.4   24.16
  5767.2   27.06  5828.1   28.49  5875.6   30.35  5956.5   31.84  6109.6   32.02
#Mann= 3 ,-1,0
  4259.9     .15       0  4987.7     .05       0  5012.3     .15       0
#XS Ineff= 2 , 0
       0  4606.8   21.73               0
Permanent Ineff=
       F       F
Bank Sta=4987.7,5012.3
XS Rating Curve= 0 ,0
Exp/Cntr=0.3,0.1
LCMann Table=0

Chan Stop Cuts=-1
Use User Specified Reach Order=0
User Specified Reach Order=Jenkins Swamp   ,Reach-1
Composite Channel Slope=5