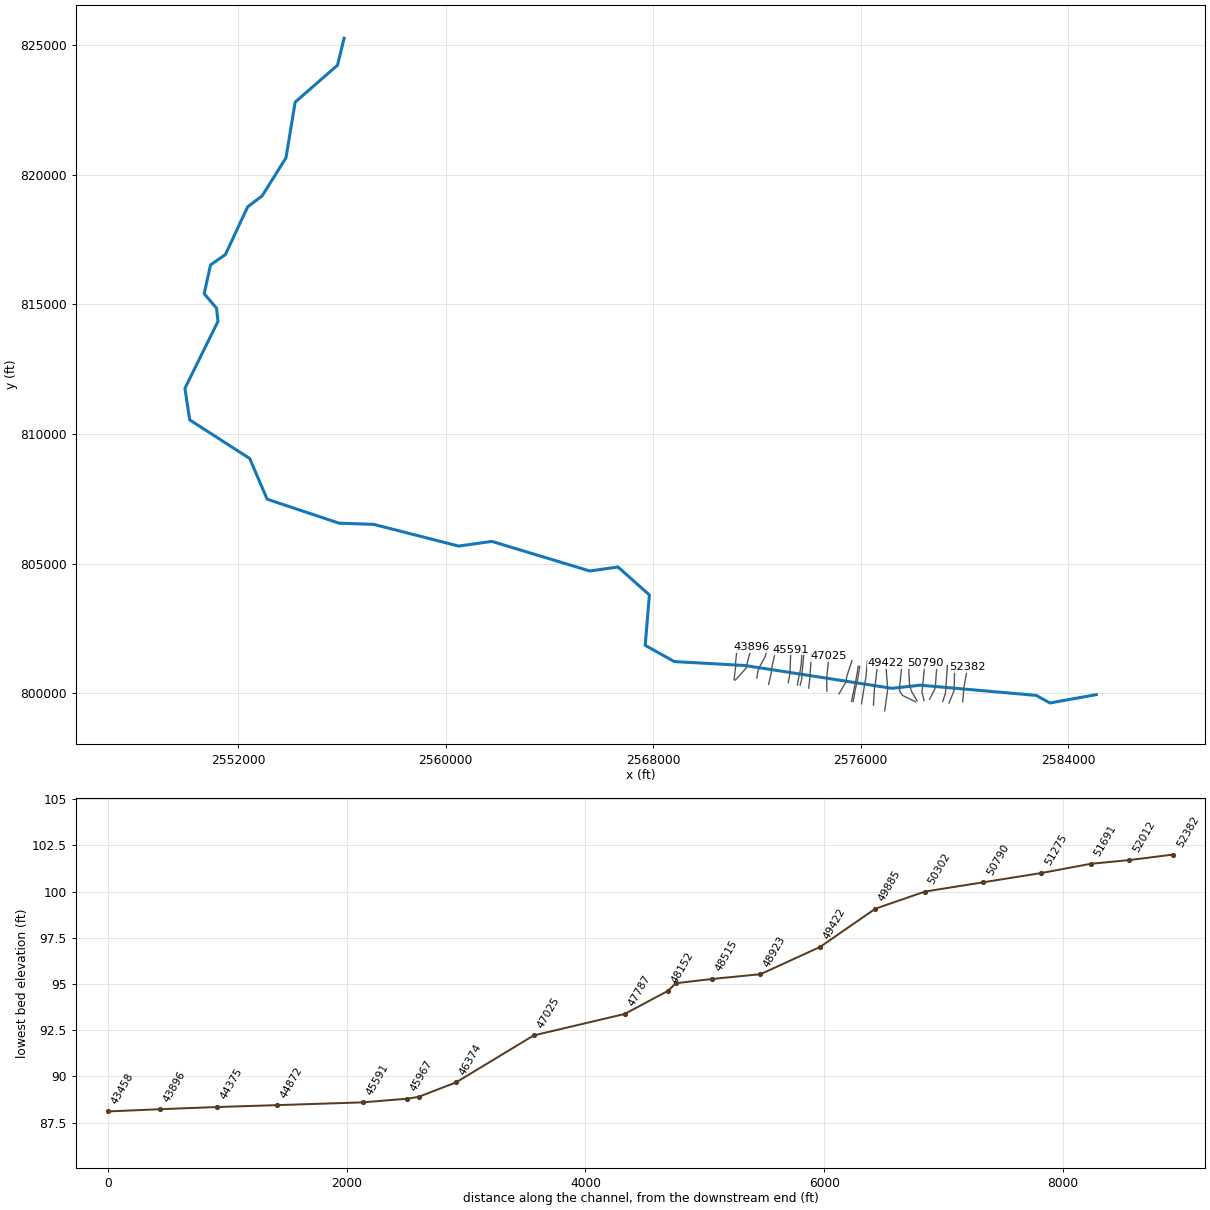
--- LousingSwamp.prj (project) ---

Proj Title=S-26-569 over Lousing Swamp
Current Plan=p03
Default Exp/Contr=0.3,0.1
English Units
Geom File=g02
Geom File=g04
Geom File=g06
Flow File=f01
Flow File=f02
Flow File=f03
Plan File=p02
Plan File=p03
Plan File=p04
Plan File=p06
Y Axis Title=Elevation
X Axis Title(PF)=Main Channel Distance
X Axis Title(XS)=Station
BEGIN DESCRIPTION:
END DESCRIPTION:
DSS Export Rating Curves= 0
DSS Export Rating Curve Sorted= 0
DSS Export Volume Flow Curves= 0
DXF OffsetX= 0
DXF OffsetY= 0
DXF ScaleX= 1
DXF ScaleY= 10

--- LousingSwamp.p03 (plan) ---

Plan Title=Sensitivity Analysis
Program Version=6.60
Short Identifier=EX SA
Geom File=g02
Flow File=f03
Subcritical Flow
K Sum by GR= 0
Std Step Tol= 0.01
Critical Tol= 0.01
Num of Std Step Trials= 20
Max Error Tol= 0.3
Flow Tol Ratio= 0.001
Split Flow NTrial= 30
Split Flow Tol= 0.02
Split Flow Ratio= 0.02
Log Output Level= 0
Friction Slope Method= 1
Unsteady Friction Slope Method= 2
Unsteady Bridges Friction Slope Method= 1
Parabolic Critical Depth
Global Vel Dist= 1 , 1 , 1
Global Log Level= 0
CheckData=True
Encroach Param=-1 ,0,0, 0
Flow Ratio Tolerance=0.1
Flow Ratio Min Ratio=0.5
Flow Ratio Max Ratio=4
Flow Ratio Max Iterations= 10
Computation Interval=1HOUR
Output Interval=1HOUR
Instantaneous Interval=1HOUR
Mapping Interval=1HOUR
Computation Time Step Use Courant=        0
Computation Time Step Use Time Series=    0
Computation Time Step Count To Double=0
Computation Time Step Max Doubling=0
Computation Time Step Max Halving=0
Computation Time Step Residence Courant=0
Run HTab= 0
Run UNet= 0
Run Sediment= 0
Run PostProcess= 0
Run WQNet= 0
Run RASMapper= 0
UNET Theta= 1
UNET Theta Warmup= 1
UNET ZTol= 0.02
UNET ZSATol= 0.05
UNET MxIter= 20
UNET Max Iter WO Improvement= 0
UNET MaxInSteps= 0
UNET DtIC= 0
UNET DtMin= 0
UNET MaxCRTS= 20
UNET WFStab= 2
UNET SFStab= 1
UNET WFX= 1
UNET SFX= 1
UNET Gravity=32.17405
UNET 1D Methodology=Finite Difference
UNET DSS MLevel= 4
UNET Pardiso=0
UNET DZMax Abort= 100
UNET Use Existing IB Tables=-1
UNET Froude Reduction=False
UNET Froude Limit= 1
UNET Froude Power= 10
UNET D1 Cores= 0
UNET WindReference=Eulerian
UNET WindDragFormulation=Hsu (1988)
UNET D2 Coriolis=0
UNET D2 Cores= 0
UNET D2 Theta= 1
UNET D2 Theta Warmup= 1
UNET D2 Z Tol= 0.01
UNET D2 Volume Tol= 0.01
UNET D2 Max Iterations= 20
UNET D2 Advanced Convergence=0
UNET D2 WS Max Tol=0.15
UNET D2 WS RMS Tol=0.002
UNET D2 WS Stall Tol=1
UNET D2 Equation= 0
UNET D2 RampUpFraction=0.1
UNET D2 TimeSlices= 1
UNET D2 Turbulence Formulation=Non-Conservative (original)
UNET D2 Eddy Viscosity=0.3
UNET D2 Transverse Eddy Viscosity=0.1
UNET D2 Smagorinsky Mixing=0
UNET D2 BCVolumeCheck=0
UNET D2 Cores=0
UNET D2 SolverType=PARDISO (Direct)
UNET D2 Minimum Iterations= 3
UNET D2 Maximum Iterations= 30
UNET D2 Restart Number= 10
UNET D2 Relaxation Coeff=1.3
UNET D2 SOR Precondition Iterations= 10
UNET D2 ILUT Maximum Fill= 8
UNET D2 ILUT Tolerance=1E-08
UNET D2 Convergence Tolerance=0.00001
PS Theta= 1
PS WS Tol= 0.01
PS Volume Tol= 0.01
PS Max Iterations= 20
PS Equation= 0
PS Advance Time Step=-1
PS Target Courant=0.9
PS Time Slices= 1
PS Iterate With 2D=0
PS Project Initial WSE from DS=-1
PS Ramp Up Initial WSE from US=-1
PS Cores=0
UNET D1D2 MaxIter= 0
UNET D1D2 ZTol=0.01
UNET D1D2 QTol=0.1
UNET D1D2 MinQTol=1
Write IC File= 0
Write IC File at Fixed DateTime=0
Write IC File at Sim End=0
Echo Input=False
Echo Parameters=False
Echo Output=False
Write Detailed= 0
HDF Write Warmup=0
HDF Write Time Slices=0
HDF Flush=0
HDF Compression= 1
HDF Chunk Size= 1
HDF Spatial Parts= 1
HDF Use Max Rows=0
HDF Fixed Rows= 1
Calibration Method= 0
Calibration Iterations= 20
Calibration Max Change=0.05
Calibration Tolerance=0.2
Calibration Maximum=1.5
Calibration Minimum=0.5
Calibration Optimization Method= 1
WQ AD Non Conservative
WQ ULTIMATE=-1
WQ Max Comp Step=1HOUR
WQ Output Interval=15MIN
WQ Output Selected Increments= 0
WQ Create Restart=0
WQ Fixed Restart=0
WQ System Summary=0
WQ Write To DSS=0
Sorting and Armoring Iterations= 10
XS Update Threshold= 0.02
Bed Roughness Predictor= 0
Processes Affected by Predictor=Sediment Only
Hydraulics Update Threshold= 0.02
Energy Slope Method= 1
Volume Change Method= 1
Sediment Retention Method= 0
Sediment TS Multiplier= 1
Warm Up Method= 0
XS Weighting Method= 0
Number of US Weighted Cross Sections= 1
Number of DS Weighted Cross Sections= 1
Upstream XS Weight=0
Main XS Weight=1
Downstream XS Weight=0
Number of DS XS's Weighted with US Boundary= 1
Upstream Boundary Weight= 1
Weight of XSs Associated with US Boundary= 0
Number of US XS's Weighted with DS Boundary= 1
Downstream Boundary Weight= 0.5
Weight of XSs Associated with DS Boundary= 0.5
Percentile Method= 0
Sediment Output Level= 3
Mass or Volume Output= 0
Output Increment Type= 1
Profile and TS Output Increment= 1
Transport Output Increment 1
XS Output Flag= 0
XS Output Increment= 10
Read HDF5 Sediment Hotstart= 0
Sediment Hotstart Type= 0
Write Gradation File= 0
Read Gradation Hotstart= 0
Write HDF5 File= 1
Write Binary Output= 1
Write DSS Sediment File= 0
DSS Sediment Output Type= 1
SV Curve= 0
Specific Gage Flag= 0
Subcell Erosion Methods= 0
Subcell Deposition Methods= 0
Advection Scheme= 1
Matrix Solver= 0
Implicit Weighting Factor= 1
Maximum Outer Loop Convergence Iterations= 5
Convergence Maximum Absolute= 0.001
Convergence RMSE= 0.0001
Grain Fractions Max Abs Error= 0.001
Max Subgrid Regions= 1
Max Subgrid Length Scale= 3.402823E+38
Initial Layer Thickness= 3
Min Layer Thickness= 0.1
Max Layer Thickness= 6
Number of Layers= 5

--- LousingSwamp.p02 (plan) ---

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Plan Title=Existing
Short Identifier=EX
Geom File=g02
Flow File=f02

--- LousingSwamp.p04 (plan) ---

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Plan Title=Natural
Short Identifier=NAT
Geom File=g04
Flow File=f02

--- LousingSwamp.p06 (plan) ---

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Plan Title=Proposed
Short Identifier=PROP
Geom File=g06
Flow File=f02

--- LousingSwamp.f03 (steady flow) ---

Flow Title=Sensitivity
Program Version=6.60
Number of Profiles= 3
Profile Names=100yr - 3ft,100yr,100yr + 3ft
River Rch & RM=Lousing Swamp,Reach-1         ,52382
     544     544     544
Boundary for River Rch & Prof#=Lousing Swamp,Reach-1         , 1
Up Type= 0
Dn Type= 1
Dn Known WS=85.96
Boundary for River Rch & Prof#=Lousing Swamp,Reach-1         , 2
Up Type= 0
Dn Type= 1
Dn Known WS=88.96
Boundary for River Rch & Prof#=Lousing Swamp,Reach-1         , 3
Up Type= 0
Dn Type= 1
Dn Known WS=91.96
DSS Import GetInterval= 0
DSS Import GetPeak= 0
DSS Import FillOption= 0

--- LousingSwamp.f01 (steady flow) ---

Flow Title=FEMA 100-year Flows
Program Version=6.60
Number of Profiles= 1
Profile Names=100-year
River Rch & RM=Loosing Swamp,Reach-1         ,39000
     683
River Rch & RM=Loosing Swamp,Reach-1         ,38500
     705
River Rch & RM=Loosing Swamp,Reach-1         ,37500
     886
River Rch & RM=Loosing Swamp,Reach-1         ,31500
     938
River Rch & RM=Loosing Swamp,Reach-1         ,27500
     977
River Rch & RM=Loosing Swamp,Reach-1         ,25500
    1027
River Rch & RM=Loosing Swamp,Reach-1         ,23500
    1069
River Rch & RM=Loosing Swamp,Reach-1         ,20000
    1111
River Rch & RM=Loosing Swamp,Reach-1         ,16000
    1140
River Rch & RM=Loosing Swamp,Reach-1         ,14000
    1183
River Rch & RM=Loosing Swamp,Reach-1         ,12500
    1219
River Rch & RM=Loosing Swamp,Reach-1         ,10000
    1249
River Rch & RM=Loosing Swamp,Reach-1         ,8500
    1296
River Rch & RM=Loosing Swamp,Reach-1         ,7500
    1338
River Rch & RM=Loosing Swamp,Reach-1         ,5481
    1362
River Rch & RM=Loosing Swamp,Reach-1         ,3500
    1402
River Rch & RM=Loosing Swamp,Reach-1         ,2500
    1416
Boundary for River Rch & Prof#=Loosing Swamp,Reach-1         , 1
Up Type= 0
Dn Type= 3
Dn Slope=0.001
DSS Import GetInterval= 0
DSS Import GetPeak= 0
DSS Import FillOption= 0

--- LousingSwamp.f02 (steady flow) ---

Flow Title=USGS Flows
Program Version=6.60
Number of Profiles= 6
Profile Names=2yr,10yr,25yr,50yr,100yr,500yr
River Rch & RM=Lousing Swamp,Reach-1         ,52382
      84     239     345     443     544     803
Boundary for River Rch & Prof#=Lousing Swamp,Reach-1         , 1
Up Type= 0
Dn Type= 3
Dn Slope=0.0015
Boundary for River Rch & Prof#=Lousing Swamp,Reach-1         , 2
Up Type= 0
Dn Type= 3
Dn Slope=0.0015
Boundary for River Rch & Prof#=Lousing Swamp,Reach-1         , 3
Up Type= 0
Dn Type= 3
Dn Slope=0.0015
Boundary for River Rch & Prof#=Lousing Swamp,Reach-1         , 4
Up Type= 0
Dn Type= 3
Dn Slope=0.0015
Boundary for River Rch & Prof#=Lousing Swamp,Reach-1         , 5
Up Type= 0
Dn Type= 3
Dn Slope=0.0015
Boundary for River Rch & Prof#=Lousing Swamp,Reach-1         , 6
Up Type= 0
Dn Type= 3
Dn Slope=0.0015
DSS Import GetInterval= 0
DSS Import GetPeak= 0
DSS Import FillOption= 0

--- LousingSwamp.g02 (geometry) ---

Geom Title=Existing
Program Version=6.60

River Reach=Lousing Swamp   ,Reach-1
Reach XY= 30
2585084.23259006799946.4784178442583296.30840018799625.477053412
2582765.87778423799916.9389281472578303.79917506800311.347073613
2577203.94304398800190.3628991952571538.24856171801070.250908649
2568818.80734377801221.396577731      2567696.25       801847.69
      2567857.12       803791.61      2566645.39       804868.97
      2565559.99        804715.2      2561783.47        805855.7
      2560503.18       805675.95      2557231.77       806512.24
      2555894.04       806558.99      2553120.77       807484.86
       2552449.9       809053.17      2550138.02       810541.17
      2549952.17       811757.99      2551226.94       814341.98
      2551171.27       814849.27      2550695.42       815406.44
      2550939.61       816518.49      2551512.23         816917.
      2552371.15        818757.5      2552930.61       819181.54
      2553848.27       820649.65      2554203.06       822797.91
      2555834.44       824219.49      2556089.52       825260.57

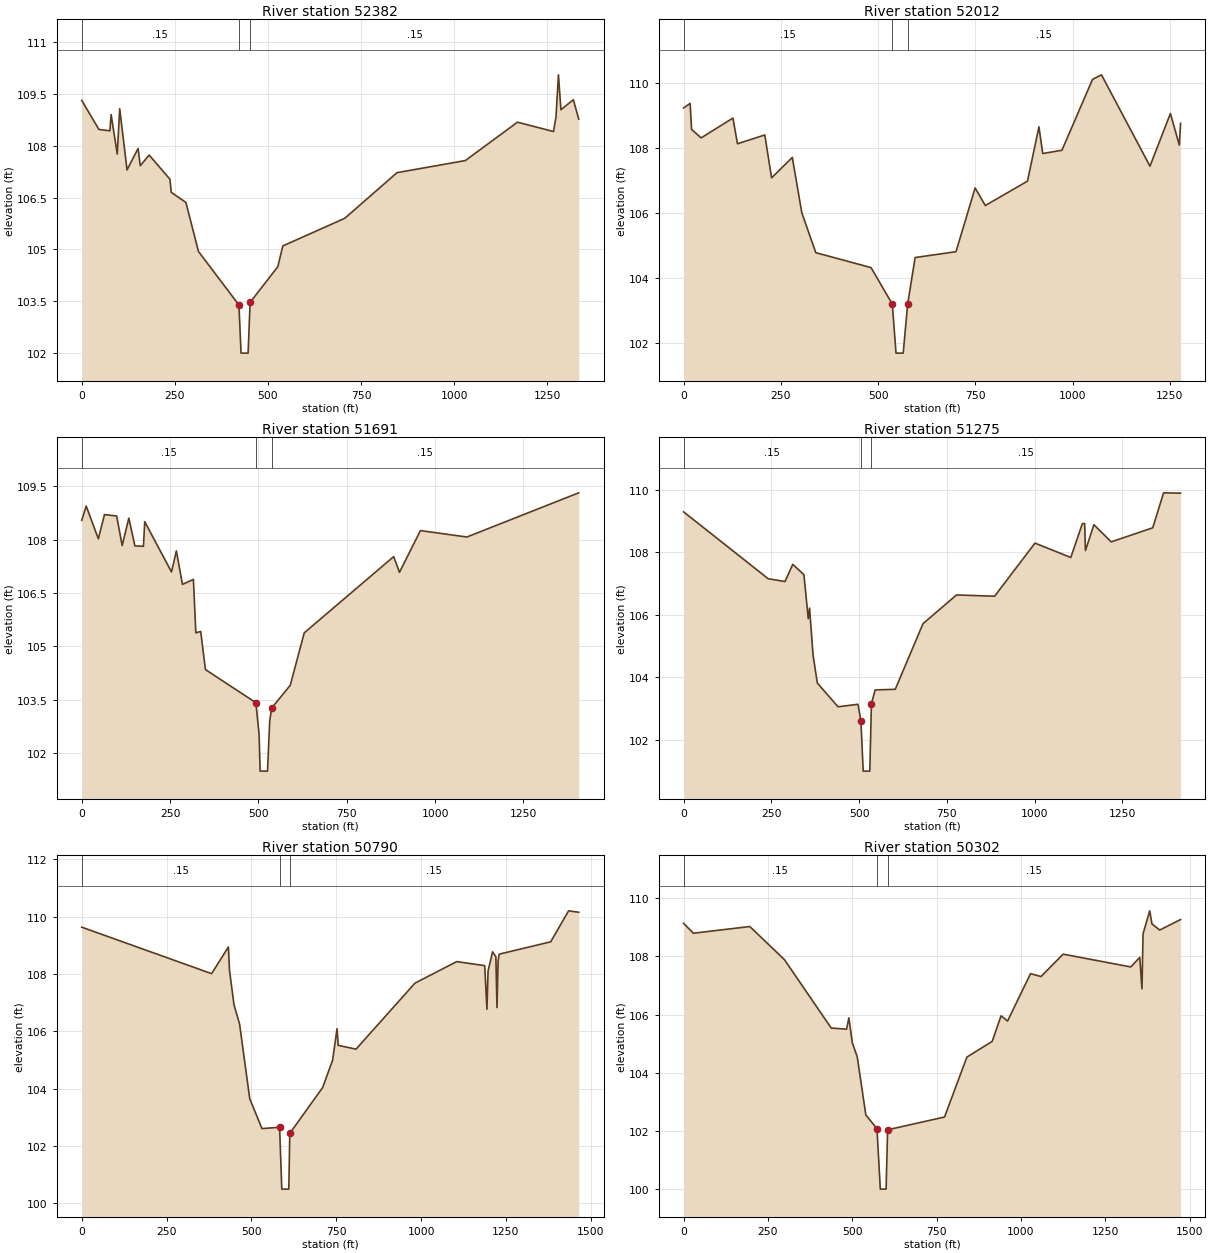
Type RM Length L Ch R = 1 ,52382   ,370,370,370
XS GIS Cut Line= 4
 2579934.7176695799674.2983325732579968.15329852800075.525880821
2579974.05370364800189.6003798332580119.59702997800994.022278035
#Sta/Elev= 30
       0  109.31      46  108.47    75.5  108.43    78.8   108.9    95.3  107.76
   101.9  109.07   121.6   107.3   151.2  107.92   157.1  107.42   180.9  107.73
   236.8  107.03   240.4  106.65   279.6  106.36   313.4  104.94     422 103.393
   427.7     102  446.63     102     452 103.467   526.4   104.5   539.8   105.1
   706.2   105.9   846.5  107.22  1029.9  107.57  1169.9  108.68  1266.6  108.41
  1273.3  108.83  1279.9  110.05  1286.6  109.04  1319.9  109.331334.328  108.77
#Mann= 3 ,0,0
       0     .15       0     422     .05       0     452     .15       0
Bank Sta=422,452
XS Rating Curve= 0 ,0
Exp/Cntr(USF)=0,0
Exp/Cntr=0.3,0.1

Type RM Length L Ch R = 1 ,52012   ,320.8,320.8,320.8
XS GIS Cut Line= 4
2579405.56623259799622.5661716962579598.50948006800088.108135766
 2579605.5899662800224.4074940682579621.52106003800861.651247167
#Sta/Elev= 30
       0  109.24    16.7  109.38    20.5  108.58    45.1  108.32   126.8  108.93
   138.5  108.14   208.8  108.41   226.2  107.09   279.5  107.72   303.9  106.02
   339.9  104.79     482  104.33   536.6  103.21  546.18   101.7  564.65   101.7
     576 103.197   595.3  104.64   700.4  104.82   749.6  106.78   775.8  106.24
   884.2  106.99   913.7  108.66   923.5  107.84   972.8  107.94  1051.5  110.12
  1074.5  110.26  1199.2  107.45  1251.7  109.07  1274.7   108.11277.867  108.77
#Mann= 3 ,0,0
       0     .15       0   536.6     .05       0     576     .15       0
Bank Sta=536.6,576
XS Rating Curve= 0 ,0
Exp/Cntr(USF)=0,0
Exp/Cntr=0.3,0.1

Type RM Length L Ch R = 1 ,51691   ,415.4,415.4,415.4
XS GIS Cut Line= 3
2579165.11232858799678.5869376572579270.70947957800004.178153197
2579344.04083442801066.016171445
#Sta/Elev= 30
       0  108.54    12.5  108.94      47  108.02    64.3   108.7    98.8  108.66
   114.4  107.83   133.2   108.6   150.5  107.82   174.6  107.81   178.2   108.5
     254  107.09   267.8  107.68     285  106.74     316  106.88   322.9  105.38
   336.7  105.42   350.1  104.35   492.9  103.42     502 102.521  504.84   101.5
  525.79   101.5     532 102.906   537.6  103.27   590.2  103.91   629.7  105.38
   882.9  107.52   899.4  107.08   958.6  108.25  1090.1  108.071406.654  109.31
#Mann= 3 ,0,0
       0     .15       0   492.9     .05       0   537.6     .15       0
Bank Sta=492.9,537.6
XS Rating Curve= 0 ,0
Exp/Cntr(USF)=0,0
Exp/Cntr=0.3,0.1

Type RM Length L Ch R = 1 ,51275   ,485.7,485.7,485.7
XS GIS Cut Line= 4
2578658.57494423799771.2563807532578860.36879938800165.993483367
2578883.38037936800309.3733278142578943.56451159 801134.24996377
#Sta/Elev= 30
       0   109.3   240.9  107.16   288.8  107.07   310.9  107.62   342.7  107.29
   355.1  105.88   358.8  106.22   368.7  104.72   380.9  103.82   439.9  103.06
   496.7  103.14     505 102.614  511.62     101  530.39     101     535 103.154
   545.6   103.6   602.9  103.62   681.9  105.72   777.3  106.64   885.9   106.6
  1000.9   108.3  1102.9  107.84  1135.8  108.92  1142.4  108.93  1144.7  108.06
  1168.7  108.89  1218.1  108.34  1336.3  108.79  1367.3  109.91 1415.61   109.9
#Mann= 3 ,0,0
       0     .15       0     505     .05       0     535     .15       0
Bank Sta=505,535
XS Rating Curve= 0 ,0
Exp/Cntr(USF)=0,0
Exp/Cntr=0.3,0.1

Type RM Length L Ch R = 1 ,50790   ,487.4,487.4,487.4
XS GIS Cut Line= 4
2578445.30812784799718.6649704712578363.06625226800043.063479718
2578408.75618314800463.4108438132578477.29107946801167.035779363
#Sta/Elev= 30
       0  109.63   382.6  108.01   432.1  108.94   435.4  108.12   448.6  106.93
   465.1  106.25     495  103.65   531.1  102.61     583 102.656  589.46   100.5
  610.11   100.5     613 102.443   709.8  104.04   739.1  104.99   752.3  106.09
   755.6  105.51   808.3  105.38   981.9  107.68    1105  108.43  1187.4  108.29
    1194  106.77  1197.3   108.1  1210.5  108.77  1220.3   108.6  1223.6  106.83
  1226.9  108.45  1230.2  108.69  1381.9  109.12  1434.6   110.21464.439  110.15
#Mann= 3 ,0,0
       0     .15       0     583     .05       0     613     .15       0
Bank Sta=583,613
XS Rating Curve= 0 ,0
Exp/Cntr(USF)=0,0
Exp/Cntr=0.3,0.1

Type RM Length L Ch R = 1 ,50302   ,416.8,416.8,416.8
XS GIS Cut Line= 5
2578176.60566518799704.9862254042577959.54485482800074.576253854
2577889.14675417800309.2365893792577856.88095803800825.489327532
2577880.34699158801107.081730161
#Sta/Elev= 30
       0  109.14    28.9   108.8   196.3  109.03     299  107.89   437.6  105.54
   483.2   105.5     490  105.89   500.3  105.03   514.8  104.55   540.3  102.55
   573.3  102.08  583.21     100  600.36     100  604.85  102.04   773.6  102.48
   839.9  104.54   914.9  105.08   941.2  105.96   960.5  105.78  1028.6  107.41
  1059.6  107.31  1125.3  108.08    1326  107.64  1352.4  107.97    1359  106.89
  1362.2  108.78    1382  109.57  1388.6  109.12  1411.6  108.911473.438  109.27
#Mann= 3 ,0,0
       0     .15       0   573.3     .05       0  604.85     .15       0
Bank Sta=573.3,604.85
XS Rating Curve= 0 ,0
Exp/Cntr(USF)=0,0
Exp/Cntr=0.3,0.1

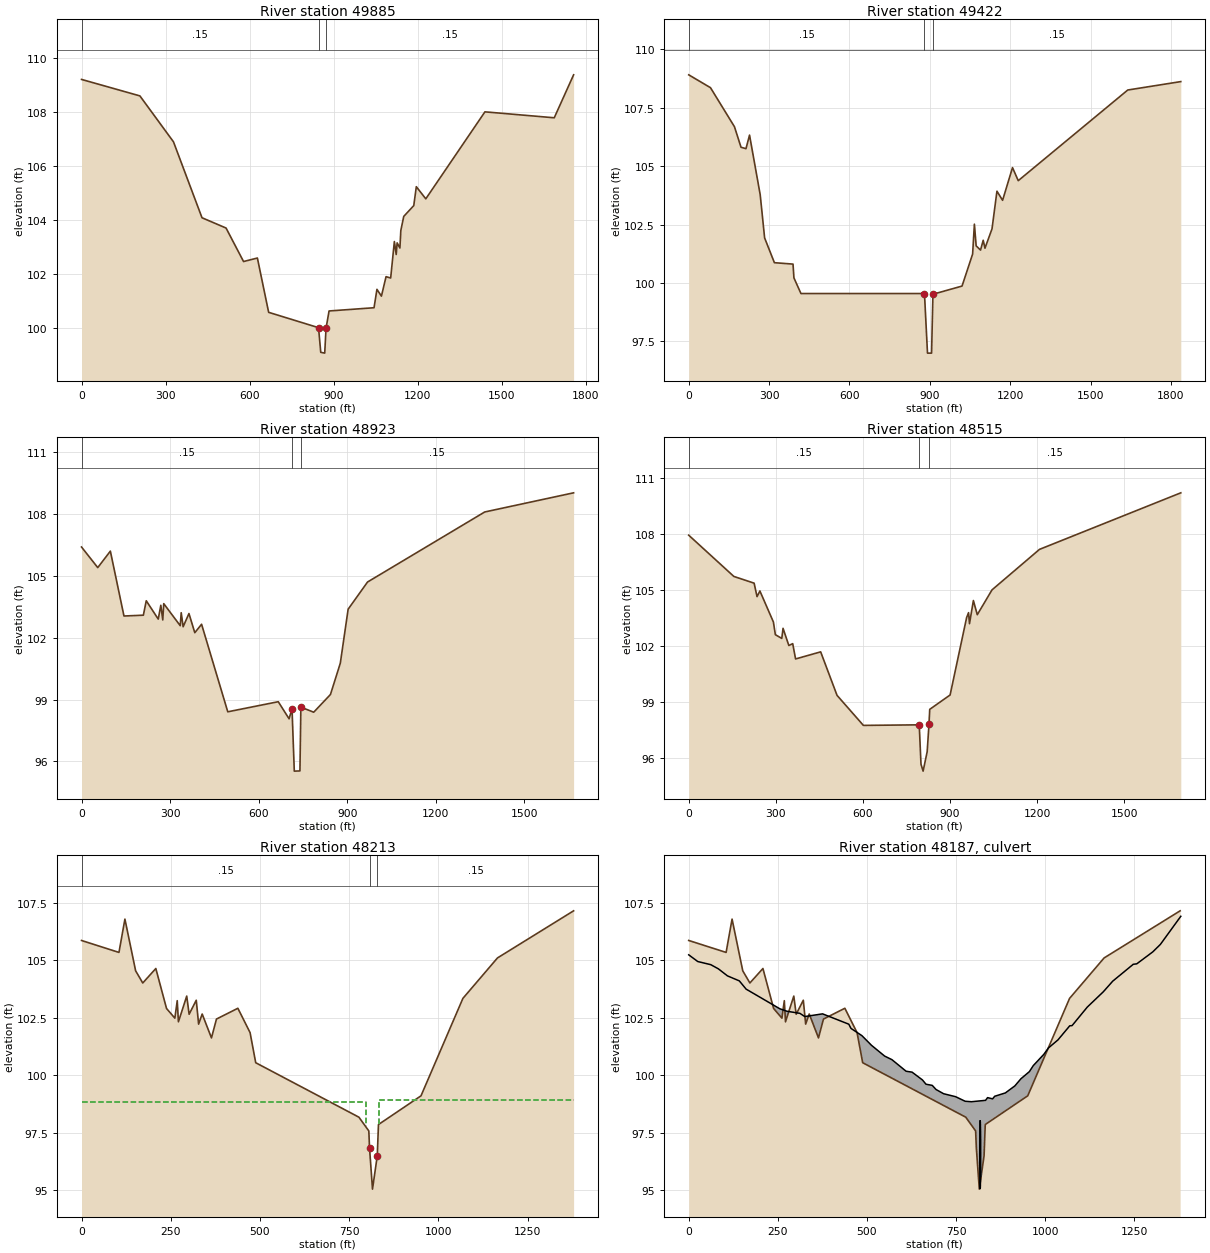
Type RM Length L Ch R = 1 ,49885   ,463.7,463.7,463.7
XS GIS Cut Line= 5
2578120.77564799799667.277842573 2577609.6036421799919.970419074
2577497.07177351 800094.462455342577509.21252479 800295.99892656
2577588.76686838801068.252473047
#Sta/Elev= 30
       0   109.2  208.35  108.59   328.2  106.89  429.98  104.08  515.77   103.7
  578.25  102.46  627.61  102.59  667.82  100.58  845.84 100.012  853.74    99.1
  867.89   99.07  872.61   99.99  883.41  100.63 1043.88  100.75 1054.27  101.43
 1070.27  101.18 1086.76   101.9 1103.25  101.85 1116.44   103.2 1123.04  102.72
 1126.34  103.15 1136.23  102.96 1139.53  103.61 1149.95  104.13 1185.71  104.53
 1194.81  105.23 1228.58  104.78 1439.67     108 1687.03  107.78 1756.09  109.37
#Mann= 3 ,0,0
       0     .15       0  845.84     .05       0  872.61     .15       0
Bank Sta=845.84,872.61
XS Rating Curve= 0 ,0
Exp/Cntr(USF)=0,0
Exp/Cntr=0.3,0.1

Type RM Length L Ch R = 1 ,49422   ,498.5,498.5,498.5
XS GIS Cut Line= 4
2576927.89300054799321.3469865832577035.72322493800089.606154828
2577040.57952544800201.3010665892576968.59694004801147.778890952
#Sta/Elev= 30
       0  108.91    81.2  108.36   170.7  106.69   195.2  105.81   213.7  105.75
     227  106.33   266.8  103.78   283.3  101.93   319.8  100.87   389.3  100.81
   392.7  100.22   418.9   99.55     880   99.55  891.25      97  906.47      97
  911.55   99.52  1020.2   99.87  1059.7  101.24  1066.3  102.52  1072.9  101.59
  1089.3  101.41  1099.2  101.83  1105.8  101.49  1132.1  102.32  1150.5  103.93
  1171.6  103.54  1208.6  104.94    1230  104.38  1638.8  108.26  1836.8  108.62
#Mann= 3 ,0,0
       0     .15       0     880     .05       0  911.55     .15       0
Bank Sta=880,911.55
XS Rating Curve= 0 ,0
Exp/Cntr(USF)=0,0
Exp/Cntr=0.3,0.1

Type RM Length L Ch R = 1 ,48923   ,407.8,407.8,407.8
XS GIS Cut Line= 4
 2576493.8857581799540.428731568 2576532.4121741 800199.60021121
2576572.55853055800416.1037763262576662.25682737801197.292646699
#Sta/Elev= 30
       0  106.41      55  105.41    97.7  106.21   143.8  103.06   209.5   103.1
   219.3   103.8   259.9  102.91   268.6  103.58   275.2  102.87   278.5  103.66
   334.4  102.59   337.7  103.22   344.2  102.54   363.9  103.18   383.7  102.25
   406.7  102.66   495.4   98.41   666.4    98.9   703.1   98.07     713  98.566
   720.7   95.53  739.84   95.54     743  98.638   786.5   98.39   843.2   99.25
   876.6  100.77   903.1  103.39   968.8  104.71  1365.7  108.11  1666.8  109.04
#Mann= 3 ,0,0
       0     .15       0     713     .05       0     743     .15       0
Bank Sta=713,743
XS Rating Curve= 0 ,0
Exp/Cntr(USF)=0,0
Exp/Cntr=0.3,0.1

Type RM Length L Ch R = 1 ,48515   ,302.2,302.2,302.2
XS GIS Cut Line= 4
2576034.61651612799595.9149189372576155.32318321800360.185636991
2576201.20473343800595.3285818852576261.95946361801274.430333686
#Sta/Elev= 30
       0  107.91   155.5   105.7   225.3  105.34   235.3  104.62   245.2  104.92
   291.7  103.26   298.4  102.58   320.6  102.38   324.9  102.92   344.9     102
   358.2   102.1   368.1  101.28   454.5  101.66   510.9   99.33   601.7   97.72
  794.03   97.75   800.1   95.64   807.4   95.27   821.4   96.31   827.6   97.77
   830.2   98.58   900.4   99.35   957.2  103.49   963.9  103.76   967.2  103.17
   980.6  104.41     994  103.65  1044.7  104.98  1208.3  107.15  1695.1  110.18
#Mann= 3 ,0,0
       0     .15       0  794.03     .05       0   827.6     .15       0
Bank Sta=794.03,827.6
XS Rating Curve= 0 ,0
Exp/Cntr(USF)=0,0
Exp/Cntr=0.3,0.1

Type RM Length L Ch R = 1 ,48213   ,61.4,61.4,61.4
XS GIS Cut Line= 5
  2575711.899665799679.0291890522575797.41067299800163.309353121
2575860.90894625800415.6091588762575903.24112842800638.276437111
 2575965.0461144801033.659018614
#Sta/Elev= 30
       0  105.86   104.9  105.34   121.6  106.79   151.6  104.54   171.6  104.01
   208.2  104.64   238.2   102.9   261.5  102.48   268.2  103.24   271.5  102.32
   294.8  103.44   301.5  102.65   321.5  103.26   328.1  102.22   338.1  102.66
   364.1  101.62   378.1  102.44   438.1  102.91   472.3  101.85   488.1  100.54
  777.28   98.17     805  97.571     807  96.827   815.3   95.04   828.7   96.49
     832   97.85  951.21    99.1  1068.6  103.34  1165.5   105.11378.779  107.15
#Mann= 3 ,0,0
       0     .15       0     807     .05       0   828.7     .15       0
#XS Ineff= 2 , 0
           795.8   98.84   834.8            98.9
Permanent Ineff=
       F       F
Bank Sta=807,828.7
XS Rating Curve= 0 ,0
Exp/Cntr(USF)=0,0
Exp/Cntr=0.3,0.1

Type RM Length L Ch R = 2 ,48187   ,,,
BEGIN DESCRIPTION:
Culvert geometry assumed, need to field verify
END DESCRIPTION:
Bridge Culvert--1,0,-1,-1, 0
Deck Dist Width WeirC Skew NumUp NumDn MinLoCord MaxHiCord MaxSubmerge Is_Ogee
17.95996,22,2.6,0, 50, 50, , , 0.98, 0, 2,2,,
       0  25.214  61.917  83.213 108.629 141.995 160.965  255.44 275.459 312.162
 325.508 375.557 449.082 455.308 485.887 512.757 549.654 570.227 609.887  626.63
 655.741  665.74 683.237 693.988 715.046 748.716 775.758 793.519 832.899 838.524
 852.588 858.475  888.45 914.911 932.087 955.804 966.766 996.2461009.4781035.895
1069.0231075.6391118.1341163.087 1189.641247.2571257.1631302.0441323.3221380.679
 105.236 104.944 104.807 104.625  104.32 104.101 103.743 102.889 102.781 102.688
 102.549 102.667 102.217 102.033 101.719 101.299  100.83 100.673  100.17 100.131
  99.792  99.605  99.555  99.375  99.192  99.063  98.863  98.844  98.904  99.022
  98.969  99.081  99.227  99.531  99.843 100.154 100.416 100.904 101.186 101.532
 102.147 102.156 102.959 103.625 104.089 104.824 104.844 105.364 105.688 106.913
                                                                                
                                                                                
                                                                                
                                                                                
                                                                                
       0  25.214  61.917  83.213 108.629 141.995 160.965  255.44 275.459 312.162
 325.508 375.557 449.082 455.308 485.887 512.757 549.654 570.227 609.887  626.63
 655.741  665.74 683.237 693.988 715.046 748.716 775.758 793.519 832.899 838.524
 852.588 858.475  888.45 914.911 932.087 955.804 966.766 996.2461009.4781035.895
1069.0231075.6391118.1341163.087 1189.641247.2571257.1631302.0441323.3221380.679
 105.236 104.944 104.807 104.625  104.32 104.101 103.743 102.889 102.781 102.688
 102.549 102.667 102.217 102.033 101.719 101.299  100.83 100.673  100.17 100.131
  99.792  99.605  99.555  99.375  99.192  99.063  98.863  98.844  98.904  99.022
  98.969  99.081  99.227  99.531  99.843 100.154 100.416 100.904 101.186 101.532
 102.147 102.156 102.959 103.625 104.089 104.824 104.844 105.364 105.688 106.913
                                                                                
                                                                                
                                                                                
                                                                                
                                                                                
BR Coef=-1 , 0 , 0 ,, 0 ,,,0.8,0,,0,
WSPro=,,,, 1 ,,,, 0 ,,,, 0 ,,,,-1 ,-1 ,-1 , 0 , 0 , 0 , 0 , 0
Culvert=1,3,3,40,0.012,0.2,1,1,3,95.04,817.85,94.72,817.65,Culvert #1  , 0 ,7
  817.85  817.65
BC Culvert Barrel=1,42inRCP,0
Culvert Bottom n=0.012
BC Design=,, 0 ,, 0 ,,,,,,
BC Use User HTab Curves=0
BC User HTab FreeFlow(D)= 0

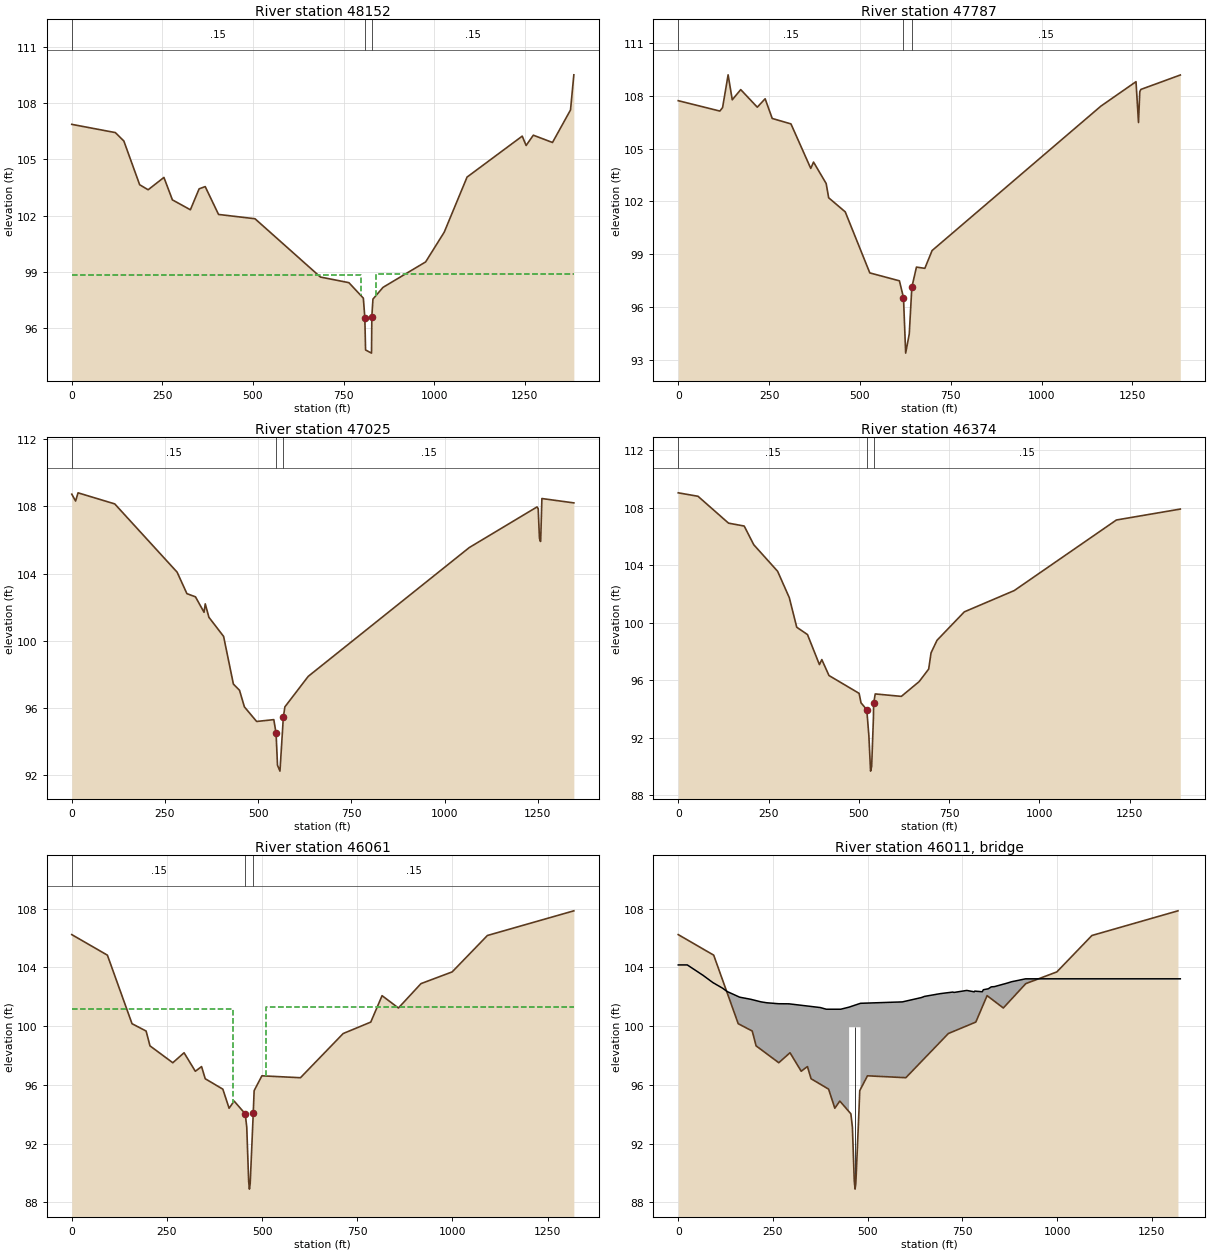
Type RM Length L Ch R = 1 ,48152   ,365.2,365.2,365.2
XS GIS Cut Line= 5
2575647.09472053799687.5824432022575774.17500855800300.810552255
2575821.96333865 800535.832556252575879.53510641800847.397417049
  2575906.627703801048.051960553
#Sta/Elev= 30
       0  106.88   120.2  106.44   143.7  105.99   187.3  103.65   210.7  103.38
   254.3  104.04   277.7  102.84   327.3  102.31   351.4  103.43   368.2  103.55
     405  102.06   505.6  101.83   686.2   98.71  764.71   98.41  804.58   97.58
  808.66   96.54   810.7   94.81   827.1   94.64  827.99   96.59  831.09   97.53
  858.92   98.16  976.45   99.52 1027.72  101.11  1090.8  104.06    1243  106.25
  1253.7  105.75  1273.6   106.3  1326.5  105.91  1376.2  107.651385.403  109.53
#Mann= 3 ,0,0
       0     .15       0  808.66     .05       0  827.99     .15       0
#XS Ineff= 2 , 0
             797   98.84   838.5            98.9
Permanent Ineff=
       F       F
Bank Sta=808.66,827.99
XS Rating Curve= 0 ,0
Exp/Cntr(USF)=0,0
Exp/Cntr=0.3,0.1

Type RM Length L Ch R = 1 ,47787   ,762.1,762.1,762.1
XS GIS Cut Line= 4
2575166.84304649799978.5353533362575440.58054129800450.701505554
2575462.21536006800637.5476677282575664.79593589801253.156602049
#Sta/Elev= 30
       0  107.73   114.6  107.14   122.1  107.34   137.3   109.2   148.7  107.78
     172  108.36   217.6  107.36   239.2  107.84   258.7  106.72   310.3  106.41
   364.8  103.88   372.4  104.24   407.2  103.02   414.1  102.21   459.7  101.41
   527.3   97.94   608.8   97.49     620  96.536     626   93.38   635.9   94.47
     643  97.127   655.7   98.27   678.8    98.2   698.7   99.21  1163.3  107.42
    1260  108.81  1266.9  106.49  1270.4  108.24  1273.4  108.371381.956  109.19
#Mann= 3 ,0,0
       0     .15       0     620     .05       0     643     .15       0
Bank Sta=620,643
XS Rating Curve= 0 ,0
Exp/Cntr(USF)=0,0
Exp/Cntr=0.3,0.1

Type RM Length L Ch R = 1 ,47025   ,650.2,650.2,650.2
XS GIS Cut Line= 4
2574698.95436957800083.7751397422574691.54851129800597.960237883
2574705.31612324800731.7027539652574778.08778641801425.983756569
#Sta/Elev= 30
       0  108.73   10.27  108.32   16.83  108.81  115.27  108.15  282.61  104.08
  308.86   102.8  331.82  102.61  354.79  101.69  358.07  102.19  367.92  101.39
  407.29  100.25  433.54   97.41  449.95   97.04  463.07   96.05  495.88   95.18
  541.96   95.29     548  94.485  551.86   92.57  558.45   92.22   567.5  95.427
  571.65   96.05  634.31   97.87 1066.45  105.55 1248.08  107.97 1251.19  107.86
 1254.49   106.1 1257.04  105.91 1257.78  105.93 1261.08  108.47 1346.77  108.21
#Mann= 3 ,0,0
       0     .15       0     548     .05       0   567.5     .15       0
Bank Sta=548,567.5
XS Rating Curve= 0 ,0
Exp/Cntr(USF)=0,0
Exp/Cntr=0.3,0.1

Type RM Length L Ch R = 1 ,46374   ,312.9,312.9,312.9
XS GIS Cut Line= 4
2573995.75181334800198.2467550892574048.85545943800623.075923821
2574052.78906284800770.5860518532574111.79311405801582.875156882
#Sta/Elev= 30
       0  109.04   54.72   108.8  139.28  106.93  182.64  106.73  209.09  105.43
  275.22  103.58  307.47  101.75  328.12   99.69  357.88   99.18  390.94   97.09
  397.55   97.44  417.39   96.33  500.82   95.09  506.09   94.43     522  93.954
   527.8   92.16  532.53   89.68  535.53      90  540.42   93.37     541  94.395
  545.47   95.05  617.77   94.88  667.11   95.91  693.43   96.78  700.01   97.91
  716.45   98.78  792.11  100.76  930.27  102.24 1213.17  107.15 1390.13  107.91
#Mann= 3 ,0,0
       0     .15       0     522     .05       0     541     .15       0
Bank Sta=522,541
XS Rating Curve= 0 ,0
Exp/Cntr(USF)=0,0
Exp/Cntr=0.5,0.3

Type RM Length L Ch R = 1 ,46061   ,94.4,94.4,94.4
XS GIS Cut Line= 5
2573668.50463338800308.6518877742573726.57347038800530.474845118
 2573747.4782517800860.3058392842573784.64230738801222.655382171
2573815.99947936801616.362097038
#Sta/Elev= 30
       0  106.24    93.6  104.84   158.3  100.17   195.3   99.67   205.5   98.66
   265.4   97.51     295   98.19   324.6   96.93     341   97.25   350.6   96.42
   396.9   95.71   413.3   94.41   426.5    94.9  455.71   94.03  459.71   93.12
  464.72   89.43  466.73    88.9  468.75   89.29  476.75   94.06   479.1   95.61
   499.5   96.62   600.8   96.49     713    99.5   785.5  100.28   815.2  102.08
   858.1  101.24   917.4   102.9   999.4   103.7  1091.9  106.181318.994  107.86
#Mann= 3 ,0,0
       0     .15       0  455.71     .05       0  476.75     .15       0
#XS Ineff= 2 , 0
       0     423  101.16     509       0   101.3
Permanent Ineff=
       F       F
Bank Sta=455.71,476.75
XS Rating Curve= 0 ,0
Exp/Cntr(USF)=0,0
Exp/Cntr=0.5,0.3

Type RM Length L Ch R = 3 ,46011   ,,,
Bridge Culvert--1,0,-1,-1, 0
Deck Dist Width WeirC Skew NumUp NumDn MinLoCord MaxHiCord MaxSubmerge Is_Ogee
27.98261,28,2.6,0, 37, 37, , , 0.98, 0, 2,2,,
       0  23.943  65.322  91.566 116.801 128.913  162.16 192.059 218.604 233.935
 264.641 292.032  375.06 390.938  428.84  450.99     451     481  481.01 591.511
 641.543 650.044 691.625 724.468  728.27 761.593 781.243 782.584 802.432 805.298
 818.377 826.251 834.416 867.534 879.642 916.838  1325.2
 104.174 104.174 103.468 102.969 102.593 102.365 101.977  101.83 101.658 101.596
 101.531 101.525  101.27 101.156 101.156   101.3   101.3  101.56  101.56 101.656
  101.95 102.031 102.219 102.325 102.301 102.438 102.342 102.391 102.348 102.485
  102.55 102.681 102.696 102.931 103.028 103.228 103.228
                                                                                
                                                   99.93   99.93
                                                                                
                                                        
       0  23.943  65.322  91.566 116.801 128.913  162.16 192.059 218.604 233.935
 264.641 292.032  375.06 390.938  428.84  464.99     465     495  495.01 591.511
 641.543 650.044 691.625 724.468  728.27 761.593 781.243 782.584 802.432 805.298
 818.377 826.251 834.416 867.534 879.642 916.838  1325.2
 104.174 104.174 103.468 102.969 102.593 102.365 101.977  101.83 101.658 101.596
 101.531 101.525  101.27 101.156 101.156   101.3   101.3  101.56  101.56 101.656
  101.95 102.031 102.219 102.325 102.301 102.438 102.342 102.391 102.348 102.485
  102.55 102.681 102.696 102.931 103.028 103.228 103.228
                                                                                
                                                   99.93   99.93
                                                                                
                                                        
Pier Skew, UpSta & Num, DnSta & Num=  ,466, 2 ,480, 2 , 0 , 0 , 0 ,,
       1       1
       0  100.75
       1       1
       0  100.75
BR Coef=-1 , 0 , 0 ,, 0 ,,,0.8,0,,0,
WSPro=,,,, 1 ,,,, 0 ,,,, 0 ,,,,-1 ,-1 ,-1 , 0 , 0 , 0 , 0 , 0
BC Design=,, 0 ,, 0 ,,,,,,
BC Use User HTab Curves=0
BC User HTab FreeFlow(D)= 0

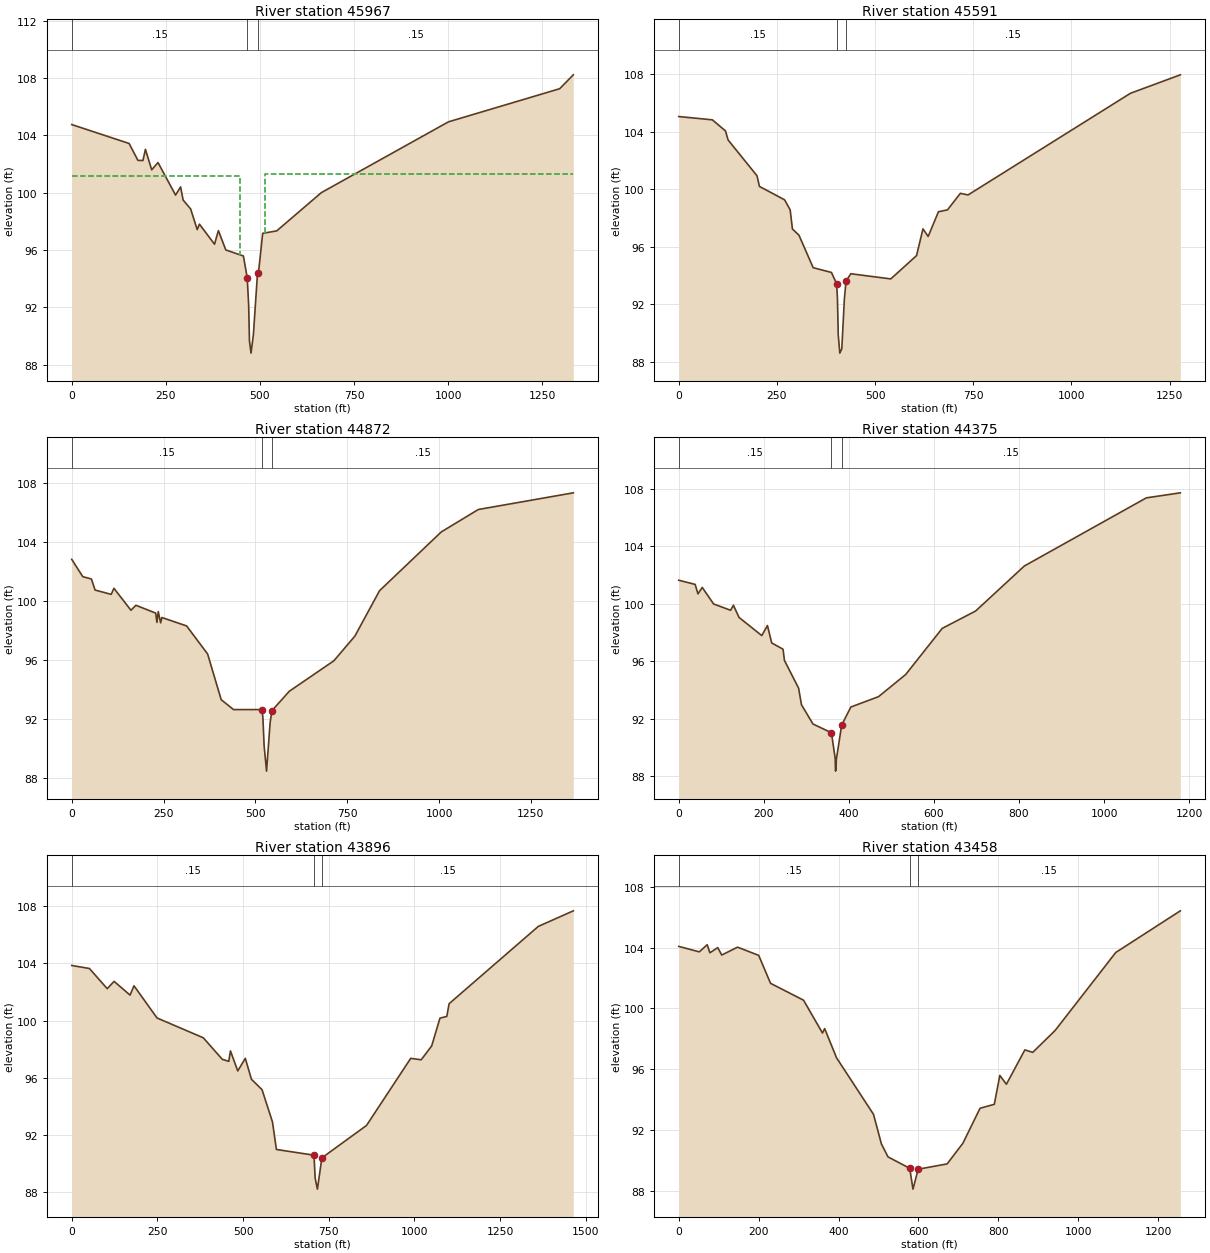
Type RM Length L Ch R = 1 ,45967   ,375.7,375.7,375.7
XS GIS Cut Line= 6
 2573561.1222244800321.4785459412573645.72694741800775.277375199
2573666.09465354800843.169728969 2573706.8300658801104.246689377
2573725.41209364801338.7930561732573727.73484712801639.589631838
#Sta/Elev= 30
       0  104.75   152.4  103.43   175.9  102.25   189.2  102.24   195.8  103.02
   212.5  101.59   229.2   102.1   275.9   99.83   289.3   100.4     296   99.48
     316   98.86   333.4   97.42   339.3    97.8   379.4    96.4   389.7   97.35
   409.4      96   456.1   95.58   466.3   94.06  470.13   92.16  472.22   89.66
  476.39    88.8  482.66   90.08   493.7    94.4   497.1   94.63   507.4   97.16
   544.7   97.33   663.3     100  1001.1  104.94  1296.5  107.251332.823  108.22
#Mann= 3 ,0,0
       0     .15       0   466.3     .05       0   493.7     .15       0
#XS Ineff= 2 , 0
       0     446  101.16     514       0   101.3
Permanent Ineff=
       F       F
Bank Sta=466.3,493.7
XS Rating Curve= 0 ,0
Exp/Cntr(USF)=0,0
Exp/Cntr=0.5,0.3

Type RM Length L Ch R = 1 ,45591   ,719.3,719.3,719.3
XS GIS Cut Line= 4
2573209.92008207800413.5796581752573273.64445738800738.573972255
2573281.09442631 800896.42861738 2573307.8525464801684.016253626
#Sta/Elev= 30
       0  105.05    85.6  104.82     119  104.05   125.7  103.42   199.3  100.93
   205.5  100.19   269.5   99.26   283.7   98.56   289.5   97.23   306.1    96.8
  342.31   94.54   388.8   94.21     402   93.43  404.12   92.39  406.12   89.89
  410.13    88.6  415.18    88.9   421.7   92.35     426  93.608   438.1   94.12
   539.9   93.76   605.5   95.38   621.9   97.24   635.1   96.71   661.3   98.43
   684.3   98.56   717.1   99.71   736.8    99.6  1150.5  106.671277.255  107.95
#Mann= 3 ,0,0
       0     .15       0     402     .05       0     426     .15       0
Bank Sta=402,426
XS Rating Curve= 0 ,0
Exp/Cntr(USF)=0,0
Exp/Cntr=0.3,0.1

Type RM Length L Ch R = 1 ,44872   ,497.6,497.6,497.6
XS GIS Cut Line= 4
2572451.60001589800337.1104078032572559.93145392800811.857003861
2572559.93145392800913.816004357 2572727.2079391801672.136070543
#Sta/Elev= 30
       0   102.8      30  101.63    53.6  101.47    63.6  100.72   107.4  100.43
   114.9  100.84   161.2   99.35   174.7   99.69   228.5   99.16   231.9   98.53
   235.5   99.26     242    98.5   245.4   98.86   312.7   98.29   369.9   96.39
   406.9   93.29   440.5   92.62     518  92.623   520.4   92.06   523.7   90.18
   530.3   88.45   540.1   91.75     545  92.545   592.1   93.86   713.7   95.93
   770.8    97.6     838  100.68    1006  104.66  1106.8  106.181365.459  107.31
#Mann= 3 ,0,0
       0     .15       0     518     .05       0     545     .15       0
Bank Sta=518,545
XS Rating Curve= 0 ,0
Exp/Cntr(USF)=0,0
Exp/Cntr=0.3,0.1

Type RM Length L Ch R = 1 ,44375   ,478.8,478.8,478.8
XS GIS Cut Line= 5
2571997.39772573800587.6098650732572051.98243251800893.051947698
2572107.72851604801024.287519321 2572319.9226416 801409.88273092
2572390.72750305 801687.20177162
#Sta/Elev= 30
       0  101.63    38.5  101.34    45.2  100.68    55.2  101.13    81.9   99.98
   121.9   99.54   128.5   99.89   141.8   99.04   195.2   97.78   208.5   98.48
   218.5   97.27   245.2   96.83   248.5   96.05   281.8   94.12   288.5   92.97
   315.5   91.63     359  91.018   367.7   89.24   368.6   88.35  369.88   88.52
  370.35   89.14     383   91.55   404.6   92.81   469.6   93.53   533.5   95.07
   619.4   98.28     698   99.49   812.5  102.62  1099.3  107.361179.206  107.71
#Mann= 3 ,0,0
       0     .15       0     359     .05       0     383     .15       0
Bank Sta=359,383
XS Rating Curve= 0 ,0
Exp/Cntr(USF)=0,0
Exp/Cntr=0.3,0.1

Type RM Length L Ch R = 1 ,43896   ,437.7,437.7,437.7
XS GIS Cut Line= 4
2571169.35607314800509.5289780472571603.03584955 800987.46179287
 2571623.7807889801157.3849637792571790.15350903801782.963399604
#Sta/Elev= 30
       0  103.86    51.6  103.65   103.5  102.24   123.6  102.75   170.2  101.79
   181.7  102.44     249  100.19   383.8   98.81   439.5    97.3   458.3   97.16
   463.2   97.89   484.5   96.49   506.6   97.37   524.4   95.91   555.4   95.18
   585.8   92.93   597.4      91     707  90.603   710.4      89     717   88.23
     730  90.414   860.3   92.68   989.3   97.37  1019.9   97.27  1050.5   98.24
  1074.7  100.18  1094.6   100.3  1101.4  101.19  1361.6  106.591463.875  107.68
#Mann= 3 ,0,0
       0     .15       0     707     .05       0     730     .15       0
Bank Sta=707,730
XS Rating Curve= 0 ,0
Exp/Cntr(USF)=0,0
Exp/Cntr=0.3,0.1

Type RM Length L Ch R = 1 ,43458   ,612.2,612.2,612.2
XS GIS Cut Line= 5
2571120.10489714800522.0104784952571183.35619161801043.774466689
2571177.14876715801139.068432477 2571183.0215654801218.496669793
2571241.93105613801773.395755023
#Sta/Elev= 30
       0  104.08   51.38  103.72   71.24  104.19   77.91  103.66   97.68     104
  107.59  103.51  147.25  104.03  200.13  103.49  229.87  101.65  312.49  100.54
  359.83   98.38  365.37   98.67  395.11   96.75  487.65   93.03  507.48   91.08
     524   90.23 578.338   89.48  586.48   88.11  599.43   89.42  671.99   89.77
   711.5   91.13  754.39   93.43   790.1   93.69  803.88   95.59  820.38   95.01
  866.57   97.27  886.36   97.11  942.45   98.55 1094.22  103.68 1255.88  106.42
#Mann= 3 ,0,0
       0     .15       0 578.338     .05       0  599.43     .15       0
Bank Sta=578.338,599.43
XS Rating Curve= 0 ,0
Exp/Cntr(USF)=0,0
Exp/Cntr=0.3,0.1