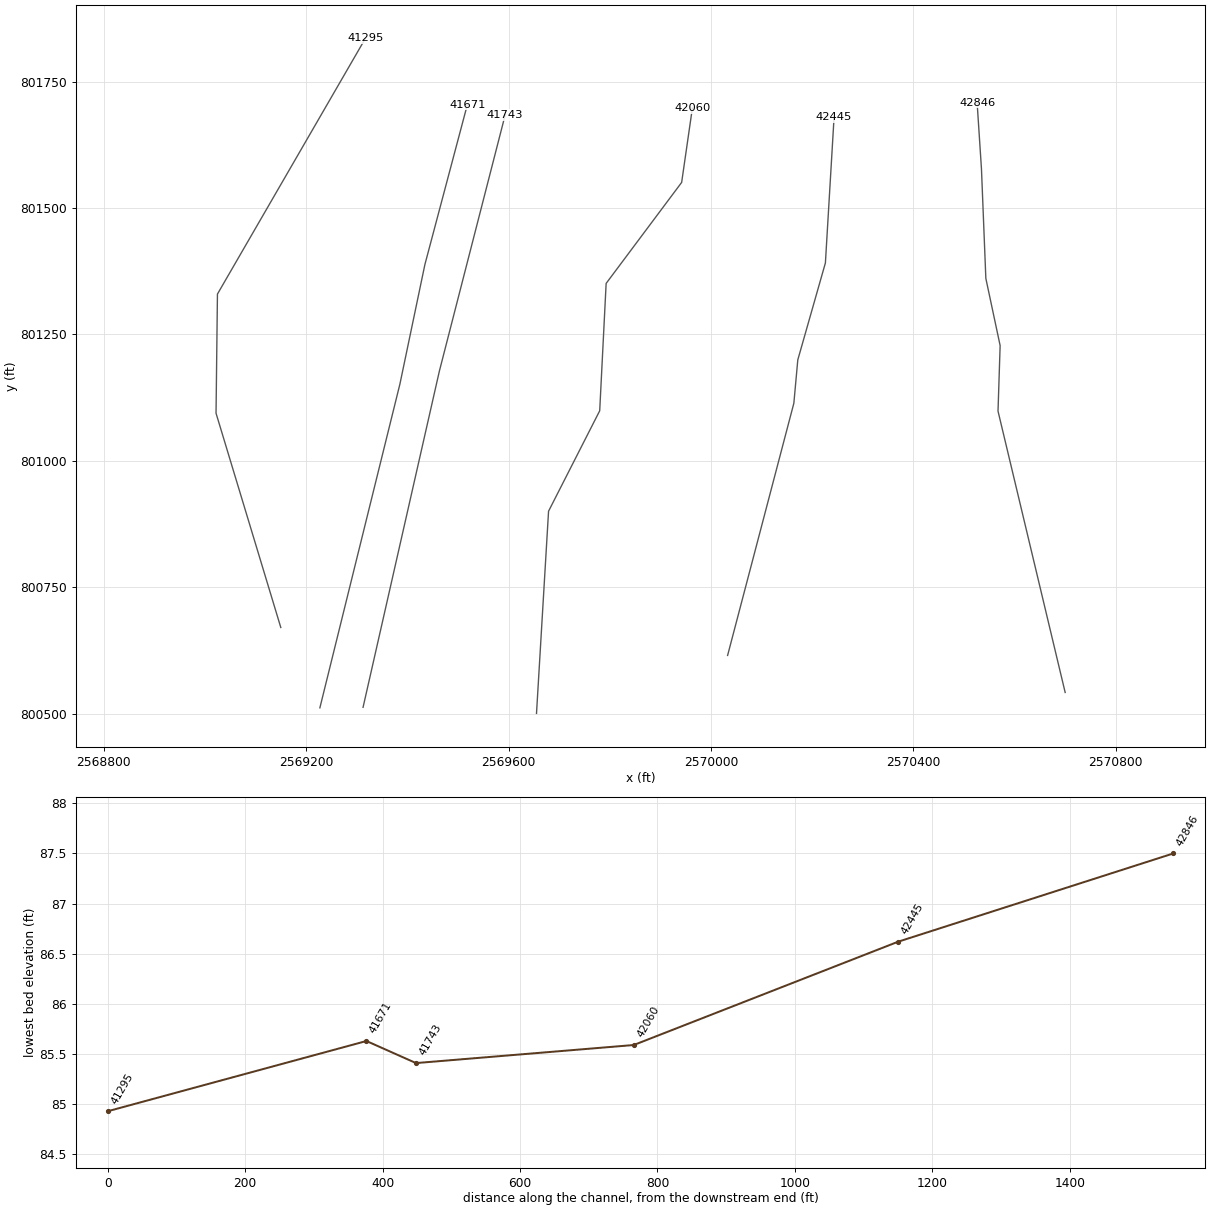
HEC-RAS study LousingSwamp.prj: S-26-569 over Lousing Swamp

--- LousingSwamp.g02 (geometry) --- (continued)

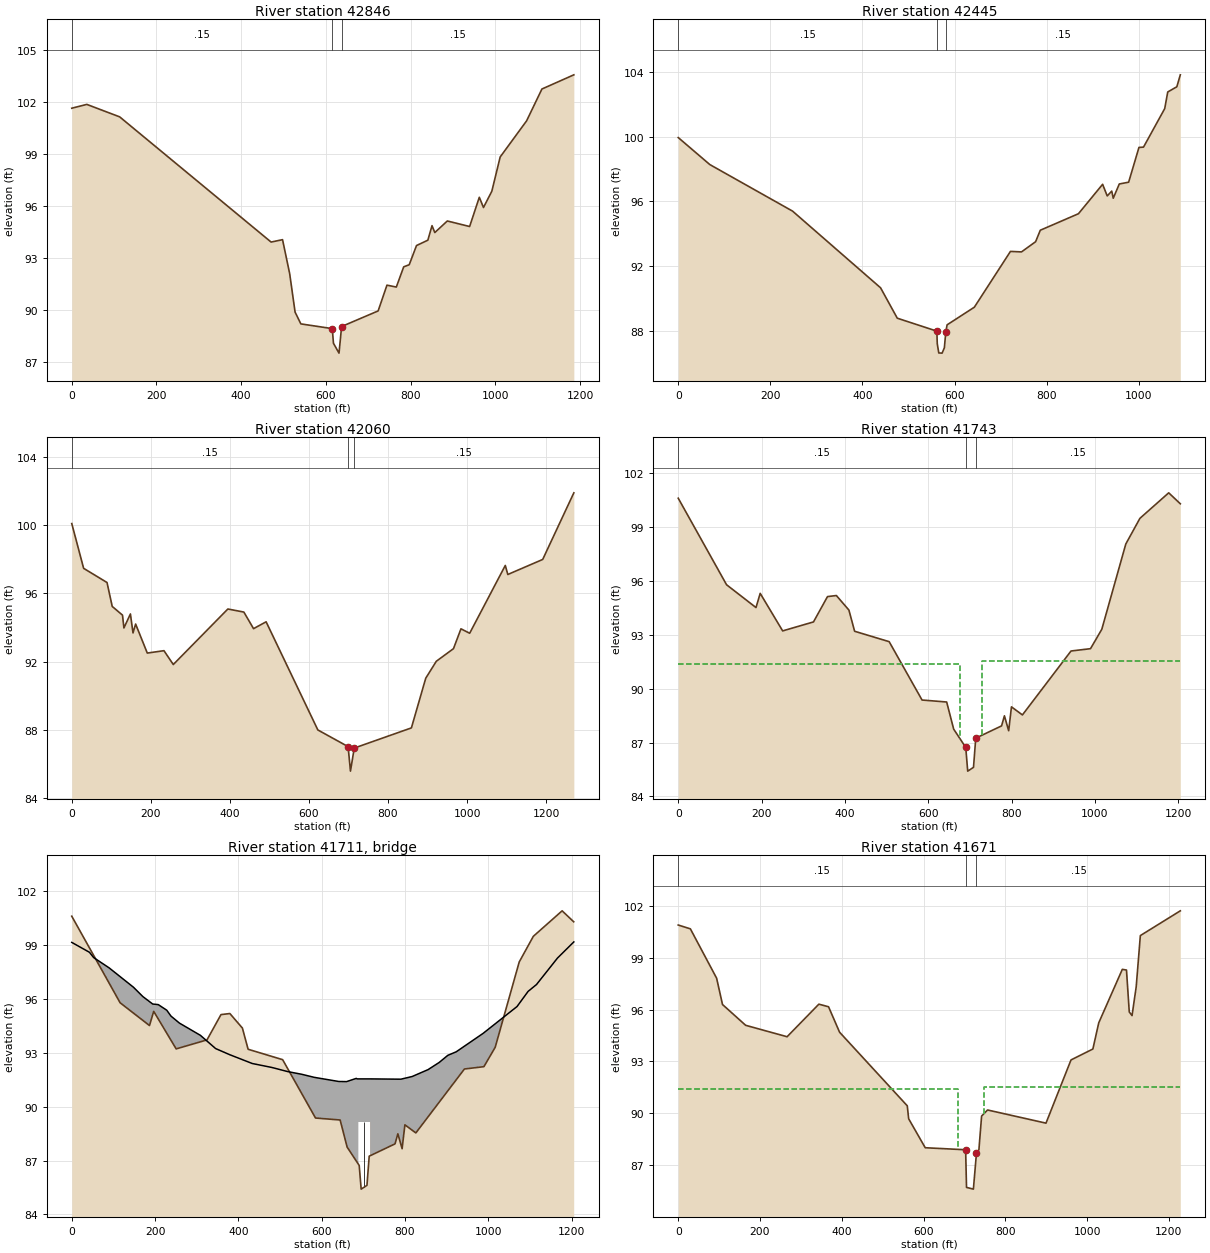
Type RM Length L Ch R = 1 ,42846   ,400.6,400.6,400.6
XS GIS Cut Line= 6
2570699.94996444800541.7966728142570567.23007117801098.206974327
2570571.41102743801227.8166185132570543.17515268801360.670069045
2570534.51486634801577.1772276752570525.94655288801707.928319531
#Sta/Elev= 30
       0  101.66    35.5  101.88  113.07  101.16   470.6   93.92  497.58   94.06
  514.45   92.09  527.19   89.87  540.81   89.19     615  88.917  617.75   88.07
  630.88    87.5     637  89.038  723.25   89.94  744.04   91.43  766.17   91.32
  783.62   92.49   796.6   92.61  813.81   93.72  840.58   94.03  850.43   94.87
     857   94.47  886.55   95.14   939.2   94.82  962.07   96.51  971.92   95.92
  991.62   96.86 1011.32   98.84 1073.73  100.93  1109.9  102.77 1185.23  103.59
#Mann= 3 ,0,0
       0     .15       0     615     .05       0     637     .15       0
Bank Sta=615,637
XS Rating Curve= 0 ,0
Exp/Cntr(USF)=0,0
Exp/Cntr=0.3,0.1

Type RM Length L Ch R = 1 ,42445   ,384.9,384.9,384.9
XS GIS Cut Line= 5
 2570032.7745177800614.9977145062570163.71804724801113.830207991
2570171.51230496801199.5670428092570226.07210893801391.305782492
2570243.21947589801679.693317788
#Sta/Elev= 30
       0   99.95    68.6   98.28   248.3    95.4   439.3   90.66   475.6   88.78
  561.45   87.98   562.4    87.2   565.7   86.63   572.9   86.62   577.8   86.95
     581   87.95  583.74   88.37   642.9   89.46   721.3   92.91   745.3   92.88
   775.9   93.51   786.1   94.22   868.9   95.24   921.4   97.06   931.4   96.34
   941.2   96.64   944.5    96.2   957.6   97.08   977.9   97.19  1000.3   99.34
  1010.2   99.36  1056.2  101.74  1062.8  102.77  1082.5  103.09 1090.07  103.83
#Mann= 3 ,0,0
       0     .15       0  561.45     .05       0     581     .15       0
Bank Sta=561.45,581
XS Rating Curve= 0 ,0
Exp/Cntr(USF)=0,0
Exp/Cntr=0.3,0.1

Type RM Length L Ch R = 1 ,42060   ,316.9,316.9,316.9
XS GIS Cut Line= 6
2569655.08996227 800500.421704732569678.91521764800900.267546718
 2569779.9971138801098.8997619862569792.71138021801350.775642397
2569941.95335902801550.5225333062569963.15039806801697.489568961
#Sta/Elev= 30
       0  100.08   30.03   97.46   89.19   96.63  102.33   95.23  128.34   94.72
  131.91   93.97  148.35   94.79  154.92   93.68  161.49    94.2  191.07    92.5
  233.19   92.64  256.81   91.83  394.85   95.08  435.29    94.9  459.83   93.93
  491.61   94.33  622.45      88     699  87.024  704.97   85.59  714.54   86.94
  859.08   88.12   895.4   91.03  922.08   92.02  965.56   92.76  984.47   93.92
 1006.51   93.66 1096.61   97.63 1102.97    97.1  1191.2   97.98 1269.99  101.88
#Mann= 3 ,0,0
       0     .15       0     699     .05       0  714.54     .15       0
Bank Sta=699,714.54
XS Rating Curve= 0 ,0
Exp/Cntr(USF)=0,0
Exp/Cntr=0.5,0.3

Type RM Length L Ch R = 1 ,41743   ,72.1,72.1,72.1
XS GIS Cut Line= 3
2569312.28744664800512.4116812122569463.12561494 801177.38405876
2569593.17383767801683.992306915
#Sta/Elev= 30
       0  100.61     116   95.79   186.6   94.52   196.7   95.31   250.6   93.22
   324.6   93.72   358.2   95.13   379.5   95.19   409.6   94.38   423.3    93.2
   506.2   92.62   585.1   89.37   644.2   89.26     661   87.75     690  86.729
   694.7   85.41   708.6   85.62     714  87.245     776   87.93   782.8   88.49
     793   87.66   799.7   88.99     826   88.54   942.6    92.1   989.4   92.23
  1016.5   93.31  1074.1   98.06    1108   99.49  1177.1  100.911204.899   100.3
#Mann= 3 ,0,0
       0     .15       0     690     .05       0     714     .15       0
#XS Ineff= 2 , 0
             676    91.4     728           91.53
Permanent Ineff=
       F       F
Bank Sta=690,714
XS Rating Curve= 0 ,0
Exp/Cntr(USF)=0,0
Exp/Cntr=0.5,0.3

Type RM Length L Ch R = 3 ,41711   ,,,
Bridge Culvert--1,0,-1,-1, 0
Deck Dist Width WeirC Skew NumUp NumDn MinLoCord MaxHiCord MaxSubmerge Is_Ogee
12,26.2,2.6,0, 39, 40, , , 0.98, 0, 2,2,,
       0  42.449  52.571  89.687 148.029 170.666 194.269 207.611 228.026 238.148
 258.393 308.777 345.324 379.204 433.351  480.73 517.956 551.773 582.168 641.022
 659.724 682.961  684.99     688     688     716     716 789.961 817.049 855.344
 882.062 902.665 922.945 987.1661068.9721095.3281115.6081166.0071205.237
  99.151  98.601  98.305  97.733  96.656  96.134  95.719  95.687  95.375  95.047
  94.658  93.976  93.238  92.897  92.406  92.184  91.958  91.808  91.636  91.405
  91.399  91.578   91.55   91.55   91.55   91.55   91.55  91.533  91.682  92.067
  92.467  92.862   93.06  94.081  95.582  96.421  96.806   98.28  99.179
                                                                                
                                                                                
                                   89.15   89.15
                                                                        
       0  42.449  52.571  89.687 148.029 170.666 194.269 207.611 228.026 238.148
 258.393 308.777 345.324 379.204 433.351  480.73 517.956 551.773 582.168 641.022
 659.724 682.961  697.99  702.23  702.23  730.23  730.23  733.01 789.961 817.049
 855.344 882.062 902.665 922.945 987.1661068.9721095.3281115.6081166.0071205.237
  99.151  98.601  98.305  97.733  96.656  96.134  95.719  95.687  95.375  95.047
  94.658  93.976  93.238  92.897  92.406  92.184  91.958  91.808  91.636  91.405
  91.399  91.578   91.55   91.55   91.55   91.55   91.55   91.55  91.533  91.682
  92.067  92.467  92.862   93.06  94.081  95.582  96.421  96.806   98.28  99.179
                                                                                
                                                                                
                                   89.15   89.15
                                                                                
Pier Skew, UpSta & Num, DnSta & Num=  ,702, 2 ,716.23, 2 , 0 , 0 , 0 ,,
       1       1
       0      91
       1       1
       0      91
Abutment Skew #Up #Dn= , 2 , 2
     696     716
   78.15   88.15
  710.23  730.23
   78.15   88.15
BR Coef=-1 , 0 , 0 ,, 0 ,,,0.8,0,,0,
WSPro=,,,, 1 ,,,, 0 ,,,, 0 ,,,,-1 ,-1 ,-1 , 0 , 0 , 0 , 0 , 0
BC Design=,, 0 ,, 0 ,,,,,,
BC Use User HTab Curves=0
BC User HTab FreeFlow(D)= 0

Type RM Length L Ch R = 1 ,41671   ,376.5,376.5,376.5
XS GIS Cut Line= 4
2569226.92904694800511.3730303192569385.07253012 801151.53519778
2569434.51050773 801388.17091083 2569518.3884248 801704.24067779
#Sta/Elev= 30
       0  100.88    29.7  100.66    93.9   97.81   108.3   96.29   164.9   95.09
   266.3   94.43     344   96.31   367.7   96.16   394.7   94.69   560.3   90.44
   563.7   89.69   604.2   88.02     703  87.903   705.2   85.73     722   85.63
   729.6   87.73   735.5    87.9   742.1   89.85   756.7    90.2   899.6   89.44
   960.8   93.09  1014.3   93.72  1028.6   95.23  1086.3   98.32  1096.5   98.28
  1103.3   95.86  1110.1   95.65  1120.3   97.32  1130.4  100.271228.161   101.7
#Mann= 3 ,0,0
       0     .15       0     703     .05       0   729.6     .15       0
#XS Ineff= 2 , 0
          685.28    91.4  747.18           91.53
Permanent Ineff=
       F       F
Bank Sta=703,729.6
XS Rating Curve= 0 ,0
Exp/Cntr(USF)=0,0
Exp/Cntr=0.5,0.3

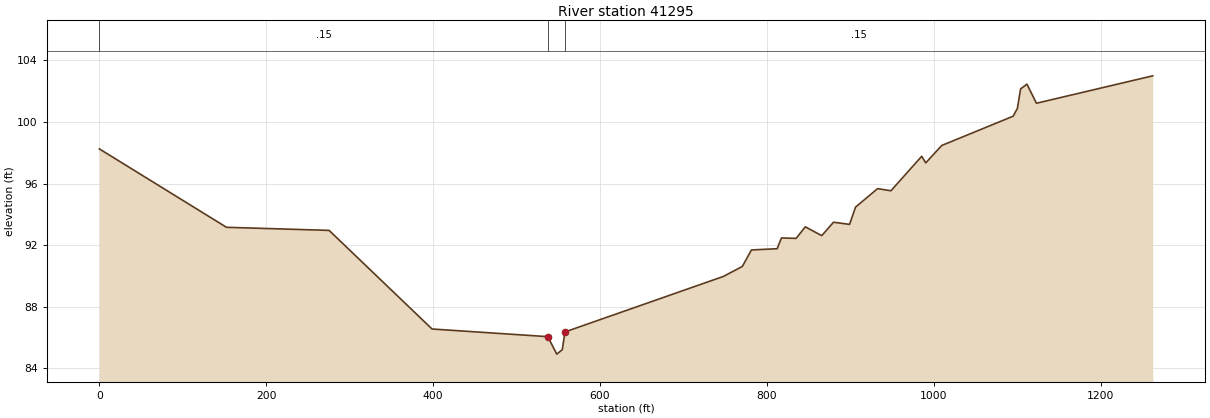
Type RM Length L Ch R = 1 ,41295   ,,,
XS GIS Cut Line= 4
2569149.69737617800670.3000383782569021.70801988 801094.04293728
2569024.49022067 801329.703942732569316.98741382801835.488050017
#Sta/Elev= 30
       0   98.25   152.4   93.16   275.4   92.96   398.8   86.56   537.5  86.064
   548.3   84.93   554.9   85.22   558.1   86.37   747.9   89.97   770.7   90.62
   781.6   91.69   812.4   91.77   817.6   92.47   835.1   92.44   846.2   93.19
   865.9   92.62     880   93.49   899.2   93.35   906.4   94.47   932.8   95.67
   948.8   95.53   985.7   97.77   990.5   97.34  1009.7   98.47  1095.3  100.37
  1100.4  100.88  1104.2  102.14  1111.8  102.45  1123.2  101.21  1262.6  102.99
#Mann= 3 ,0,0
       0     .15       0   537.5     .05       0   558.1     .15       0
Bank Sta=537.5,558.1
XS Rating Curve= 0 ,0
Exp/Cntr(USF)=0,0
Exp/Cntr=0.3,0.1
LCMann Table=0

Chan Stop Cuts=-1
Use User Specified Reach Order=0
Composite Channel Slope=5

--- LousingSwamp.g04 (geometry) ---

Geom Title=Natural
Program Version=6.60

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
River Reach=Lousing Swamp   ,Reach-1

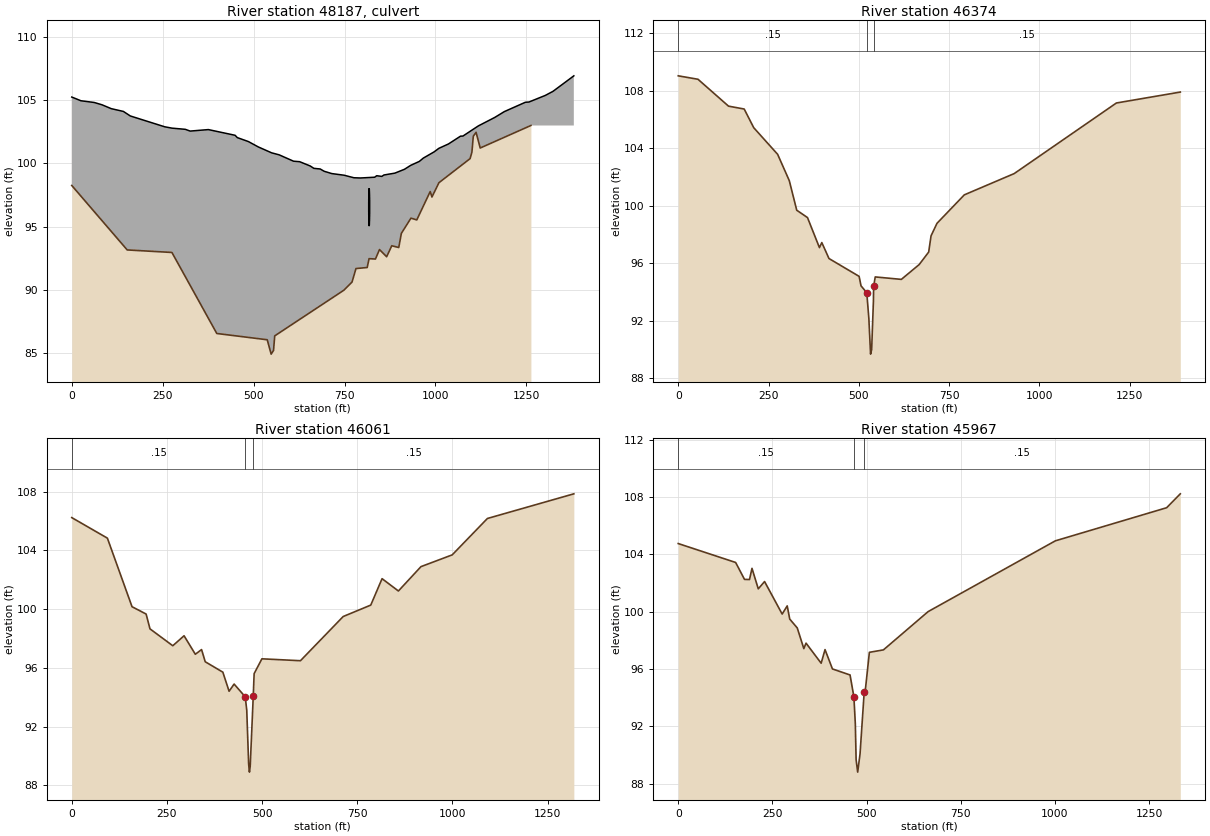
Type RM Length L Ch R = 2 ,48187   ,,,
BEGIN DESCRIPTION:
Culvert geometry assumed, need to field verify
END DESCRIPTION:
Bridge Culvert--1,0,-1,-1, 0
Deck Dist Width WeirC Skew NumUp NumDn MinLoCord MaxHiCord MaxSubmerge Is_Ogee
17.95996,22,2.6,0, 50, 50, , , 0.98, 0, 2,2,,
       0  25.214  61.917  83.213 108.629 141.995 160.965  255.44 275.459 312.162
 325.508 375.557 449.082 455.308 485.887 512.757 549.654 570.227 609.887  626.63
 655.741  665.74 683.237 693.988 715.046 748.716 775.758 793.519 832.899 838.524
 852.588 858.475  888.45 914.911 932.087 955.804 966.766 996.2461009.4781035.895
1069.0231075.6391118.1341163.087 1189.641247.2571257.1631302.0441323.3221380.679
 105.236 104.944 104.807 104.625  104.32 104.101 103.743 102.889 102.781 102.688
 102.549 102.667 102.217 102.033 101.719 101.299  100.83 100.673  100.17 100.131
  99.792  99.605  99.555  99.375  99.192  99.063  98.863  98.844  98.904  99.022
  98.969  99.081  99.227  99.531  99.843 100.154 100.416 100.904 101.186 101.532
 102.147 102.156 102.959 103.625 104.089 104.824 104.844 105.364 105.688 106.913
                                                                                
                                                                                
                                                                                
                                                                                
                                                                                
       0  25.214  61.917  83.213 108.629 141.995 160.965  255.44 275.459 312.162
 325.508 375.557 449.082 455.308 485.887 512.757 549.654 570.227 609.887  626.63
 655.741  665.74 683.237 693.988 715.046 748.716 775.758 793.519 832.899 838.524
 852.588 858.475  888.45 914.911 932.087 955.804 966.766 996.2461009.4781035.895
1069.0231075.6391118.1341163.087 1189.641247.2571257.1631302.0441323.3221380.679
 105.236 104.944 104.807 104.625  104.32 104.101 103.743 102.889 102.781 102.688
 102.549 102.667 102.217 102.033 101.719 101.299  100.83 100.673  100.17 100.131
  99.792  99.605  99.555  99.375  99.192  99.063  98.863  98.844  98.904  99.022
  98.969  99.081  99.227  99.531  99.843 100.154 100.416 100.904 101.186 101.532
 102.147 102.156 102.959 103.625 104.089 104.824 104.844 105.364 105.688 106.913
                                                                                
                                                                                
                                                                                
                                                                                
                                                                                
BR Coef=-1 , 0 , 0 ,, 0 ,,,0.8,0,,0,
WSPro=,,,, 1 ,,,, 0 ,,,, 0 ,,,,-1 ,-1 ,-1 , 0 , 0 , 0 , 0 , 0
Culvert=1,3,2.5,40,0.012,0.2,1,1,3,95.04,817.85,94.72,817.65,Culvert #1  , 0 ,7
  817.85  817.65
BC Culvert Barrel=1,42inRCP,0
Culvert Bottom n=0.012
BC Design=,, 0 ,, 0 ,,,,,,
BC Use User HTab Curves=0
BC User HTab FreeFlow(D)= 0

Type RM Length L Ch R = 1 ,46374   ,312.9,312.9,312.9
XS GIS Cut Line= 4
2573995.75181334800198.2467550892574048.85545943800623.075923821
2574052.78906284800770.5860518532574111.79311405801582.875156882
#Sta/Elev= 30
       0  109.04   54.72   108.8  139.28  106.93  182.64  106.73  209.09  105.43
  275.22  103.58  307.47  101.75  328.12   99.69  357.88   99.18  390.94   97.09
  397.55   97.44  417.39   96.33  500.82   95.09  506.09   94.43     522  93.954
   527.8   92.16  532.53   89.68  535.53      90  540.42   93.37     541  94.395
  545.47   95.05  617.77   94.88  667.11   95.91  693.43   96.78  700.01   97.91
  716.45   98.78  792.11  100.76  930.27  102.24 1213.17  107.15 1390.13  107.91
#Mann= 3 ,0,0
       0     .15       0     522     .05       0     541     .15       0
Bank Sta=522,541
XS Rating Curve= 0 ,0
Exp/Cntr(USF)=0,0
Exp/Cntr=0.3,0.1

Type RM Length L Ch R = 1 ,46061   ,94.4,94.4,94.4
XS GIS Cut Line= 5
2573668.50463338800308.6518877742573726.57347038800530.474845118
 2573747.4782517800860.3058392842573784.64230738801222.655382171
2573815.99947936801616.362097038
#Sta/Elev= 30
       0  106.24    93.6  104.84   158.3  100.17   195.3   99.67   205.5   98.66
   265.4   97.51     295   98.19   324.6   96.93     341   97.25   350.6   96.42
   396.9   95.71   413.3   94.41   426.5    94.9  455.71   94.03  459.71   93.12
  464.72   89.43  466.73    88.9  468.75   89.29  476.75   94.06   479.1   95.61
   499.5   96.62   600.8   96.49     713    99.5   785.5  100.28   815.2  102.08
   858.1  101.24   917.4   102.9   999.4   103.7  1091.9  106.181318.994  107.86
#Mann= 3 ,0,0
       0     .15       0  455.71     .05       0  476.75     .15       0
Bank Sta=455.71,476.75
XS Rating Curve= 0 ,0
Exp/Cntr(USF)=0,0
Exp/Cntr=0.3,0.1

Type RM Length L Ch R = 1 ,45967   ,375.7,375.7,375.7
XS GIS Cut Line= 6
 2573561.1222244800321.4785459412573645.72694741800775.277375199
2573666.09465354800843.169728969 2573706.8300658801104.246689377
2573725.41209364801338.7930561732573727.73484712801639.589631838
#Sta/Elev= 30
       0  104.75   152.4  103.43   175.9  102.25   189.2  102.24   195.8  103.02
   212.5  101.59   229.2   102.1   275.9   99.83   289.3   100.4     296   99.48
     316   98.86   333.4   97.42   339.3    97.8   379.4    96.4   389.7   97.35
   409.4      96   456.1   95.58   466.3   94.06  470.13   92.16  472.22   89.66
  476.39    88.8  482.66   90.08   493.7    94.4   497.1   94.63   507.4   97.16
   544.7   97.33   663.3     100  1001.1  104.94  1296.5  107.251332.823  108.22
#Mann= 3 ,0,0
       0     .15       0   466.3     .05       0   493.7     .15       0
Bank Sta=466.3,493.7
XS Rating Curve= 0 ,0
Exp/Cntr(USF)=0,0
Exp/Cntr=0.3,0.1

--- LousingSwamp.g06 (geometry) ---

Geom Title=Proposed
Program Version=6.60

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
River Reach=Lousing Swamp   ,Reach-1

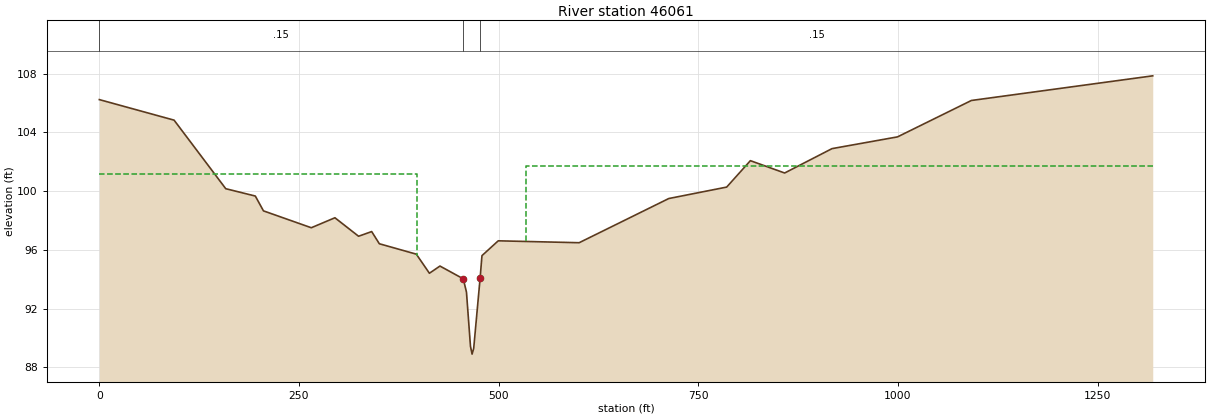
Type RM Length L Ch R = 1 ,46061   ,94.4,94.4,94.4
XS GIS Cut Line= 5
2573668.50463338800308.6518877742573726.57347038800530.474845118
 2573747.4782517800860.3058392842573784.64230738801222.655382171
2573815.99947936801616.362097038
#Sta/Elev= 30
       0  106.24    93.6  104.84   158.3  100.17   195.3   99.67   205.5   98.66
   265.4   97.51     295   98.19   324.6   96.93     341   97.25   350.6   96.42
   396.9   95.71   413.3   94.41   426.5    94.9  455.71   94.03  459.71   93.12
  464.72   89.43  466.73    88.9  468.75   89.29  476.75   94.06   479.1   95.61
   499.5   96.62   600.8   96.49     713    99.5   785.5  100.28   815.2  102.08
   858.1  101.24   917.4   102.9   999.4   103.7  1091.9  106.181318.994  107.86
#Mann= 3 ,0,0
       0     .15       0  455.71     .05       0  476.75     .15       0
#XS Ineff= 2 , 0
       0  398.23  101.15  534.23       0  101.74
Permanent Ineff=
       F       F
Bank Sta=455.71,476.75
XS Rating Curve= 0 ,0
Exp/Cntr(USF)=0,0
Exp/Cntr=0.5,0.3