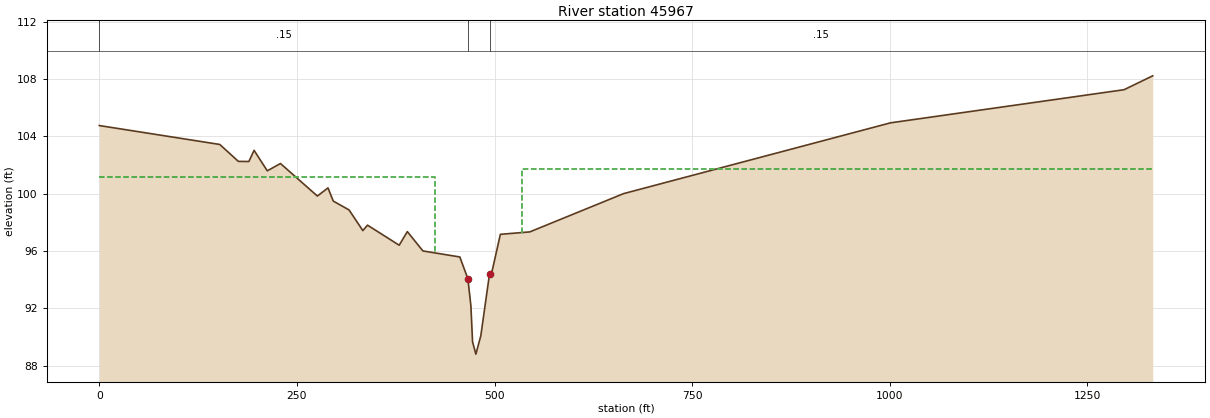
HEC-RAS study LousingSwamp.prj: S-26-569 over Lousing Swamp

--- LousingSwamp.g06 (geometry) --- (continued)

Type RM Length L Ch R = 3 ,46011   ,,,
Bridge Culvert--1,0,-1,-1, 0
Deck Dist Width WeirC Skew NumUp NumDn MinLoCord MaxHiCord MaxSubmerge Is_Ogee
28,36,2.6,0, 81, 80, , , 0.98, 0, 2,2,,
      20  199.23  210.23  215.23  219.23  226.23  233.23  234.23  249.23  250.23
  257.23  258.23  268.23  269.23  294.23  295.23  305.23  306.23  313.23  320.23
  329.23  338.23  341.23  348.23  353.23  370.23  372.23  377.23  383.23  390.23
  395.23  407.23  410.23  415.23  426.22  426.23  427.23  434.23  437.23  441.23
  448.23  460.23  465.23  474.23  475.23  486.23  487.23  493.23  494.23  502.23
  503.23  506.23  506.24  514.23  526.23  526.24  564.23  565.23  601.23  602.23
  617.23  618.23  627.23  628.23  636.23  643.23  644.23  650.23  657.23  666.23
  672.23  676.23  688.23  689.23  696.23  700.23  713.23  719.23  731.23  739.23
    1000
  101.35  101.31  101.27  101.26  101.24  101.22  101.21   101.2  101.18  101.17
  101.17  101.16  101.16  101.15  101.15  101.16  101.16  101.17  101.17  101.19
   101.2  101.23  101.23  101.26  101.27  101.34  101.34  101.37  101.39  101.42
  101.45  101.49  101.51  101.52  101.55  101.55  101.56  101.59  101.59  101.61
  101.63  101.65  101.67  101.68  101.69   101.7  101.71  101.71  101.72  101.72
  101.73  101.73  101.73  101.74  101.74  101.74  101.74  101.73  101.73  101.74
  101.74  101.75  101.75  101.76  101.76  101.77  101.78  101.78   101.8  101.81
  101.83  101.83  101.86  101.87  101.88   101.9  101.93  101.95     102  102.02
     103
                                                                                
                                                                                
                                                                                
                                           98.12   98.12   98.12   98.12   98.12
   98.12   98.12   98.12   98.12   98.12   98.12   98.12   98.12   98.12   98.12
   98.12   98.12
                                                                                
                                                                                
        
  199.23  210.23  215.23  219.23  226.23  233.23  234.23  249.23  250.23  257.23
  258.23  268.23  269.23  294.23  295.23  305.23  306.23  313.23  320.23  329.23
  338.23  341.23  348.23  353.23  370.23  372.23  377.23  383.23  390.23  395.23
  407.23  410.23  415.23  422.23  427.23  434.23  437.23  439.99     440  441.23
  448.23  460.23  465.23  474.23  475.23  486.23  487.23  493.23  494.23  502.23
  503.23  513.23  514.23     520  520.01  564.23  565.23  601.23  602.23  617.23
  618.23  627.23  628.23  636.23  643.23  644.23  650.23  657.23  666.23  672.23
  676.23  688.23  689.23  696.23  700.23  713.23  719.23  731.23  739.23     940
  101.31  101.27  101.26  101.24  101.22  101.21   101.2  101.18  101.17  101.17
  101.16  101.16  101.15  101.15  101.16  101.16  101.17  101.17  101.19   101.2
  101.23  101.23  101.26  101.27  101.34  101.34  101.37  101.39  101.42  101.45
  101.49  101.51  101.52  101.55  101.56  101.59  101.59   101.6   101.6  101.61
  101.63  101.65  101.67  101.68  101.69   101.7  101.71  101.71  101.72  101.72
  101.73  101.73  101.74  101.74  101.74  101.74  101.73  101.73  101.74  101.74
  101.75  101.75  101.76  101.76  101.77  101.78  101.78   101.8  101.81  101.83
  101.83  101.86  101.87  101.88   101.9  101.93  101.95     102  102.02  103.75
                                                                                
                                                                                
                                                                                
                                                                   98.12   98.12
   98.12   98.12   98.12   98.12   98.12   98.12   98.12   98.12   98.12   98.12
   98.12   98.12   98.12   98.12
                                                                                
                                                                                
Abutment Skew #Up #Dn= , 3 , 3
  426.24  428.23  466.23
   96.48   96.48   76.48
  439.99     442     480
   96.48   96.48   76.48
Abutment Skew #Up #Dn= , 3 , 3
  466.23  504.23  506.24
   76.65   96.65   96.65
     480     518  520.01
   76.65   96.65   96.65
BR Coef=-1 , 0 , 0 ,, 0 ,,,0.8,0,,0,
WSPro=,,,, 1 ,,,, 0 ,,,, 0 ,,,,-1 ,-1 ,-1 , 0 , 0 , 0 , 0 , 0
BC Design=,, 0 ,, 0 ,,,,,,
BC Use User HTab Curves=0
BC User HTab FreeFlow(D)= 0

Type RM Length L Ch R = 1 ,45967   ,375.7,375.7,375.7
XS GIS Cut Line= 6
 2573561.1222244800321.4785459412573645.72694741800775.277375199
2573666.09465354800843.169728969 2573706.8300658801104.246689377
2573725.41209364801338.7930561732573727.73484712801639.589631838
#Sta/Elev= 30
       0  104.75   152.4  103.43   175.9  102.25   189.2  102.24   195.8  103.02
   212.5  101.59   229.2   102.1   275.9   99.83   289.3   100.4     296   99.48
     316   98.86   333.4   97.42   339.3    97.8   379.4    96.4   389.7   97.35
   409.4      96   456.1   95.58   466.3   94.06  470.13   92.16  472.22   89.66
  476.39    88.8  482.66   90.08   493.7    94.4   497.1   94.63   507.4   97.16
   544.7   97.33   663.3     100  1001.1  104.94  1296.5  107.251332.823  108.22
#Mann= 3 ,0,0
       0     .15       0   466.3     .05       0   493.7     .15       0
#XS Ineff= 2 , 0
       0   424.8  101.15   535.2       0  101.74
Permanent Ineff=
       F       F
Bank Sta=466.3,493.7
XS Rating Curve= 0 ,0
Exp/Cntr(USF)=0,0
Exp/Cntr=0.5,0.3