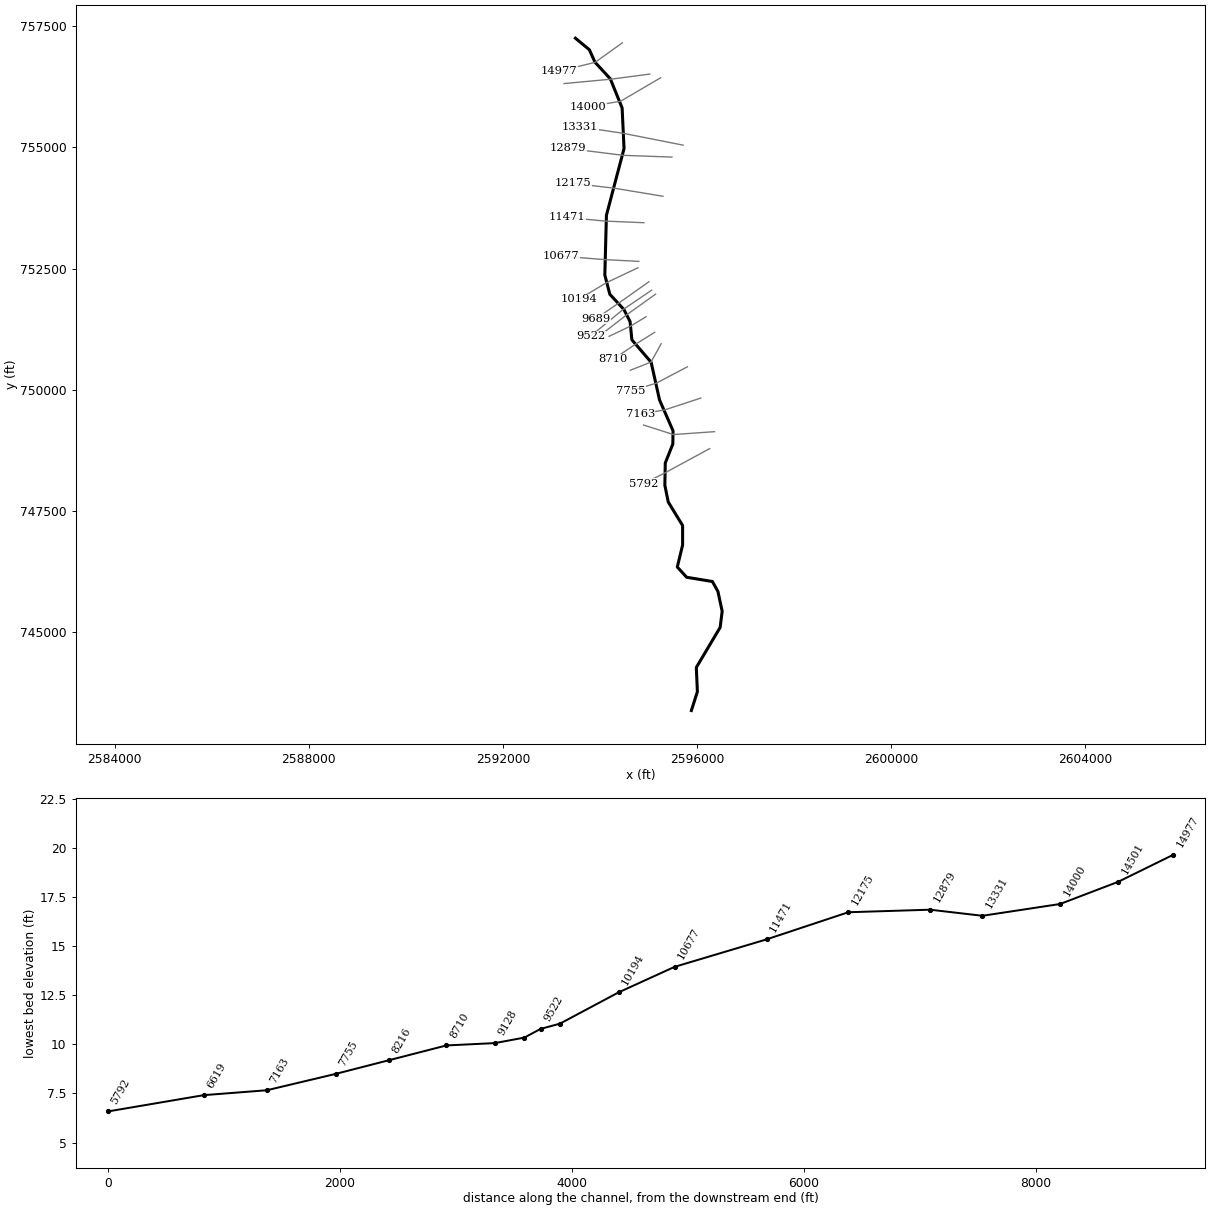
--- GrierSwamp.prj (project) ---

Proj Title=S-26-65 over Grier Swamp
Current Plan=p01
Default Exp/Contr=0.3,0.1
English Units
Geom File=g02
Geom File=g03
Geom File=g01
Geom File=g04
Flow File=f01
Flow File=f02
Flow File=f03
Plan File=p02
Plan File=p03
Plan File=p04
Plan File=p01
Plan File=p05
Y Axis Title=Elevation
X Axis Title(PF)=Main Channel Distance
X Axis Title(XS)=Station
BEGIN DESCRIPTION:
END DESCRIPTION:
DSS File=dss
DSS Export Rating Curves= 0
DSS Export Rating Curve Sorted= 0
DSS Export Volume Flow Curves= 0
DXF OffsetX= 0
DXF OffsetY= 0
DXF ScaleX= 1
DXF ScaleY= 10

--- GrierSwamp.p01 (plan) ---

Plan Title=Proposed_Conditions
Program Version=6.60
Short Identifier=PRO
Geom File=g01
Flow File=f01
Subcritical Flow
K Sum by GR= 0
Std Step Tol= 0.01
Critical Tol= 0.01
Num of Std Step Trials= 20
Max Error Tol= 0.3
Flow Tol Ratio= 0.001
Split Flow NTrial= 30
Split Flow Tol= 0.02
Split Flow Ratio= 0.02
Log Output Level= 0
Friction Slope Method= 1
Unsteady Friction Slope Method= 2
Unsteady Bridges Friction Slope Method= 1
Parabolic Critical Depth
Global Vel Dist= 0 , 0 , 0
Global Log Level= 0
CheckData=True
Encroach Param=-1 ,0,0, 0
Flow Ratio Tolerance=0.1
Flow Ratio Min Ratio=0.5
Flow Ratio Max Ratio=4
Flow Ratio Max Iterations= 10
Computation Interval=1MIN
Output Interval=1HOUR
Instantaneous Interval=1HOUR
Mapping Interval=1HOUR
Computation Time Step Use Courant=        0
Computation Time Step Use Time Series=    0
Computation Time Step Count To Double=0
Computation Time Step Max Doubling=0
Computation Time Step Max Halving=0
Computation Time Step Residence Courant=0
Run HTab= 0
Run UNet= 0
Run Sediment= 0
Run PostProcess= 0
Run WQNet= 0
Run RASMapper= 0
UNET Theta= 1
UNET Theta Warmup= 1
UNET ZTol= 0.02
UNET ZSATol= 0.02
UNET MxIter= 20
UNET Max Iter WO Improvement= 0
UNET MaxInSteps= 0
UNET DtIC= 0
UNET DtMin= 0
UNET MaxCRTS= 20
UNET WFStab= 2
UNET SFStab= 1
UNET WFX= 1
UNET SFX= 1
UNET Gravity=32.17405
UNET 1D Methodology=Finite Difference
UNET DSS MLevel= 4
UNET Pardiso=0
UNET DZMax Abort= 100
UNET Use Existing IB Tables=-1
UNET Froude Reduction=False
UNET Froude Limit= 0.8
UNET Froude Power= 4
UNET D1 Cores= 0
UNET WindReference=Eulerian
UNET WindDragFormulation=Hsu (1988)
UNET D2 Coriolis=0
UNET D2 Cores= 0
UNET D2 Theta= 1
UNET D2 Theta Warmup= 1
UNET D2 Z Tol= 0.01
UNET D2 Volume Tol= 0.01
UNET D2 Max Iterations= 20
UNET D2 Advanced Convergence=0
UNET D2 WS Max Tol=0.15
UNET D2 WS RMS Tol=0.002
UNET D2 WS Stall Tol=1
UNET D2 Equation= 0
UNET D2 RampUpFraction=0.1
UNET D2 TimeSlices= 1
UNET D2 Turbulence Formulation=None
UNET D2 Eddy Viscosity=0.3
UNET D2 Transverse Eddy Viscosity=0.1
UNET D2 Smagorinsky Mixing=0.05
UNET D2 BCVolumeCheck=0
UNET D2 Cores=0
UNET D2 SolverType=PARDISO (Direct)
UNET D2 Minimum Iterations= 3
UNET D2 Maximum Iterations= 30
UNET D2 Restart Number= 10
UNET D2 Relaxation Coeff=1.3
UNET D2 SOR Precondition Iterations= 10
UNET D2 ILUT Maximum Fill= 8
UNET D2 ILUT Tolerance=1E-08
UNET D2 Convergence Tolerance=0.00001
PS Theta= 1
PS WS Tol= 0.01
PS Volume Tol= 0.01
PS Max Iterations= 20
PS Equation= 0
PS Advance Time Step=-1
PS Target Courant=0.9
PS Time Slices= 1
PS Iterate With 2D=0
PS Project Initial WSE from DS=-1
PS Ramp Up Initial WSE from US=-1
PS Cores=0
UNET D1D2 MaxIter= 0
UNET D1D2 ZTol=0.01
UNET D1D2 QTol=0.1
UNET D1D2 MinQTol=1
DSS File=dss
Write IC File= 0
Write IC File at Fixed DateTime=0
Write IC File at Sim End=0
Echo Input=False
Echo Parameters=False
Echo Output=False
Write Detailed= 0
HDF Write Warmup=0
HDF Write Time Slices=0
HDF Flush=0
HDF Compression= 1
HDF Chunk Size= 1
HDF Spatial Parts= 1
HDF Use Max Rows=0
HDF Fixed Rows= 1
Calibration Method= 0
Calibration Iterations= 20
Calibration Max Change=0.05
Calibration Tolerance=0.2
Calibration Maximum=1.5
Calibration Minimum=0.5
Calibration Optimization Method= 1
WQ AD Non Conservative
WQ ULTIMATE=-1
WQ Max Comp Step=1HOUR
WQ Output Interval=15MIN
WQ Output Selected Increments= 0
WQ Create Restart=0
WQ Fixed Restart=0
WQ System Summary=0
WQ Write To DSS=0
Sorting and Armoring Iterations= 10
XS Update Threshold= 0.02
Bed Roughness Predictor= 0
Processes Affected by Predictor=Sediment Only
Hydraulics Update Threshold= 0.02
Energy Slope Method= 1
Volume Change Method= 1
Sediment Retention Method= 0
Sediment TS Multiplier= 1
Warm Up Method= 0
XS Weighting Method= 0
Number of US Weighted Cross Sections= 1
Number of DS Weighted Cross Sections= 1
Upstream XS Weight=0
Main XS Weight=1
Downstream XS Weight=0
Number of DS XS's Weighted with US Boundary= 1
Upstream Boundary Weight= 1
Weight of XSs Associated with US Boundary= 0
Number of US XS's Weighted with DS Boundary= 1
Downstream Boundary Weight= 0.5
Weight of XSs Associated with DS Boundary= 0.5
Percentile Method= 0
Sediment Output Level= 3
Mass or Volume Output= 0
Output Increment Type= 1
Profile and TS Output Increment= 1
Transport Output Increment 1
XS Output Flag= 0
XS Output Increment= 10
Read HDF5 Sediment Hotstart= 0
Sediment Hotstart Type= 0
Write Gradation File= 0
Read Gradation Hotstart= 0
Write HDF5 File= 1
Write Binary Output= 1
Write DSS Sediment File= 0
DSS Sediment Output Type= 1
SV Curve= 0
Specific Gage Flag= 0
Subcell Erosion Methods= 0
Subcell Deposition Methods= 0
Advection Scheme= 1
Matrix Solver= 0
Implicit Weighting Factor= 1
Maximum Outer Loop Convergence Iterations= 5
Convergence Maximum Absolute= 0.001
Convergence RMSE= 0.0001
Grain Fractions Max Abs Error= 0.001
Max Subgrid Regions= 1
Max Subgrid Length Scale= 3.402823E+38
Initial Layer Thickness= 3
Min Layer Thickness= 0.1
Max Layer Thickness= 6
Number of Layers= 5

--- GrierSwamp.p02 (plan) ---

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Plan Title=Existing_Conditions
Short Identifier=EX
Geom File=g02
Flow File=f01

--- GrierSwamp.p03 (plan) ---

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Plan Title=Natural_Conditions
Short Identifier=NAT
Geom File=g03
Flow File=f01

--- GrierSwamp.p04 (plan) ---

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Plan Title=Sensitivity_Analysis
Short Identifier=Sensitivity
Geom File=g02
Flow File=f02

--- GrierSwamp.p05 (plan) ---

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Plan Title=Duplicate Effective
Short Identifier=DE
Geom File=g04
Flow File=f03

--- GrierSwamp.f01 (steady flow) ---

Flow Title=USGS Regression Equations
Program Version=6.60
Number of Profiles= 6
Profile Names=2yr,10yr,25yr,50yr,100yr,500yr
River Rch & RM=Grier Swamp,Reach-1         ,14977
     201     558     795    1020    1240    1810
Boundary for River Rch & Prof#=Grier Swamp,Reach-1         , 1
Up Type= 0
Dn Type= 3
Dn Slope=0.0014
Boundary for River Rch & Prof#=Grier Swamp,Reach-1         , 2
Up Type= 0
Dn Type= 3
Dn Slope=0.0014
Boundary for River Rch & Prof#=Grier Swamp,Reach-1         , 3
Up Type= 0
Dn Type= 3
Dn Slope=0.0014
Boundary for River Rch & Prof#=Grier Swamp,Reach-1         , 4
Up Type= 0
Dn Type= 3
Dn Slope=0.0014
Boundary for River Rch & Prof#=Grier Swamp,Reach-1         , 5
Up Type= 0
Dn Type= 3
Dn Slope=0.0014
Boundary for River Rch & Prof#=Grier Swamp,Reach-1         , 6
Up Type= 0
Dn Type= 3
Dn Slope=0.0014
DSS Import GetInterval= 0
DSS Import GetPeak= 0
DSS Import FillOption= 0

--- GrierSwamp.f02 (steady flow) ---

Flow Title=Sensitivity Analysis
Program Version=6.60
Number of Profiles= 3
Profile Names=-3ft,100yr,+3ft
River Rch & RM=Grier Swamp,Reach-1         ,14977
    1240    1240    1240
Boundary for River Rch & Prof#=Grier Swamp,Reach-1         , 1
Up Type= 0
Dn Type= 1
Dn Known WS=7.78
Boundary for River Rch & Prof#=Grier Swamp,Reach-1         , 2
Up Type= 0
Dn Type= 1
Dn Known WS=10.78
Boundary for River Rch & Prof#=Grier Swamp,Reach-1         , 3
Up Type= 0
Dn Type= 1
Dn Known WS=13.78
DSS Import GetInterval= 0
DSS Import GetPeak= 0
DSS Import FillOption= 0

--- GrierSwamp.f03 (steady flow) ---

Flow Title=FEMA Flows
Program Version=6.60
Number of Profiles= 1
Profile Names=100-year
River Rch & RM=Grier Swamp,Reach-1         ,19779
     461
River Rch & RM=Grier Swamp,Reach-1         ,17365
     833
River Rch & RM=Grier Swamp,Reach-1         ,13327
     887
River Rch & RM=Grier Swamp,Reach-1         ,11467
     940
River Rch & RM=Grier Swamp,Reach-1         ,8216
     997
River Rch & RM=Grier Swamp,Reach-1         ,5792
    1858
Boundary for River Rch & Prof#=Grier Swamp,Reach-1         , 1
Up Type= 0
Dn Type= 1
Dn Known WS=12.3
DSS Import GetInterval= 0
DSS Import GetPeak= 0
DSS Import FillOption= 0

--- GrierSwamp.g01 (geometry) ---

Geom Title=Proposed Conditions
Program Version=6.60

River Reach=Grier Swamp     ,Reach-1
Reach XY= 30
      2593496.26       757250.63      2593784.37       757012.86
      2593898.92       756755.99      2594215.99       756412.78
      2594459.48       755811.27       2594498.7       754973.74
      2594135.71       753597.58      2594102.85       752365.54
      2594206.18       751967.852594494.31873995 751656.52982276
2594623.35671283751405.157657143       2594660.5       751028.85
      2595057.35       750566.24      2595230.55       749788.99
        2595509.       749152.07      2595504.62       748879.32
      2595348.95       748487.96      2595340.18       748029.73
      2595410.34       747683.09      2595706.33       747198.99
      2595706.33       746795.57       2595596.7       746342.15
      2595789.64        746130.8      2596320.23       746043.54
      2596434.24       745839.63      2596521.94       745429.63
      2596480.28       745096.15      2595989.16       744271.11
      2596011.09       743771.22      2595887.48       743382.35

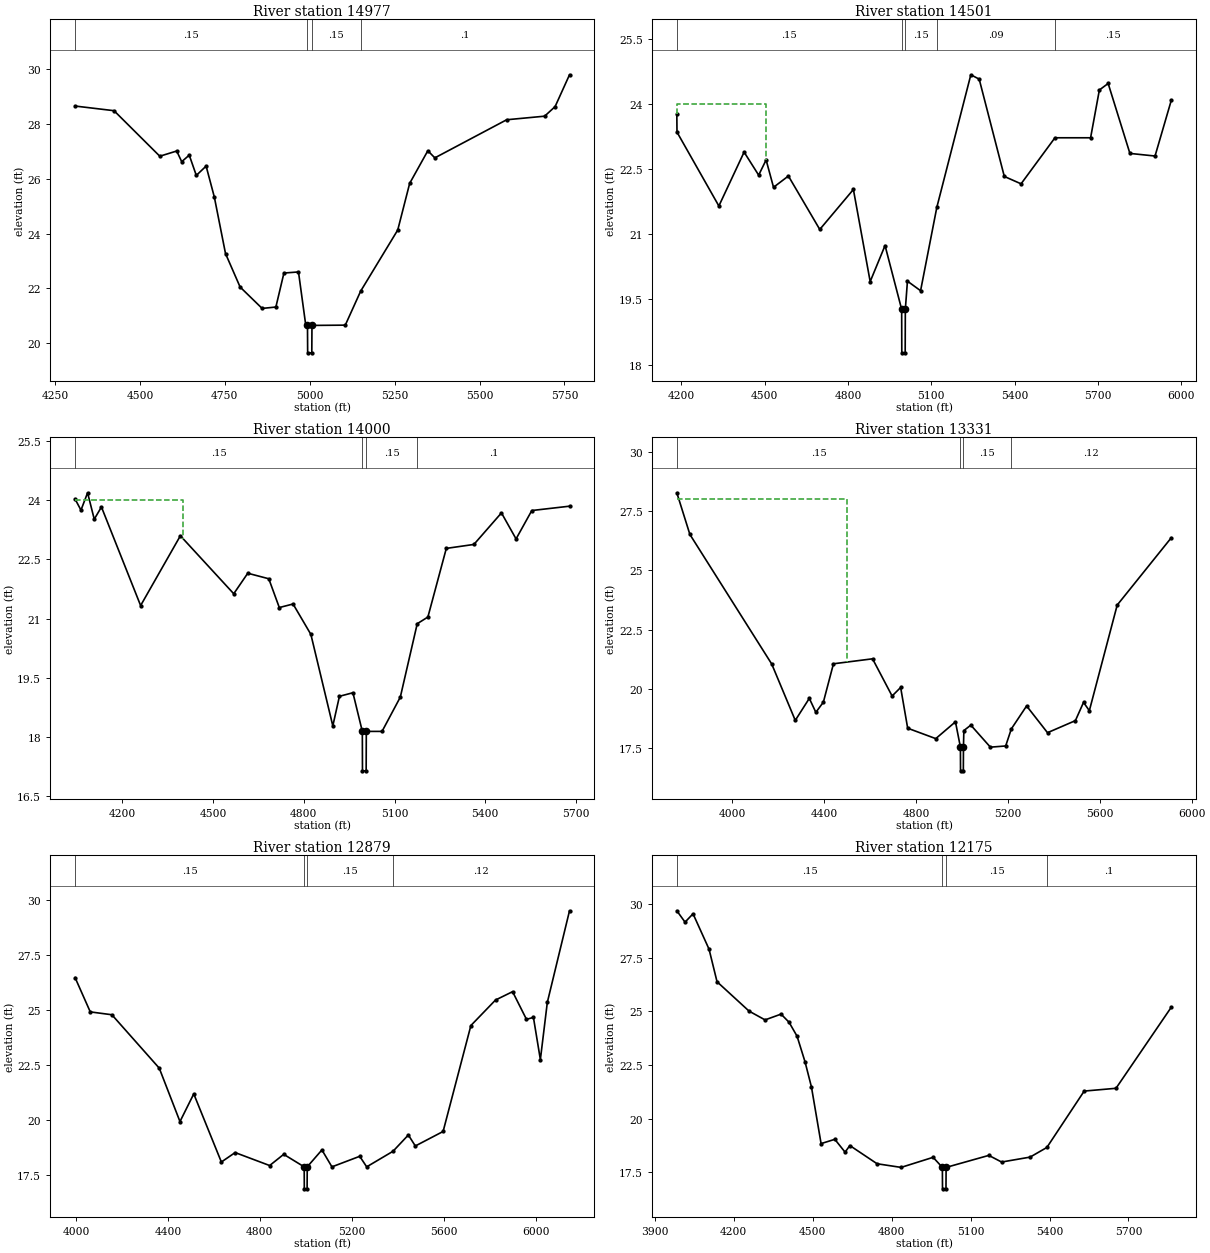
Type RM Length L Ch R = 1 ,14977   ,475.9,475.9,475.9
BEGIN DESCRIPTION:
Grier Swamp 21.0
END DESCRIPTION:
XS GIS Cut Line= 3
      2594463.24       757154.86      2593901.69       756752.19
      2593158.85       756569.39
#Sta/Elev= 30
    4309   28.65  4423.7   28.48  4558.5   26.82  4608.3   27.01    4623   26.62
  4645.2   26.86    4666   26.12  4694.9   26.46  4719.1   25.33    4752   23.27
    4795   22.05  4859.8   21.27  4900.3   21.32    4924   22.56  4966.9    22.6
  4988.4   20.65  4993.4   20.65  4993.9   19.65  5006.1   19.65  5006.6   20.65
  5104.7   20.66    5150    21.9  5259.2   24.13  5294.3   25.83  5347.8   27.02
  5368.4   26.76    5580   28.15  5691.7   28.28  5722.6   28.63    5765   29.79
#Mann= 4 ,-1,0
    4309     .15       0  4993.4     .05       0  5006.6     .15       0
    5150      .1       0
Bank Sta=4993.4,5006.6
XS Rating Curve= 0 ,0
Exp/Cntr=0.3,0.1

Type RM Length L Ch R = 1 ,14501   ,500.8,500.8,500.8
BEGIN DESCRIPTION:
Grier Swamp 20.0
END DESCRIPTION:
XS GIS Cut Line= 3
      2595030.03       756510.33      2594221.26       756404.22
      2593261.82       756314.78
#Sta/Elev= 30
  4184.3   23.77  4184.9   23.35  4335.6   21.65  4426.4   22.89  4478.8   22.36
  4505.6   22.71  4532.3   22.08  4585.8   22.34  4698.7   21.11  4819.7   22.03
  4880.1   19.91  4933.6   20.74  4993.4   19.27  4993.9   18.27  5006.1   18.27
  5006.6   19.27  5014.2   19.92  5061.5    19.7    5120   21.62  5242.3   24.67
  5272.4   24.57  5362.8   22.33  5423.1   22.16    5545   23.22  5673.3   23.22
  5704.9   24.32  5736.5   24.47  5814.8   22.86  5905.2    22.8  5963.6   24.08
#Mann= 5 ,-1,0
  4184.3     .15       0  4993.4     .05       0  5006.6     .15       0
    5120     .09       0    5545     .15       0
#XS Ineff= 2 , 0
            4505      24
Permanent Ineff=
       F       F
Bank Sta=4993.4,5006.6
XS Rating Curve= 0 ,0
Exp/Cntr=0.3,0.1

Type RM Length L Ch R = 1 ,14000   ,669.5,669.5,669.5
BEGIN DESCRIPTION:
Grier Swamp 19.0
END DESCRIPTION:
XS GIS Cut Line= 3
      2595252.57       756434.14       2594427.5       755949.86
      2593757.99       755838.58
#Sta/Elev= 30
  4043.3   24.03  4062.8   23.75  4084.7   24.19  4106.7   23.52  4130.5   23.83
  4260.1   21.33  4391.6    23.1  4568.1   21.63  4614.5   22.15    4684   22.01
  4718.8   21.28  4764.3   21.37  4823.2    20.6  4895.8   18.28  4917.7   19.03
  4962.3   19.12  4993.4   18.14  4993.9   17.14  5006.1   17.14  5006.6   18.14
  5058.6   18.14  5119.1   19.01    5175   20.87  5210.3   21.04  5271.2   22.78
  5362.4   22.88  5453.6   23.68  5501.9   23.02    5554   23.74  5678.7   23.85
#Mann= 4 ,-1,0
  4043.3     .15       0  4993.4     .05       0  5006.6     .15       0
    5175      .1       0
#XS Ineff= 2 , 0
            4400      24
Permanent Ineff=
       F       F
Bank Sta=4993.4,5006.6
XS Rating Curve= 0 ,0
Exp/Cntr=0.3,0.1

Type RM Length L Ch R = 1 ,13331   ,451.9,451.9,451.9
BEGIN DESCRIPTION:
Grier Swamp 18.0
END DESCRIPTION:
XS GIS Cut Line= 3
      2595715.77       755044.54      2594498.28       755285.48
      2593597.42       755422.31
#Sta/Elev= 30
  3758.9   28.28  3815.8   26.52    4172   21.05  4274.5   18.67  4335.6    19.6
  4364.1   19.01  4396.8   19.44  4440.7   21.06  4610.9   21.27    4696    19.7
  4733.2   20.06  4763.8   18.34  4886.1    17.9  4971.8   18.61  4993.4   17.54
  4993.9   16.54  5006.1   16.54  5006.6   17.54  5008.4   18.24  5038.7   18.47
  5123.8   17.54  5190.4   17.59    5215   18.31  5281.5   19.28  5372.5   18.15
  5493.9   18.66  5529.3   19.43  5554.6   19.08  5675.9   23.54  5911.2   26.38
#Mann= 4 ,-1,0
  3758.9     .15       0  4993.4     .05       0  5006.6     .15       0
    5215     .12       0
#XS Ineff= 2 , 0
            4500      28
Permanent Ineff=
       F       F
Bank Sta=4993.4,5006.6
XS Rating Curve= 0 ,0
Exp/Cntr=0.3,0.1

Type RM Length L Ch R = 1 ,12879   ,704.1,704.1,704.1
BEGIN DESCRIPTION:
Grier Swamp 17.0
END DESCRIPTION:
XS GIS Cut Line= 3
      2595486.08       754798.11      2594483.24        754834.6
      2593344.18       754975.98
#Sta/Elev= 30
  3996.5   26.46  4062.6    24.9  4156.6   24.77  4362.8   22.34  4452.9   19.91
  4512.9   21.17    4633   18.07    4693    18.5  4843.1   17.91  4904.3   18.42
  4993.4   17.85  4993.9   16.85  5006.1   16.85  5006.6   17.85  5070.5   18.62
  5114.1   17.85    5235   18.33  5265.3   17.85    5380   18.56  5446.6    19.3
  5476.9    18.8  5597.8   19.46  5718.7   24.28  5825.9   25.44  5900.1   25.82
  5960.6   24.56  5990.8   24.65    6021   22.73  6051.2   25.33  6147.8    29.5
#Mann= 4 ,-1,0
  3996.5     .15       0  4993.4     .05       0  5006.6     .15       0
    5380     .12       0
Bank Sta=4993.4,5006.6
XS Rating Curve= 0 ,0
Exp/Cntr=0.3,0.1

Type RM Length L Ch R = 1 ,12175   ,703.9,703.9,703.9
BEGIN DESCRIPTION:
Grier Swamp 16.0
END DESCRIPTION:
XS GIS Cut Line= 3
      2595300.78       753990.28      2594298.25       754156.43
      2593441.37       754256.44
#Sta/Elev= 30
  3983.8   29.69    4015   29.16  4045.4   29.55  4106.2    27.9  4136.6   26.38
  4258.3   25.01  4319.1    24.6  4379.9   24.87  4410.3   24.49  4440.7   23.84
  4471.1   22.64  4495.4   21.47    4532   18.83  4584.2   19.03  4623.2   18.43
  4641.2   18.74  4744.8   17.89    4836   17.72  4957.7   18.19  4992.9   17.72
  4993.4   16.72  5006.6   16.72  5007.1   17.72  5169.4   18.28    5218   17.97
  5326.2    18.2    5390   18.65  5531.8   21.28  5652.7   21.41  5862.7   25.19
#Mann= 4 ,-1,0
  3983.8     .15       0  4992.9     .05       0  5007.1     .15       0
    5390      .1       0
Bank Sta=4992.9,5007.1
XS Rating Curve= 0 ,0
Exp/Cntr=0.3,0.1

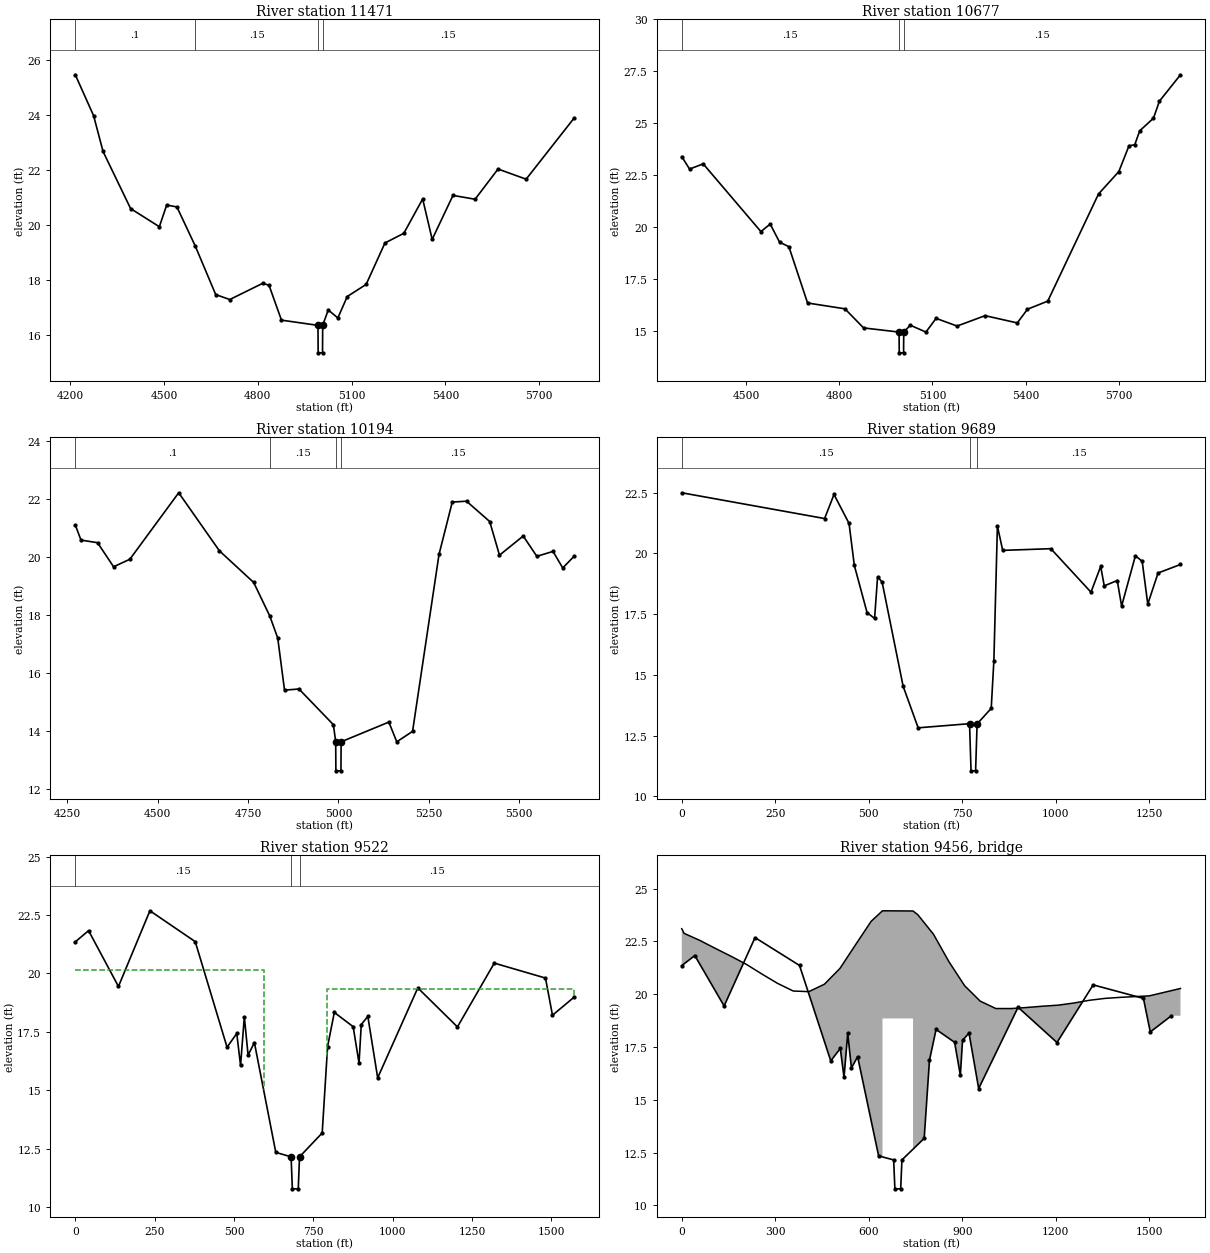
Type RM Length L Ch R = 1 ,11471   ,793.6,793.6,793.6
BEGIN DESCRIPTION:
Grier Swamp 15.0
END DESCRIPTION:
XS GIS Cut Line= 3
      2594908.59        753444.5      2594125.76       753477.07
      2593318.18       753552.49
#Sta/Elev= 30
  4216.5   25.46  4275.1   23.97  4305.2   22.67  4393.4   20.59  4485.3   19.93
  4508.7   20.72  4541.4   20.65    4600   19.23  4665.5   17.46  4710.5   17.28
  4815.6   17.87  4835.9    17.8  4875.7   16.53  4992.5   16.34    4993   15.34
    5007   15.34  5007.5   16.34  5025.3    16.9    5056   16.61  5086.1   17.39
  5146.4   17.83  5206.7   19.34  5266.9   19.69  5327.2   20.94  5357.6   19.47
  5424.1   21.07  5494.8   20.93  5568.2   22.03    5658   21.66  5811.1   23.88
#Mann= 4 ,-1,0
  4216.5      .1       0    4600     .15       0  4992.5     .05       0
  5007.5     .15       0
Bank Sta=4992.5,5007.5
XS Rating Curve= 0 ,0
Exp/Cntr=0.3,0.1

Type RM Length L Ch R = 1 ,10677   ,482.9,482.9,482.9
BEGIN DESCRIPTION:
Grier Swamp 14.0
END DESCRIPTION:
XS GIS Cut Line= 3
      2594804.25       752646.99      2594098.51       752683.93
      2593203.39       752754.46
#Sta/Elev= 30
  4293.3   23.39  4318.4   22.79  4362.3   23.04  4547.9   19.78  4577.9   20.14
    4608   19.27    4638   19.05  4698.1   16.34  4818.3   16.06  4878.3   15.14
  4992.5   14.94    4993   13.94    5007   13.94  5007.5   14.94  5028.6   15.27
  5078.9   14.94  5111.6    15.6  5179.1   15.23  5269.3   15.73  5372.9   15.38
  5405.6   16.04  5470.9   16.43  5634.2   21.59  5699.6   22.67  5732.2   23.91
  5750.8   23.96  5766.7   24.63    5811   25.24  5830.2   26.06  5897.9   27.33
#Mann= 3 ,-1,0
  4293.3     .15       0  4992.5     .05       0  5007.5     .15       0
Bank Sta=4992.5,5007.5
XS Rating Curve= 0 ,0
Exp/Cntr=0.3,0.1

Type RM Length L Ch R = 1 ,10194   ,504.8,504.8,504.8
BEGIN DESCRIPTION:
Grier Swamp 13.0
END DESCRIPTION:
XS GIS Cut Line= 3
      2594785.66       752515.44      2594128.37       752203.16
      2593570.21       751866.95
#Sta/Elev= 30
  4272.3   21.11  4288.1   20.59  4333.9    20.5  4378.2   19.67  4423.2   19.93
  4558.3   22.22  4670.9   20.22  4765.7   19.13    4810   17.98  4832.1   17.22
    4851   15.42  4890.9   15.46  4986.1   14.23  4992.5   13.64    4993   12.64
    5007   12.64  5007.5   13.64  5139.5   14.32  5161.4   13.64  5205.1      14
  5278.3    20.1  5314.9    21.9  5354.3   21.93  5418.4   21.23  5445.5   20.07
  5511.1   20.73  5548.8   20.03  5593.5    20.2  5620.4   19.63  5651.6   20.03
#Mann= 4 ,-1,0
  4272.3      .1       0    4810     .15       0  4992.5     .05       0
  5007.5     .15       0
Bank Sta=4992.5,5007.5
XS Rating Curve= 0 ,0
Exp/Cntr=0.3,0.1

Type RM Length L Ch R = 1 ,9689    ,167.7,167.7,167.7
BEGIN DESCRIPTION:
Grier Swamp 12.0
END DESCRIPTION:
XS GIS Cut Line= 3
      2595011.74       752226.42      2594389.35       751786.09
      2593917.15       751464.52
#Sta/Elev= 30
       0   22.49     382   21.43  407.17   22.42  447.35   21.23  461.51    19.5
  495.58   17.56  515.66   17.32   523.7   19.03  535.75   18.82  592.01   14.53
  632.19   12.82   769.6   12.99   773.6   11.05   785.8   11.05   789.8   12.98
  827.59   13.62  834.68   15.58  844.13   21.12  858.28   20.12  986.99   20.19
 1094.37    18.4 1120.34   19.46 1129.86   18.66 1164.62   18.88 1176.28   17.83
  1213.2    19.9 1231.29   19.67 1246.21   17.91 1273.79   19.19  1333.7   19.54
#Mann= 3 ,0,0
       0     .15       0   769.6     .05       0   789.8     .15       0
Bank Sta=769.6,789.8
XS Rating Curve= 0 ,0
Exp/Cntr=0.5,0.3

Type RM Length L Ch R = 1 ,9522    ,139.1,139.1,139.1
BEGIN DESCRIPTION:
Grier Swamp (HWY-65) US
END DESCRIPTION:
XS GIS Cut Line= 3
      2595067.33       752052.27      2594467.58       751644.94
      2593807.35       751103.57
#Sta/Elev= 30
       0   21.35   41.86   21.83  135.94   19.44  235.07   22.68  377.81   21.36
  478.07   16.84  508.66   17.43  520.59   16.06  532.45   18.14  544.35    16.5
  564.17   17.04  631.58   12.34  679.79   12.15  683.79   10.78  702.36   10.78
  706.36   12.15  777.77   13.17  794.74   16.87  815.95   18.33  875.33   17.72
  893.81   16.16  900.83   17.81  921.52   18.16  952.56   15.53 1078.95   19.38
  1203.8   17.71 1319.86   20.44 1481.16    19.8 1503.14   18.21 1571.01   18.98
#Mann= 3 ,0,0
       0     .15       0  679.79     .05       0  706.36     .15       0
#XS Ineff= 2 , 0
          593.24   20.13  792.76           19.33
Permanent Ineff=
       F       F
Bank Sta=679.79,706.36
XS Rating Curve= 0 ,0
Exp/Cntr=0.5,0.3

Type RM Length L Ch R = 3 ,9456    ,,,
BEGIN DESCRIPTION:
Grier Swamp (HWY-65) TOR
Structure ID: LDS_GRS_01
Approximate Survey Structure
END DESCRIPTION:
Bridge Culvert--1,0,-1,-1, 0
Deck Dist Width WeirC Skew NumUp NumDn MinLoCord MaxHiCord MaxSubmerge Is_Ogee
50.76013,42.75,3,0, 34, 35, , , 0.95, 0, 2,2,,
       0    7.54   57.54  107.54  157.54  207.54  257.54  307.54  357.54  407.54
  457.54  507.54  557.54  607.54  643.99     644     742  742.01  757.54  807.54
  857.54  907.54  957.54 1007.54 1057.54 1107.54 1157.54 1207.54 1257.54 1307.54
 1357.54 1407.54    1500    1600
    23.1   22.88   22.55   22.17    21.8   21.41   20.95   20.51   20.15   20.12
   20.47   21.22   22.34   23.45   23.95   23.95   23.94   23.94   23.76   22.84
   21.53    20.4   19.67   19.32   19.32   19.37   19.43   19.48   19.58   19.71
    19.8   19.85   19.92   20.27
                                                                                
                                           18.85   18.85
                                                                                
                                
       0   13.74   63.74  113.74  163.74  213.74  263.74  313.74  363.74  413.74
  463.74  513.74  563.74  613.74  663.74  700.19   700.2   798.2  798.21  813.74
  863.74  913.74  963.74 1013.74 1063.74 1113.74 1163.74 1213.74 1263.74 1313.74
 1363.74 1413.74 1463.74    1500    1600
    23.1    23.1   22.88   22.55   22.17    21.8   21.41   20.95   20.51   20.15
   20.12   20.47   21.22   22.34   23.45   23.95   23.95   23.94   23.94   23.76
   22.84   21.53    20.4   19.67   19.32   19.32   19.37   19.43   19.48   19.58
   19.71    19.8   19.85   19.92   20.27
                                                                                
                                                   18.85   18.85
                                                                                
                                        
Abutment Skew #Up #Dn= , 3 , 3
  643.99     646  656.08
   17.19   17.19   12.15
  700.19   702.2  712.28
   17.19   17.19   12.15
Abutment Skew #Up #Dn= , 3 , 3
  729.98     740  742.01
   12.18   17.19   17.19
  786.18   796.2  798.21
   12.18   17.19   17.19
BR Coef=-1 ,-1 , 0 ,0.9, 0 ,,,0.8,0,1.2,0,
WSPro=,,,, 1 ,,,, 0 ,,,, 0 ,,,,-1 ,-1 ,-1 , 0 , 0 , 0 , 0 , 0
BC Design=,, 0 ,, 0 ,,,,,,
BC HTab HWMax=25
BC Use User HTab Curves=0
BC User HTab FreeFlow(D)= 0

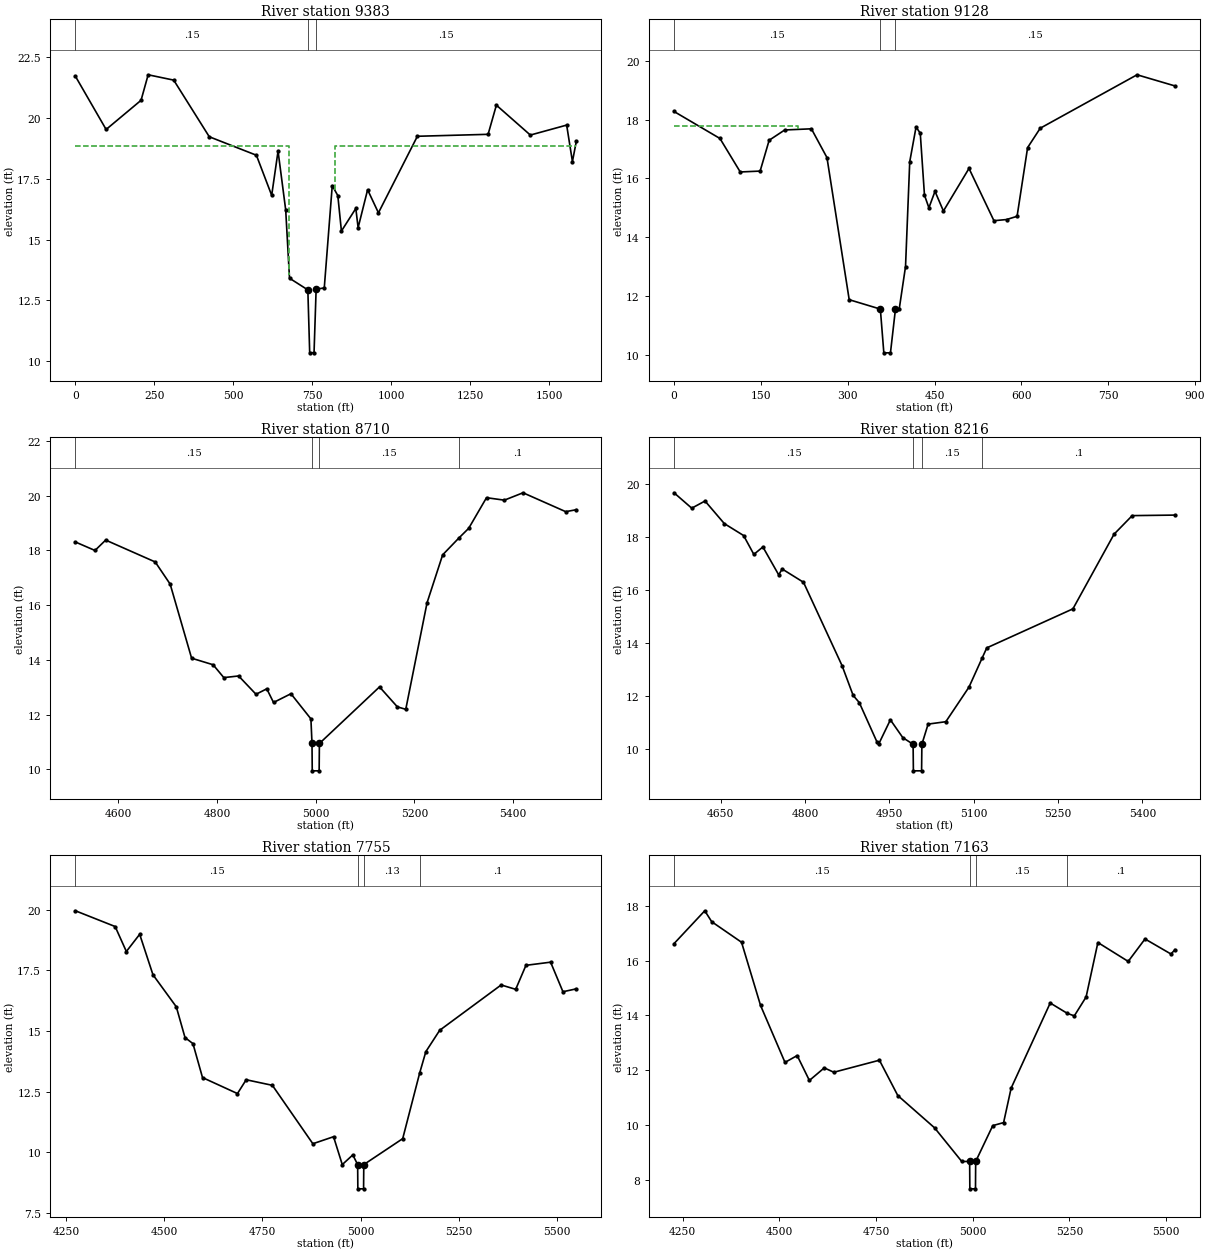
Type RM Length L Ch R = 1 ,9383    ,254.2,254.2,254.2
BEGIN DESCRIPTION:
Grier Swamp (HWY-65) DS
END DESCRIPTION:
XS GIS Cut Line= 3
      2595148.81       751970.71      2594553.22       751544.64
      2593877.77       751022.06
#Sta/Elev= 30
       0   21.72   97.29   19.53  207.91   20.73  230.38   21.78  311.36   21.56
  423.97   19.23  573.19   18.47  621.59   16.82  641.76   18.64  665.96   16.22
  678.05   13.41  736.09   12.93  741.96   10.34  755.74   10.35  762.35   12.96
  788.11   13.01  813.38   17.22     831   16.81  842.41   15.35  888.03   16.28
  895.32   15.49  925.36   17.05  959.65    16.1 1082.95   19.25  1306.9   19.33
 1333.14   20.53  1440.7    19.3 1555.74   19.71 1573.98   18.21  1586.3   19.04
#Mann= 3 ,0,0
       0     .15       0  736.09     .05       0  762.35     .15       0
#XS Ineff= 2 , 0
          677.41   18.86     821           18.86
Permanent Ineff=
       F       F
Bank Sta=736.09,762.35
XS Rating Curve= 0 ,0
Exp/Cntr=0.5,0.3

Type RM Length L Ch R = 1 ,9128    ,418.1,418.1,418.1
BEGIN DESCRIPTION:
Grier Swamp 11.0
END DESCRIPTION:
XS GIS Cut Line= 3
      2594954.16       751505.83      2594651.38       751321.46
      2594190.59       751101.25
#Sta/Elev= 30
       0   18.28   79.34   17.36  114.37   16.22  148.72   16.25   164.3    17.3
  191.18   17.65  237.27   17.69  264.15   16.71  302.56   11.87  356.36   11.55
  362.38   10.06  373.82   10.06  382.51   11.56  388.94   11.55  399.85      13
  407.12   16.57  418.03   17.75   425.3   17.54  432.57   15.43  440.22      15
  450.75   15.56  465.29   14.89  509.48   16.34  552.54   14.56  574.35    14.6
  592.53   14.71  610.71   17.05  632.52   17.71  799.75   19.53   865.2   19.15
#Mann= 3 ,0,0
       0     .15       0  356.36     .05       0  382.51     .15       0
#XS Ineff= 2 , 0
          214.23   17.79  418.03           17.75
Permanent Ineff=
       F       F
Bank Sta=356.36,382.51
XS Rating Curve= 0 ,0
Exp/Cntr=0.3,0.1

Type RM Length L Ch R = 1 ,8710    ,494.3,494.3,494.3
BEGIN DESCRIPTION:
Grier Swamp 10.0
END DESCRIPTION:
XS GIS Cut Line= 3
      2595130.75       751183.88      2594717.42       750925.96
       2594278.9       750631.17
#Sta/Elev= 30
  4512.8   18.31  4552.5      18  4574.2   18.38  4674.6   17.58  4704.9   16.77
  4748.4   14.06    4792   13.82  4813.7   13.35  4843.7   13.41    4879   12.74
  4900.8   12.94  4914.5   12.44  4949.8   12.76  4990.3   11.84  4992.5   10.94
    4993    9.94    5007    9.94  5007.5   10.94  5129.4   13.01  5165.6   12.28
  5182.6   12.19  5225.8   16.09  5257.4   17.84    5290   18.45  5310.2   18.81
  5346.3   19.93  5382.5   19.84  5420.4   20.11  5506.8   19.42  5528.4   19.49
#Mann= 4 ,-1,0
  4512.8     .15       0  4992.5     .05       0  5007.5     .15       0
    5290      .1       0
Bank Sta=4992.5,5007.5
XS Rating Curve= 0 ,0
Exp/Cntr=0.3,0.1

Type RM Length L Ch R = 1 ,8216    ,461,461,461
BEGIN DESCRIPTION:
Grier Swamp 9.0
END DESCRIPTION:
XS GIS Cut Line= 3
      2595264.63       750948.24       2595055.1       750569.42
       2594629.3       750401.27
#Sta/Elev= 30
  4567.1   19.66  4598.6   19.08  4622.2   19.35  4656.5    18.5  4690.8   18.05
    4709   17.34  4725.1   17.62  4753.2   16.57  4759.4   16.79  4797.3   16.29
  4865.9   13.15  4885.6   12.03  4896.5   11.76  4927.9   10.28  4930.8   10.19
  4951.8   11.11  4973.9   10.44  4992.2   10.19  4992.7    9.19  5007.3    9.19
  5007.8   10.19  5018.9   10.95  5050.4   11.04  5091.5   12.34    5115   13.44
  5123.2   13.82  5276.4   15.29  5349.5    18.1  5381.8    18.8  5457.8   18.82
#Mann= 4 ,-1,0
  4567.1     .15       0  4992.2     .05       0  5007.8     .15       0
    5115      .1       0
Bank Sta=4992.2,5007.8
XS Rating Curve= 0 ,0
Exp/Cntr=0.3,0.1

Type RM Length L Ch R = 1 ,7755    ,592,592,592
BEGIN DESCRIPTION:
Grier Swamp 8.0
END DESCRIPTION:
XS GIS Cut Line= 3
      2595804.72        750471.8      2595162.22       750134.41
      2594637.43       749975.24
#Sta/Elev= 30
  4274.3   19.96  4375.4   19.31  4403.9   18.28  4437.8   18.99  4471.6   17.32
  4530.9      16  4553.1   14.73  4573.3   14.48  4597.6   13.08  4686.5   12.42
  4708.7   12.99  4775.3   12.76  4878.3   10.35  4930.9   10.64  4953.1    9.49
  4979.9    9.89  4992.2    9.49  4992.7    8.49  5007.3    8.49  5007.8    9.49
  5106.8   10.56    5150   13.27  5165.7   14.15  5200.9   15.03  5357.2    16.9
  5394.2   16.72  5420.3   17.71    5483   17.84  5514.4   16.62  5548.4   16.74
#Mann= 4 ,-1,0
  4274.3     .15       0  4992.2     .05       0  5007.8     .13       0
    5150      .1       0
Bank Sta=4992.2,5007.8
XS Rating Curve= 0 ,0
Exp/Cntr=0.3,0.1

Type RM Length L Ch R = 1 ,7163    ,544,544,544
BEGIN DESCRIPTION:
Grier Swamp 7.0
END DESCRIPTION:
XS GIS Cut Line= 3
      2596082.64       749827.76      2595348.78       749586.79
      2594833.83       749494.25
#Sta/Elev= 30
  4227.6   16.62  4307.1   17.82  4325.1   17.42  4402.2   16.67  4451.4   14.36
  4514.6   12.28  4546.1   12.53  4577.7   11.62  4616.2   12.08  4640.9   11.92
  4758.8   12.36  4806.3   11.07  4901.4    9.89  4971.8    8.66  4992.2    8.66
  4992.7    7.66  5007.3    7.66  5007.8    8.66    5052    9.97    5080   10.08
  5099.5   11.34  5200.6   14.45    5245   14.07  5262.9   13.98  5293.4   14.67
  5323.9   16.66  5402.3   15.97  5445.8   16.79  5512.9   16.24  5523.2    16.4
#Mann= 4 ,-1,0
  4227.6     .15       0  4992.2     .05       0  5007.8     .15       0
    5245      .1       0
Bank Sta=4992.2,5007.8
XS Rating Curve= 0 ,0
Exp/Cntr=0.3,0.1

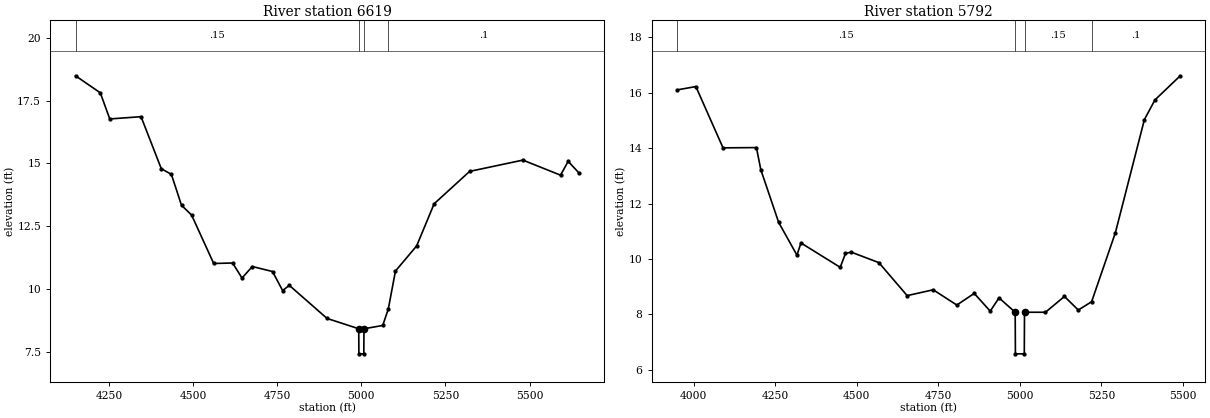
Type RM Length L Ch R = 1 ,6619    ,827,827,827
BEGIN DESCRIPTION:
Grier Swamp 6.0
END DESCRIPTION:
XS GIS Cut Line= 3
      2596364.29       749134.44      2595516.61       749074.51
      2594900.55       749271.54
#Sta/Elev= 30
  4150.2   18.49  4223.9   17.81    4252   16.77    4345   16.86  4405.1   14.79
  4435.2   14.56  4465.3   13.33  4495.3   12.94    4561   11.01  4617.2   11.03
  4645.2   10.43  4675.8   10.89  4735.9   10.69    4766    9.93  4785.7   10.14
  4898.1    8.82  4992.2    8.41  4992.7    7.41  5007.3    7.41  5007.8    8.41
  5063.5    8.54    5080    9.19  5101.4   10.71  5164.4   11.71  5216.4   13.39
  5321.9   14.68  5480.2   15.13  5592.2   14.53  5614.9   15.08  5646.8   14.62
#Mann= 4 ,-1,0
  4150.2     .15       0  4992.2     .05       0  5007.8     .15       0
    5080      .1       0
Bank Sta=4992.2,5007.8
XS Rating Curve= 0 ,0
Exp/Cntr=0.3,0.1

Type RM Length L Ch R = 1 ,5792    ,0,0,0
BEGIN DESCRIPTION:
Grier Swamp 5.0
END DESCRIPTION:
XS GIS Cut Line= 3
      2596264.34       748784.69      2595340.18       748283.33
      2594900.72       748062.77
#Sta/Elev= 30
  3948.6    16.1  4006.9   16.22  4090.1   14.01  4192.5   14.02    4206   13.22
  4260.7   11.32  4316.7   10.14    4329   10.58  4449.4     9.7  4465.5    10.2
  4482.7   10.25  4567.9    9.87  4654.5    8.68  4734.4    8.89  4806.8    8.34
  4860.2    8.76  4909.2    8.12  4936.2     8.6  4985.7    8.08  4986.4    6.58
  5013.6    6.58  5014.3    8.08  5078.5    8.08  5136.7    8.65  5179.2    8.16
    5220    8.46  5292.9   10.95  5381.8   15.03  5414.2   15.74  5491.7   16.61
#Mann= 4 ,-1,0
  3948.6     .15       0  4985.7     .05       0  5014.3     .15       0
    5220      .1       0
Bank Sta=4985.7,5014.3
XS Rating Curve= 0 ,0
Exp/Cntr=0.3,0.1
LCMann Table=0

Chan Stop Cuts=-1
Use User Specified Reach Order=0
Composite Channel Slope=5

--- GrierSwamp.g02 (geometry) ---

Geom Title=Existing Conditions
Program Version=6.60

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
River Reach=Grier Swamp     ,Reach-1

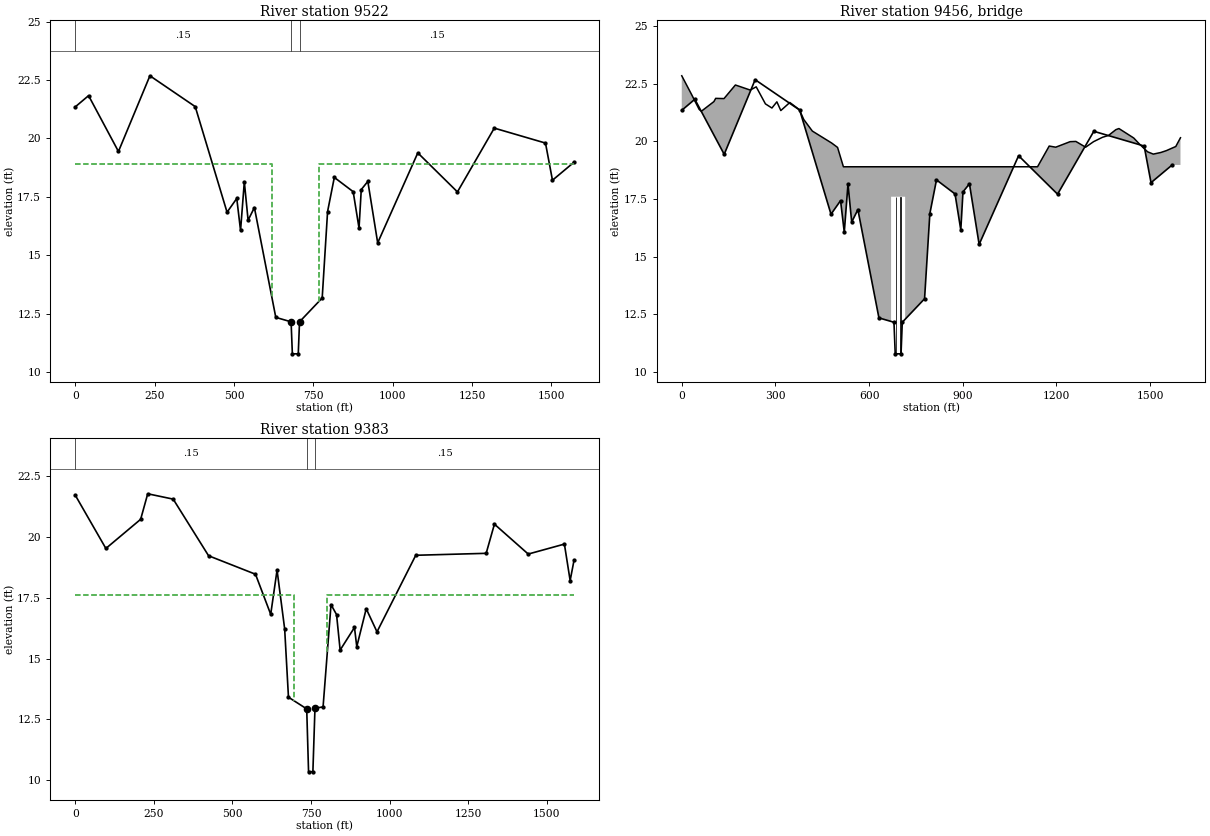
Type RM Length L Ch R = 1 ,9522    ,139.1,139.1,139.1
BEGIN DESCRIPTION:
Grier Swamp (HWY-65) US
END DESCRIPTION:
XS GIS Cut Line= 3
      2595067.33       752052.27      2594467.58       751644.94
      2593807.35       751103.57
#Sta/Elev= 30
       0   21.35   41.86   21.83  135.94   19.44  235.07   22.68  377.81   21.36
  478.07   16.84  508.66   17.43  520.59   16.06  532.45   18.14  544.35    16.5
  564.17   17.04  631.58   12.34  679.79   12.15  683.79   10.78  702.36   10.78
  706.36   12.15  777.77   13.17  794.74   16.87  815.95   18.33  875.33   17.72
  893.81   16.16  900.83   17.81  921.52   18.16  952.56   15.53 1078.95   19.38
  1203.8   17.71 1319.86   20.44 1481.16    19.8 1503.14   18.21 1571.01   18.98
#Mann= 3 ,0,0
       0     .15       0  679.79     .05       0  706.36     .15       0
#XS Ineff= 2 , 0
       0   619.5    18.9   766.5       0    18.9
Permanent Ineff=
       F       F
Bank Sta=679.79,706.36
XS Rating Curve= 0 ,0
Exp/Cntr=0.5,0.3

Type RM Length L Ch R = 3 ,9456    ,,,
BEGIN DESCRIPTION:
Grier Swamp (HWY-65) TOR
Structure ID: LDS_GRS_01
Approximate Survey Structure
END DESCRIPTION:
Bridge Culvert--1,0,-1,-1, 0
Deck Dist Width WeirC Skew NumUp NumDn MinLoCord MaxHiCord MaxSubmerge Is_Ogee
51.26013,28,3,0, 44, 43, , , 0.95, 0, 2,2,,
       0    31.8    55.7    62.7     103   108.7   135.3   171.8   219.3   238.5
     268   288.8   304.7   317.3   346.1   376.7   390.9   418.3   480.3   499.1
   517.8  670.49   670.5   715.5  715.51  1139.6    1177  1197.9    1244  1262.4
  1293.7  1319.1  1347.7    1367  1390.4  1400.3  1447.7  1465.8  1492.1  1510.5
  1534.4  1552.1  1582.4  1597.5
   22.85   22.03   21.39   21.31   21.73   21.87   21.86   22.45   22.23   22.37
   21.63   21.45   21.72   21.34   21.69   21.38   20.95   20.45   19.93   19.74
    18.9    18.9    18.9    18.9    18.9    18.9    19.8   19.75   19.99      20
   19.75   19.99   20.18   20.26   20.51   20.56   20.15   19.89   19.55   19.45
   19.52    19.6   19.78   20.16
                                                                                
                                                                                
                    17.6    17.6
                                                                                
                                
       0    31.8    55.7    62.7     103   108.7   135.3   171.8   219.3   238.5
     268   288.8   304.7   317.3   346.1   376.7   390.9   418.3   480.3   499.1
   517.8  726.69   726.7   771.7  771.71    1177  1197.9    1244  1262.4  1293.7
  1319.1  1347.7    1367  1390.4  1400.3  1447.7  1465.8  1492.1  1510.5  1534.4
  1552.1  1582.4  1597.5
   22.85   22.03   21.39   21.31   21.73   21.87   21.86   22.45   22.23   22.37
   21.63   21.45   21.72   21.34   21.69   21.38   20.95   20.45   19.93   19.74
    18.9    18.9    18.9    18.9    18.9    18.9   19.75   19.99      20   19.75
   19.99   20.18   20.26   20.51   20.56   20.15   19.89   19.55   19.45   19.52
    19.6   19.78   20.16
                                                                                
                                                                                
                    17.6    17.6
                                                                                
                        
Pier Skew, UpSta & Num, DnSta & Num=  ,685.5, 2 ,741.7, 2 , 0 , 0 , 0 ,0,0
       1       1
    10.2    18.6
       1       1
    9.95    18.6
Pier Skew, UpSta & Num, DnSta & Num=  ,700.5, 2 ,756.7, 2 , 0 , 0 , 0 ,0,0
       1       1
    10.2    18.6
       1       1
    9.95    18.6
BR Coef=-1 ,-1 ,-1 ,0.9, 0 ,,,0.8,0,1.2,0,
WSPro=,,,, 1 ,,,, 0 ,,,, 0 ,,,,-1 ,-1 ,-1 , 0 , 0 , 0 , 0 , 0
BC Design=,, 0 ,, 0 ,,,,,,
BC HTab HWMax=22.8
BC Use User HTab Curves=0
BC User HTab FreeFlow(D)= 0

Type RM Length L Ch R = 1 ,9383    ,254.2,254.2,254.2
BEGIN DESCRIPTION:
Grier Swamp (HWY-65) DS
END DESCRIPTION:
XS GIS Cut Line= 3
      2595148.81       751970.71      2594553.22       751544.64
      2593877.77       751022.06
#Sta/Elev= 30
       0   21.72   97.29   19.53  207.91   20.73  230.38   21.78  311.36   21.56
  423.97   19.23  573.19   18.47  621.59   16.82  641.76   18.64  665.96   16.22
  678.05   13.41  736.09   12.93  741.96   10.34  755.74   10.35  762.35   12.96
  788.11   13.01  813.38   17.22     831   16.81  842.41   15.35  888.03   16.28
  895.32   15.49  925.36   17.05  959.65    16.1 1082.95   19.25  1306.9   19.33
 1333.14   20.53  1440.7    19.3 1555.74   19.71 1573.98   18.21  1586.3   19.04
#Mann= 3 ,0,0
       0     .15       0  736.09     .05       0  762.35     .15       0
#XS Ineff= 2 , 0
       0   696.7    17.6   801.7       0    17.6
Permanent Ineff=
       F       F
Bank Sta=736.09,762.35
XS Rating Curve= 0 ,0
Exp/Cntr=0.5,0.3

--- GrierSwamp.g03 (geometry) ---

Geom Title=Natural Conditions
Program Version=6.60

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
River Reach=Grier Swamp     ,Reach-1

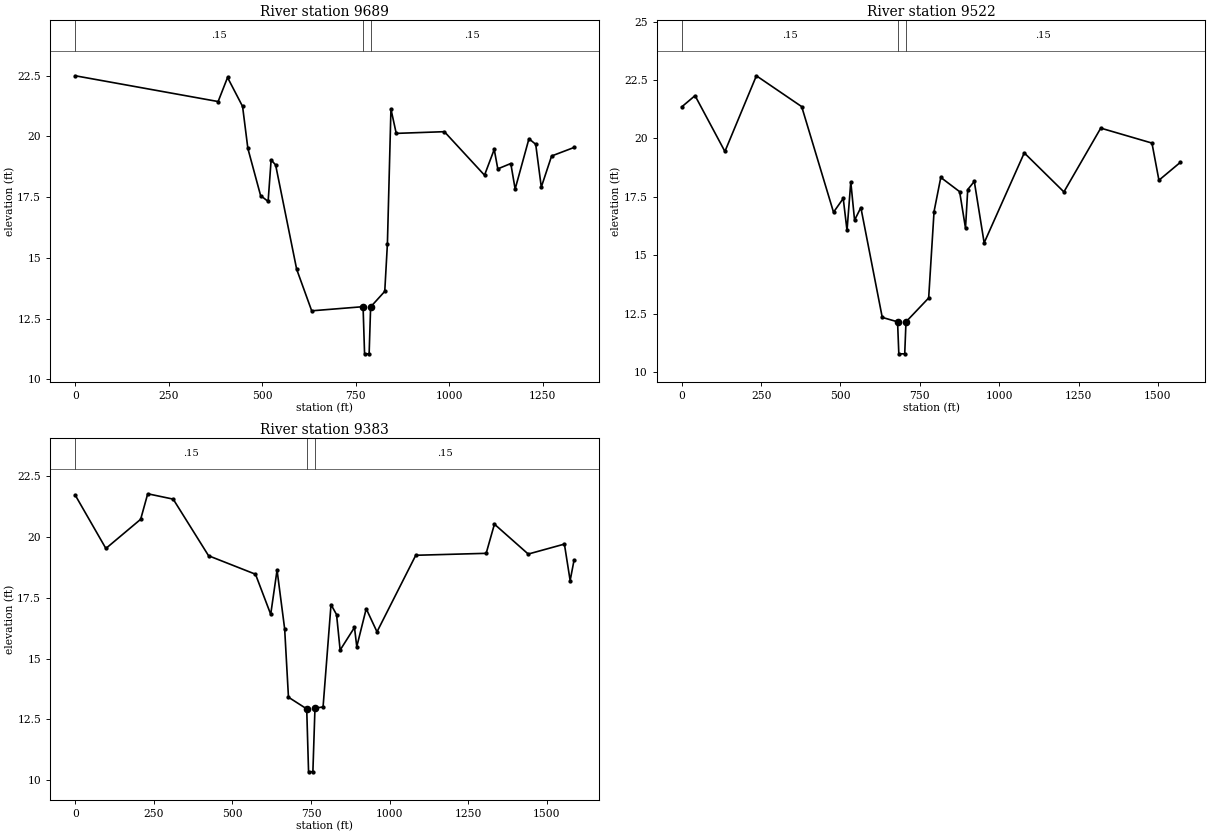
Type RM Length L Ch R = 1 ,9689    ,167.7,167.7,167.7
BEGIN DESCRIPTION:
Grier Swamp 12.0
END DESCRIPTION:
XS GIS Cut Line= 3
      2595011.74       752226.42      2594389.35       751786.09
      2593917.15       751464.52
#Sta/Elev= 30
       0   22.49     382   21.43  407.17   22.42  447.35   21.23  461.51    19.5
  495.58   17.56  515.66   17.32   523.7   19.03  535.75   18.82  592.01   14.53
  632.19   12.82   769.6   12.99   773.6   11.05   785.8   11.05   789.8   12.98
  827.59   13.62  834.68   15.58  844.13   21.12  858.28   20.12  986.99   20.19
 1094.37    18.4 1120.34   19.46 1129.86   18.66 1164.62   18.88 1176.28   17.83
  1213.2    19.9 1231.29   19.67 1246.21   17.91 1273.79   19.19  1333.7   19.54
#Mann= 3 ,0,0
       0     .15       0   769.6     .05       0   789.8     .15       0
Bank Sta=769.6,789.8
XS Rating Curve= 0 ,0
Exp/Cntr=0.3,0.1

Type RM Length L Ch R = 1 ,9522    ,139.1,139.1,139.1
BEGIN DESCRIPTION:
Grier Swamp (HWY-65) US
END DESCRIPTION:
XS GIS Cut Line= 3
      2595067.33       752052.27      2594467.58       751644.94
      2593807.35       751103.57
#Sta/Elev= 30
       0   21.35   41.86   21.83  135.94   19.44  235.07   22.68  377.81   21.36
  478.07   16.84  508.66   17.43  520.59   16.06  532.45   18.14  544.35    16.5
  564.17   17.04  631.58   12.34  679.79   12.15  683.79   10.78  702.36   10.78
  706.36   12.15  777.77   13.17  794.74   16.87  815.95   18.33  875.33   17.72
  893.81   16.16  900.83   17.81  921.52   18.16  952.56   15.53 1078.95   19.38
  1203.8   17.71 1319.86   20.44 1481.16    19.8 1503.14   18.21 1571.01   18.98
#Mann= 3 ,0,0
       0     .15       0  679.79     .05       0  706.36     .15       0
Bank Sta=679.79,706.36
XS Rating Curve= 0 ,0
Exp/Cntr=0.3,0.1

Type RM Length L Ch R = 1 ,9383    ,254.2,254.2,254.2
BEGIN DESCRIPTION:
Grier Swamp (HWY-65) DS
END DESCRIPTION:
XS GIS Cut Line= 3
      2595148.81       751970.71      2594553.22       751544.64
      2593877.77       751022.06
#Sta/Elev= 30
       0   21.72   97.29   19.53  207.91   20.73  230.38   21.78  311.36   21.56
  423.97   19.23  573.19   18.47  621.59   16.82  641.76   18.64  665.96   16.22
  678.05   13.41  736.09   12.93  741.96   10.34  755.74   10.35  762.35   12.96
  788.11   13.01  813.38   17.22     831   16.81  842.41   15.35  888.03   16.28
  895.32   15.49  925.36   17.05  959.65    16.1 1082.95   19.25  1306.9   19.33
 1333.14   20.53  1440.7    19.3 1555.74   19.71 1573.98   18.21  1586.3   19.04
#Mann= 3 ,0,0
       0     .15       0  736.09     .05       0  762.35     .15       0
Bank Sta=736.09,762.35
XS Rating Curve= 0 ,0
Exp/Cntr=0.3,0.1

--- GrierSwamp.g04 (geometry) ---

Geom Title=Duplicate Effective
Program Version=6.60

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