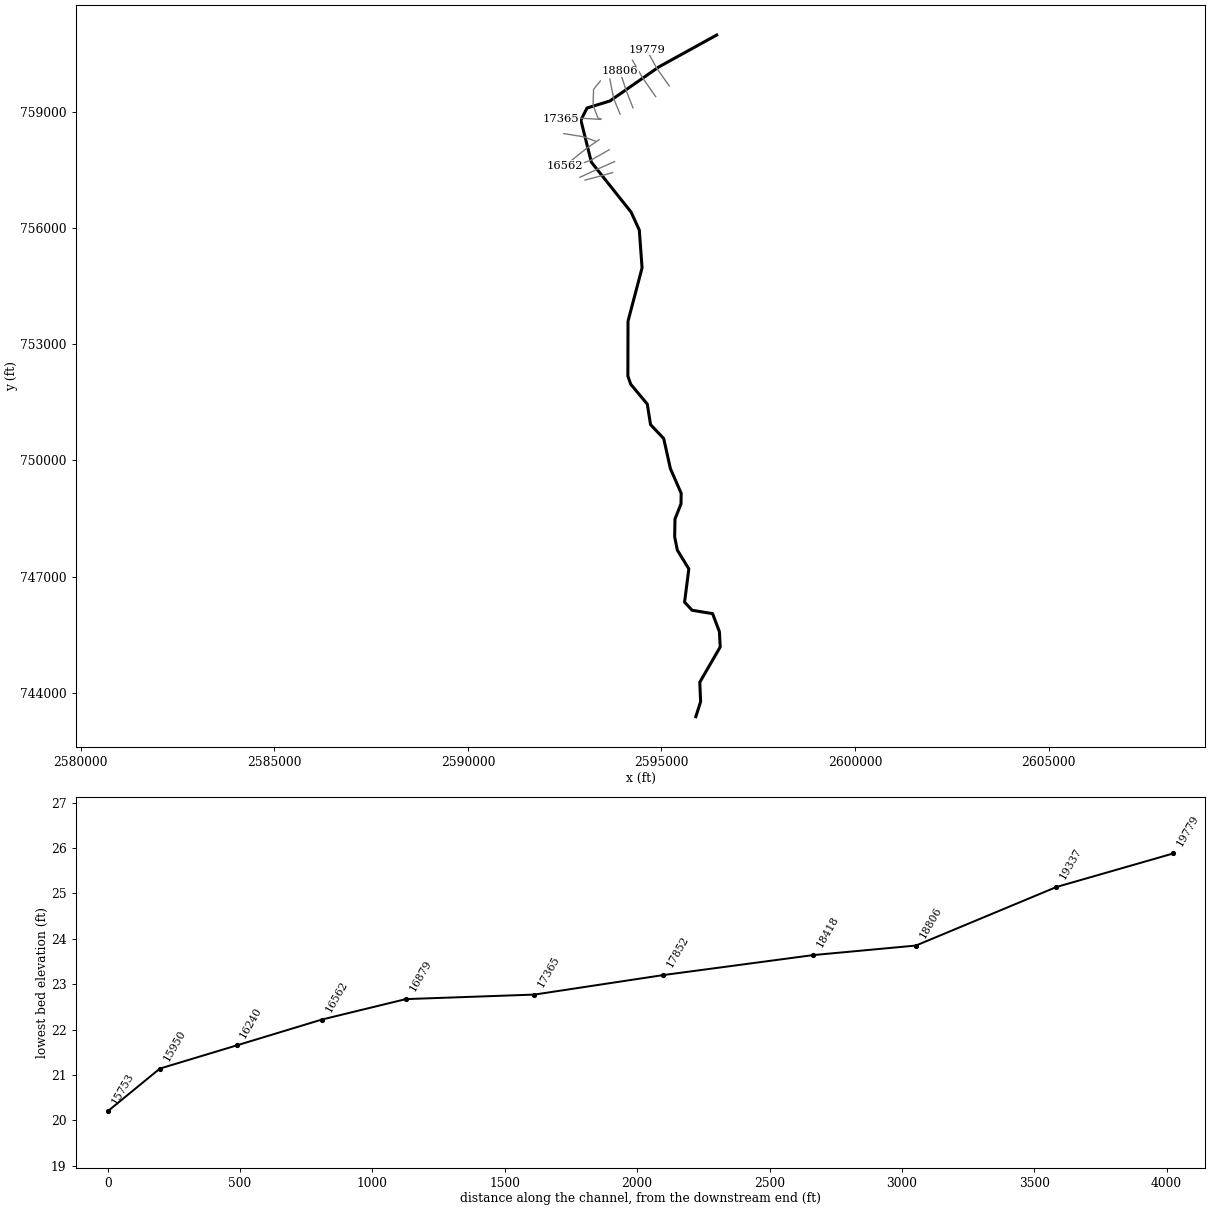
HEC-RAS study GrierSwamp.prj: S-26-65 over Grier Swamp

--- GrierSwamp.g04 (geometry) --- (continued)

River Reach=Grier Swamp     ,Reach-1
Reach XY= 30
      2596425.81       760987.35      2594938.26       760167.77
      2593669.72       759285.12      2593076.25       759101.12
      2592918.31       758788.54      2593189.06        757703.8
      2594215.99       756412.78      2594427.39       755950.33
       2594498.7       754973.74      2594135.71       753597.58
      2594132.06        752179.7      2594206.18       751967.85
      2594633.69       751455.44      2594717.51       750925.81
      2595057.35       750566.24      2595230.55       749788.99
        2595509.       749152.07      2595504.62       748879.32
      2595348.95       748487.96      2595340.18       748029.73
      2595410.34       747683.09      2595706.33       747198.99
       2595596.7       746342.15      2595789.64        746130.8
      2596320.23       746043.54      2596495.63       745578.72
      2596517.55       745183.85      2595989.16       744271.11
      2596011.09       743771.22      2595887.48       743382.35

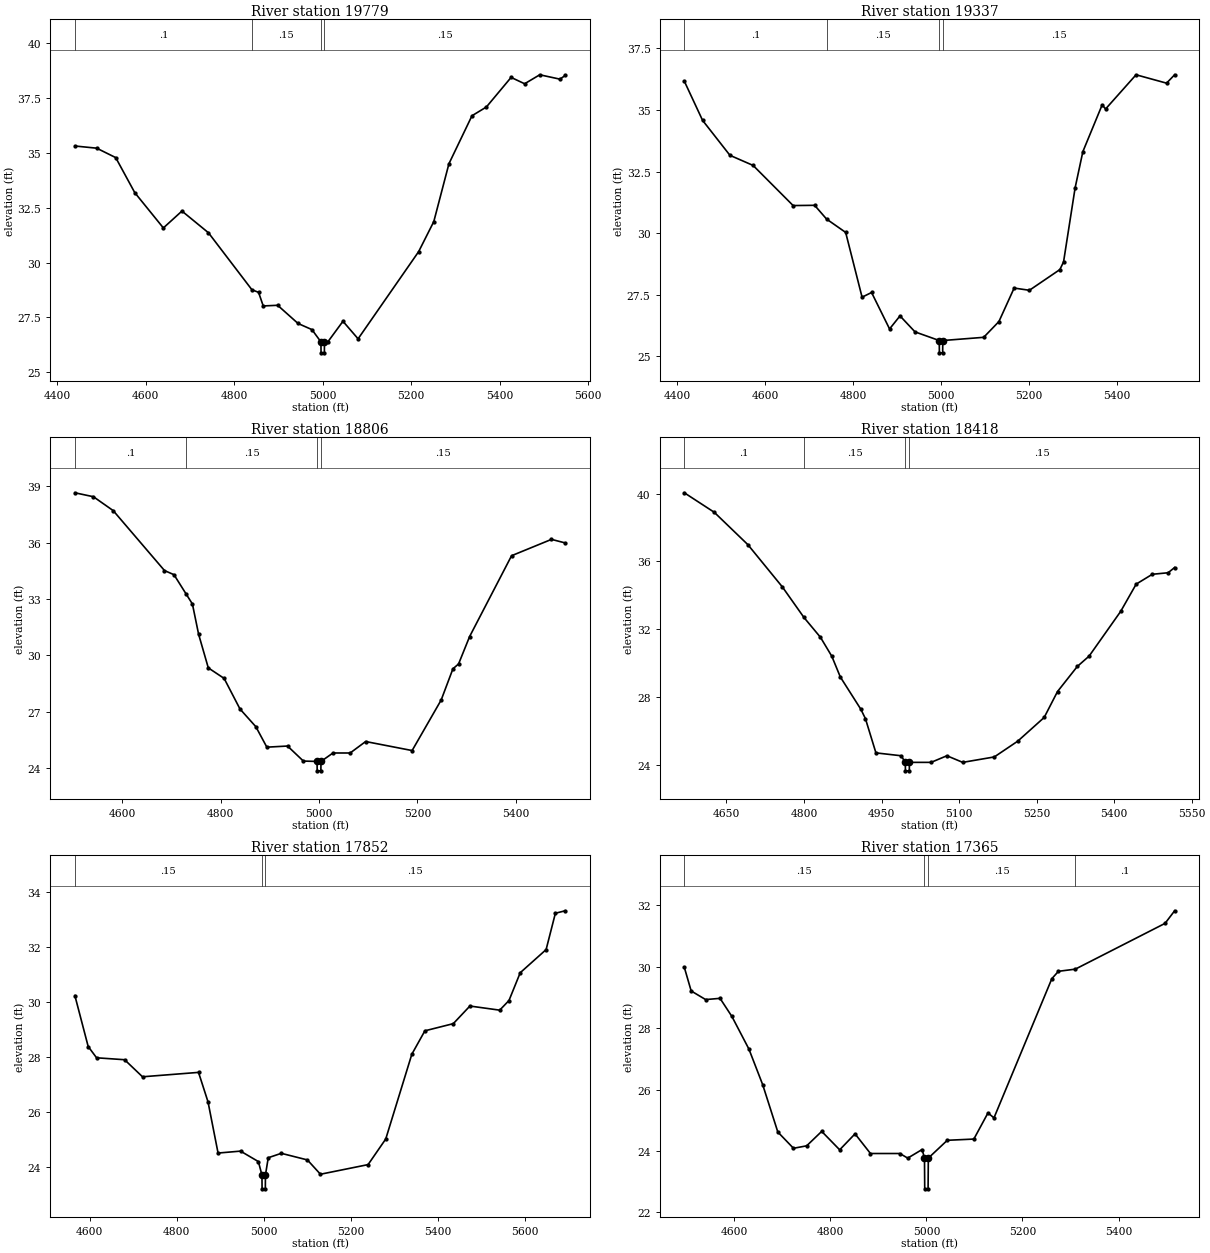
Type RM Length L Ch R = 1 ,19779   ,442,442,442
BEGIN DESCRIPTION:
Grier Swamp 33.0
END DESCRIPTION:
XS GIS Cut Line= 3
      2595200.97        759672.3      2594877.89       760129.82
      2594614.35       760610.41
#Sta/Elev= 30
  4439.9   35.32  4489.2   35.22  4532.2   34.79  4575.3   33.19  4639.9   31.58
  4681.9   32.35  4741.8   31.36    4840   28.76  4855.1   28.64  4865.6   28.02
  4898.2   28.05  4944.3   27.22  4975.7   26.94    4996   26.38  4996.3   25.88
  5003.8   25.88    5004   26.38  5011.6   26.38  5045.8   27.32    5080   26.52
  5216.9    30.5  5251.1   31.87  5285.3   34.51  5337.4    36.7    5370    37.1
  5425.8   38.45  5456.4   38.16  5490.6   38.57  5536.3   38.37  5548.1   38.54
#Mann= 4 ,-1,0
  4439.9      .1       0    4840     .15       0    4996     .05       0
    5004     .15       0
Bank Sta=4996,5004
XS Rating Curve= 0 ,0
Exp/Cntr=0.3,0.1

Type RM Length L Ch R = 1 ,19337   ,531,531,531
BEGIN DESCRIPTION:
Grier Swamp 32.0
END DESCRIPTION:
XS GIS Cut Line= 3
      2594849.18       759396.86      2594516.37       759876.02
      2594250.99       760335.95
#Sta/Elev= 30
  4416.6   36.17  4458.1   34.58  4520.3   33.16  4572.9   32.75  4663.9   31.12
  4712.8   31.13    4740   30.57  4783.3   30.03  4820.6    27.4  4842.2   27.59
  4883.1   26.11  4906.8   26.64    4941   25.99    4996   25.64  4996.3   25.14
  5003.8   25.14    5004   25.64    5097   25.77  5131.6   26.41  5166.2   27.77
  5200.9   27.68  5270.1   28.52  5278.5   28.83  5304.8   31.84  5322.4   33.31
  5366.3   35.21    5374   35.04  5443.3   36.43  5512.6   36.09    5531   36.43
#Mann= 4 ,-1,0
  4416.6      .1       0    4740     .15       0    4996     .05       0
    5004     .15       0
Bank Sta=4996,5004
XS Rating Curve= 0 ,0
Exp/Cntr=0.3,0.1

Type RM Length L Ch R = 1 ,18806   ,388,388,388
BEGIN DESCRIPTION:
Grier Swamp 31.0
END DESCRIPTION:
XS GIS Cut Line= 3
      2594263.81       759107.46      2594082.02       759569.59
      2593929.34       760046.55
#Sta/Elev= 30
  4503.4   38.65  4541.1   38.44  4581.4    37.7  4685.7   34.51    4705   34.29
    4730   33.25  4742.5   32.73  4755.1   31.12  4774.8   29.33    4807   28.77
  4839.3   27.14  4871.5    26.2  4893.9   25.11    4936   25.17  4968.2   24.37
    4996   24.35  4996.3   23.85  5003.8   23.85    5004   24.35  5028.4    24.8
  5063.4    24.8  5094.9   25.41  5189.4   24.93  5248.5   27.62  5272.4   29.28
  5283.9   29.54  5306.4      31  5391.7    35.3  5472.9   36.17  5500.8   35.98
#Mann= 4 ,-1,0
  4503.4      .1       0    4730     .15       0    4996     .05       0
    5004     .15       0
Bank Sta=4996,5004
XS Rating Curve= 0 ,0
Exp/Cntr=0.3,0.1

Type RM Length L Ch R = 1 ,18418   ,566,566,566
BEGIN DESCRIPTION:
Grier Swamp 30.0
END DESCRIPTION:
XS GIS Cut Line= 3
      2593931.17       758946.53      2593765.41       759344.92
      2593666.32       759852.44
#Sta/Elev= 30
  4568.5   40.05  4626.4    38.9  4691.4   36.99  4758.3   34.49    4800   32.69
  4831.9   31.52  4853.9    30.4  4870.3   29.18  4909.9   27.28  4918.9   26.72
  4939.2    24.7    4988   24.53    4996   24.14  4996.3   23.64  5003.8   23.64
    5004   24.14  5045.9   24.14  5076.5   24.53  5107.1   24.14  5168.2   24.46
  5213.5   25.39  5264.7   26.79  5290.5   28.32  5328.8    29.8  5351.6   30.41
  5412.7   33.05  5442.7   34.66  5473.9   35.24  5504.4   35.33  5517.1   35.64
#Mann= 4 ,-1,0
  4568.5      .1       0    4800     .15       0    4996     .05       0
    5004     .15       0
Bank Sta=4996,5004
XS Rating Curve= 0 ,0
Exp/Cntr=0.3,0.1

Type RM Length L Ch R = 1 ,17852   ,487,487,487
BEGIN DESCRIPTION:
Grier Swamp 29.0
END DESCRIPTION:
XS GIS Cut Line= 5
       2593439.4       758817.71      2593362.48       758839.64
       2593233.7       759169.51      2593245.52       759582.65
      2593421.27       759800.48
#Sta/Elev= 30
  4565.9   30.22  4596.5   28.37  4615.8   27.96  4680.2   27.89  4721.4   27.27
  4850.2   27.43    4872   26.36  4895.1    24.5  4946.8   24.57  4987.8   24.19
    4996    23.7  4996.3    23.2  5003.8    23.2    5004    23.7  5010.5   24.33
  5040.5   24.49  5100.5   24.25  5130.5   23.73    5240   24.08  5280.6   25.01
  5340.6   28.09  5370.6   28.94  5435.9    29.2  5474.1   29.84  5542.6   29.69
  5563.9   30.04  5589.8   31.05  5649.3   31.89  5670.6   33.21  5693.2    33.3
#Mann= 3 ,-1,0
  4565.9     .15       0    4996     .05       0    5004     .15       0
Bank Sta=4996,5004
XS Rating Curve= 0 ,0
Exp/Cntr=0.3,0.1

Type RM Length L Ch R = 1 ,17365   ,486,486,486
BEGIN DESCRIPTION:
Grier Swamp 28.0
END DESCRIPTION:
XS GIS Cut Line= 3
      2593424.28       758808.43      2592921.15        758839.8
      2592404.38       758828.38
#Sta/Elev= 30
  4495.9   29.98  4510.2   29.21  4540.3   28.93  4570.3   28.97    4595   28.38
  4630.4   27.32  4659.1   26.16  4690.6   24.62  4723.2   24.09  4750.7   24.17
    4782   24.64  4819.4   24.04  4851.4   24.56  4883.5   23.92  4944.7   23.92
  4961.1   23.77  4991.1   24.05    4996   23.77  4996.5   22.77  5003.5   22.77
    5004   23.77  5043.5   24.35  5098.8   24.39  5128.2   25.24  5140.7   25.08
  5261.2   29.61  5274.9   29.85    5310   29.92  5496.9   31.41  5516.9   31.82
#Mann= 4 ,-1,0
  4495.9     .15       0    4996     .05       0    5004     .15       0
    5310      .1       0
Bank Sta=4996,5004
XS Rating Curve= 0 ,0
Exp/Cntr=0.3,0.1

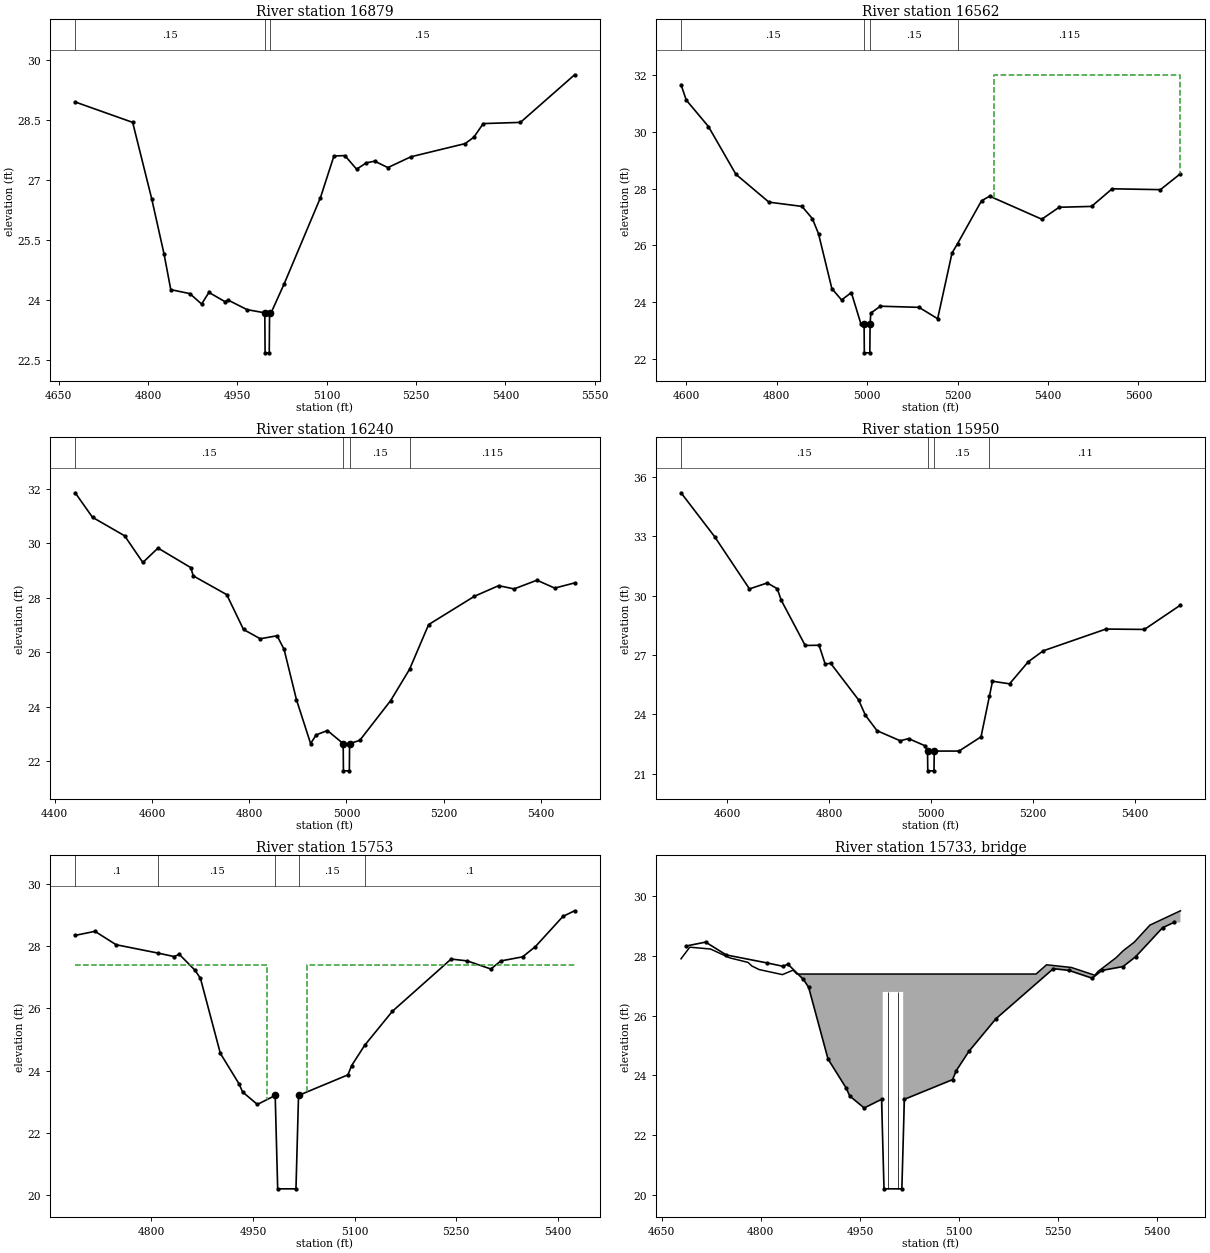
Type RM Length L Ch R = 1 ,16879   ,317,317,317
BEGIN DESCRIPTION:
Grier Swamp 27.0
END DESCRIPTION:
XS GIS Cut Line= 3
      2593290.35        758247.2      2592988.35       758360.06
      2592478.42       758440.92
#Sta/Elev= 30
  4677.6   28.94  4774.1   28.43  4806.1   26.52  4826.8   25.14  4838.1   24.25
  4870.1   24.15  4889.9   23.89  4902.2   24.18  4929.1   23.95  4934.2   23.99
  4966.2   23.75    4996   23.67  4996.5   22.67  5003.5   22.67    5004   23.67
  5007.2   23.69  5028.7    24.4  5089.5   26.55  5112.1   27.59  5130.5    27.6
  5150.2   27.26  5166.6   27.42  5180.6   27.46  5202.7    27.3  5241.3   27.57
  5332.5    27.9  5347.1   28.06  5362.8    28.4  5425.3   28.43  5516.3   29.62
#Mann= 3 ,-1,0
  4677.6     .15       0    4996     .05       0    5004     .15       0
Bank Sta=4996,5004
XS Rating Curve= 0 ,0
Exp/Cntr=0.3,0.1

Type RM Length L Ch R = 1 ,16562   ,322,322,322
BEGIN DESCRIPTION:
Grier Swamp 26.0
END DESCRIPTION:
XS GIS Cut Line= 3
      2593389.56       758284.64      2593051.88       758049.64
      2592510.38       757617.34
#Sta/Elev= 30
  4588.6   31.65  4600.2   31.11  4649.2   30.18  4709.9    28.5    4783   27.52
  4856.1   27.37    4879   26.94  4892.6   26.41  4922.1   24.48  4943.6   24.08
  4965.2   24.34  4986.7   23.22  4993.4   23.22  4993.9   22.22  5006.1   22.22
  5006.6   23.22  5008.2   23.62  5029.5   23.86  5114.9   23.82    5156   23.42
  5187.8   25.73    5200   26.06  5253.1   27.57  5271.1   27.73  5386.3   26.92
  5424.7   27.34  5496.3   27.37  5541.9   27.99  5648.6   27.96  5692.9   28.52
#Mann= 4 ,-1,0
  4588.6     .15       0  4993.4     .05       0  5006.6     .15       0
    5200    .115       0
#XS Ineff= 2 , 0
       0                    5280       0      32
Permanent Ineff=
       F       F
Bank Sta=4993.4,5006.6
XS Rating Curve= 0 ,0
Exp/Cntr=0.3,0.1

Type RM Length L Ch R = 1 ,16240   ,290,290,290
BEGIN DESCRIPTION:
Grier Swamp 25.0
END DESCRIPTION:
XS GIS Cut Line= 3
      2593650.96       758025.24      2593166.05       757749.17
      2592722.28       757595.55
#Sta/Elev= 30
    4442   31.86  4477.6   30.96  4543.7   30.28  4581.2    29.3  4612.3   29.83
    4680   29.11  4684.8   28.81  4753.8   28.12  4788.3   26.84  4822.8    26.5
  4857.4   26.61  4871.8   26.11  4897.3   24.26  4926.4   22.65  4937.8   22.97
  4960.9   23.13  4993.4   22.65  4993.9   21.65  5006.1   21.65  5006.6   22.65
  5027.6   22.77  5091.1   24.23    5130   25.38  5169.2   27.02  5263.5   28.06
  5313.3   28.45    5345   28.33  5392.2   28.65  5428.6   28.36  5469.6   28.55
#Mann= 4 ,-1,0
    4442     .15       0  4993.4     .05       0  5006.6     .15       0
    5130    .115       0
Bank Sta=4993.4,5006.6
XS Rating Curve= 0 ,0
Exp/Cntr=0.3,0.1

Type RM Length L Ch R = 1 ,15950   ,197,197,197
BEGIN DESCRIPTION:
Grier Swamp 24.0
END DESCRIPTION:
XS GIS Cut Line= 3
      2593788.89       757718.16      2593340.05        757520.6
      2592895.84       757314.25
#Sta/Elev= 30
  4509.6    35.2  4575.6   32.98  4643.9   30.34  4678.8   30.64  4698.5   30.35
  4706.2   29.77  4753.3   27.48  4780.5   27.49  4792.5   26.54  4803.2   26.58
    4858   24.73  4871.5   23.95  4894.3   23.17  4939.8   22.66  4956.3   22.77
  4989.1    22.4  4993.4   22.14  4993.9   21.14  5006.1   21.14  5006.6   22.14
  5055.2   22.14  5098.4   22.86    5115   24.93  5120.9   25.67  5154.4   25.54
  5191.3   26.66  5220.6   27.21  5343.7   28.31  5419.1   28.29  5489.8   29.52
#Mann= 4 ,-1,0
  4509.6     .15       0  4993.4     .05       0  5006.6     .15       0
    5115     .11       0
Bank Sta=4993.4,5006.6
XS Rating Curve= 0 ,0
Exp/Cntr=0.5,0.3

Type RM Length L Ch R = 1 ,15753   ,46,46,46
BEGIN DESCRIPTION:
Grier Swamp (Wise Rd) US
END DESCRIPTION:
XS GIS Cut Line= 3
      2593738.14       757434.51      2593437.13       757350.19
      2593026.54       757240.07
#Sta/Elev= 28
  4687.4   28.34  4716.6   28.47  4747.8   28.04    4810   27.77  4833.5   27.66
  4841.2   27.73  4864.4   27.22  4872.4   26.96  4901.8   24.55  4929.2   23.58
  4934.7   23.31  4956.5   22.91  4982.8    23.2  4986.5    20.2  5013.5    20.2
  5017.3    23.2  5090.2   23.86  5095.8   24.16    5115   24.81  5155.8    25.9
  5242.7   27.58  5266.5   27.52  5301.4   27.26  5316.2   27.52  5348.2   27.65
  5367.2   27.98  5407.9   28.95  5425.1   29.13
#Mann= 5 ,-1,0
  4687.4      .1       0    4810     .15       0  4982.8     .05       0
  5017.3     .15       0    5115      .1       0
#XS Ineff= 2 , 0
       0    4970    27.4    5030       0    27.4
Permanent Ineff=
       F       F
Bank Sta=4982.8,5017.3
XS Rating Curve= 0 ,0
Exp/Cntr=0.5,0.3

Type RM Length L Ch R = 3 ,15733   ,,,
BEGIN DESCRIPTION:
Grier Swamp (Wise Rd) TOR
Structure ID: LDS_GRS_02
Approximate Survey Structure
END DESCRIPTION:
Bridge Culvert--1,0,-1,-1, 0
Deck Dist Width WeirC Skew NumUp NumDn MinLoCord MaxHiCord MaxSubmerge Is_Ogee
5,30,3,0, 27, 27, , , 0.95, 0, 1,1,,
  4679.4  4692.6    4723  4723.8  4752.3  4755.2  4780.8  4786.5  4797.5  4832.8
    4849  4854.7  4984.5  4984.5  5015.5  5015.5  5216.5  5232.4  5269.9  5305.4
  5310.5  5317.1  5337.8  5348.3  5365.2  5388.8    5435
   27.91    28.3   28.24   28.24   27.95   27.93   27.79   27.67   27.55   27.38
   27.53    27.4    27.4    27.4    27.4    27.4    27.4   27.71   27.62   27.36
   27.49    27.6   27.95   28.18   28.47   29.04   29.52
     .17     .17     .17     .17     .17     .17     .17     .17     .17     .17
     .17     .17     .17    26.8    26.8     .17     .17     .17     .17     .17
     .17     .17     .17     .17     .17     .17     .17
  4679.4  4692.6    4723  4723.8  4752.3  4755.2  4780.8  4786.5  4797.5  4832.8
    4849  4854.7  4984.5  4984.5  5015.5  5015.5  5216.5  5232.4  5269.9  5305.4
  5310.5  5317.1  5337.8  5348.3  5365.2  5388.8    5435
   27.91    28.3   28.24   28.24   27.95   27.93   27.79   27.67   27.55   27.38
   27.53    27.4    27.4    27.4    27.4    27.4    27.4   27.71   27.62   27.36
   27.49    27.6   27.95   28.18   28.47   29.04   29.52
     .17     .17     .17     .17     .17     .17     .17     .17     .17     .17
     .17     .17     .17    26.8    26.8     .17     .17     .17     .17     .17
     .17     .17     .17     .17     .17     .17     .17
Pier Skew, UpSta & Num, DnSta & Num=  ,4992.3, 2 ,4992.3, 2 , 0 , 0 , 0 ,0,0
       1       1
    19.2    26.8
       1       1
   18.95    26.8
Pier Skew, UpSta & Num, DnSta & Num=  ,5007.8, 2 ,5007.8, 2 , 0 , 0 , 0 ,0,0
       1       1
    19.2    26.8
       1       1
   18.95    26.8
BR Coef= 1 , 1 , 0 ,1.25, 0 ,,,0.8,0,2,0,
WSPro=,,,, 1 ,,,, 0 ,,,, 0 ,,,,-1 ,-1 ,-1 , 0 , 0 , 0 , 0 , 0
BC Design=,, 0 ,, 0 ,,,,,,
BC HTab HWMax=29.13
BC Use User HTab Curves=0
BC User HTab FreeFlow(D)= 0