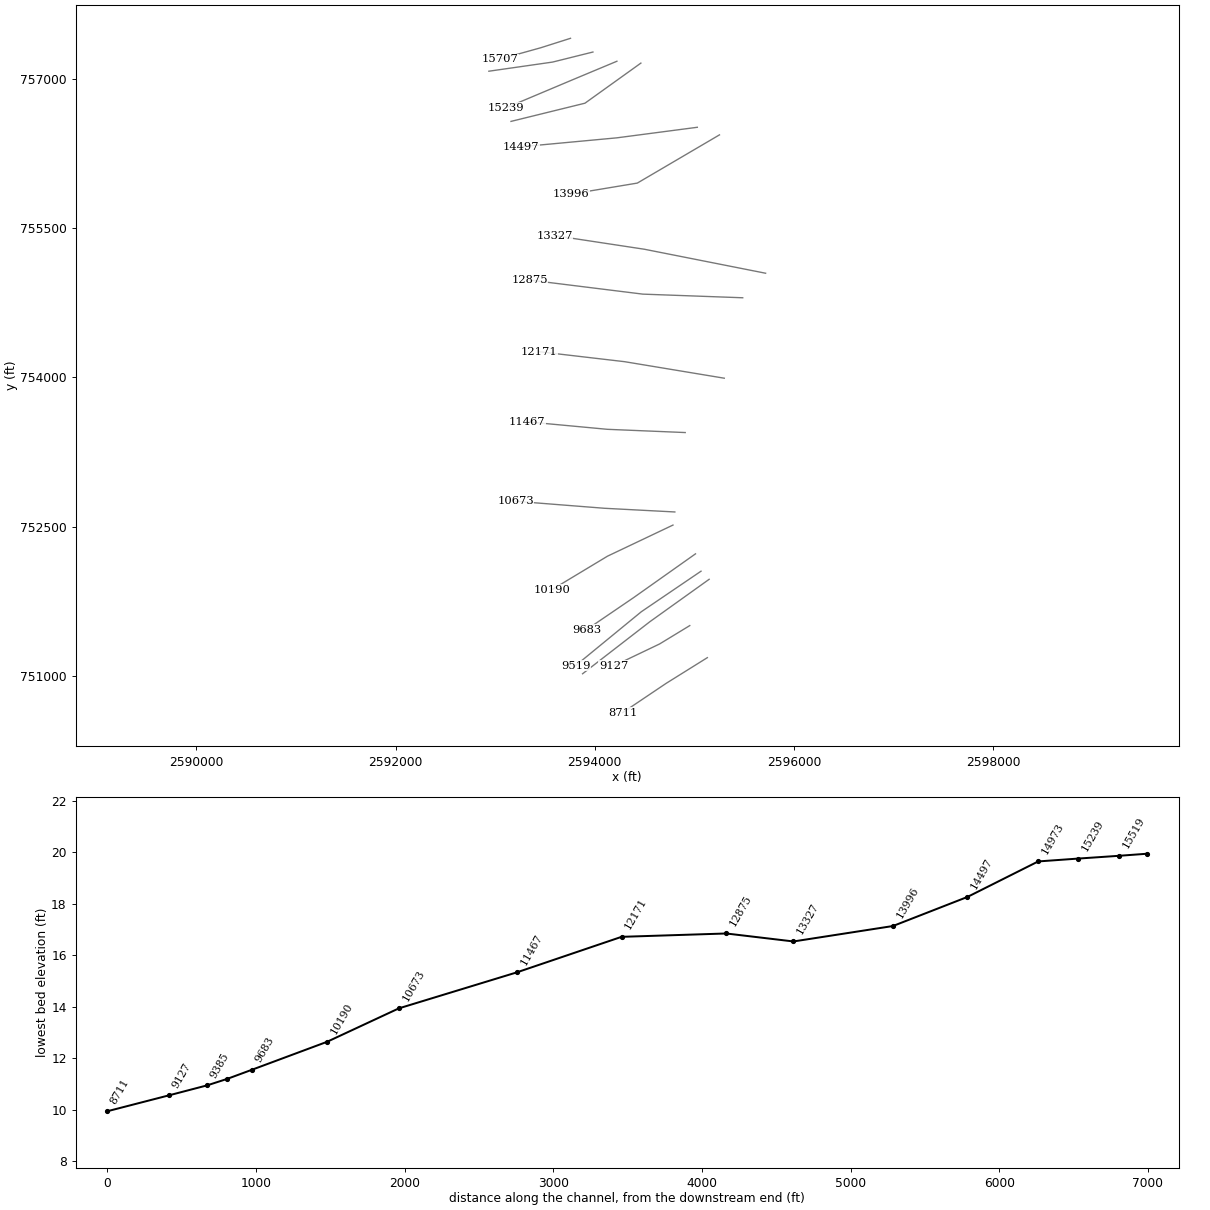
HEC-RAS study GrierSwamp.prj: S-26-65 over Grier Swamp

--- GrierSwamp.g04 (geometry) --- (continued)

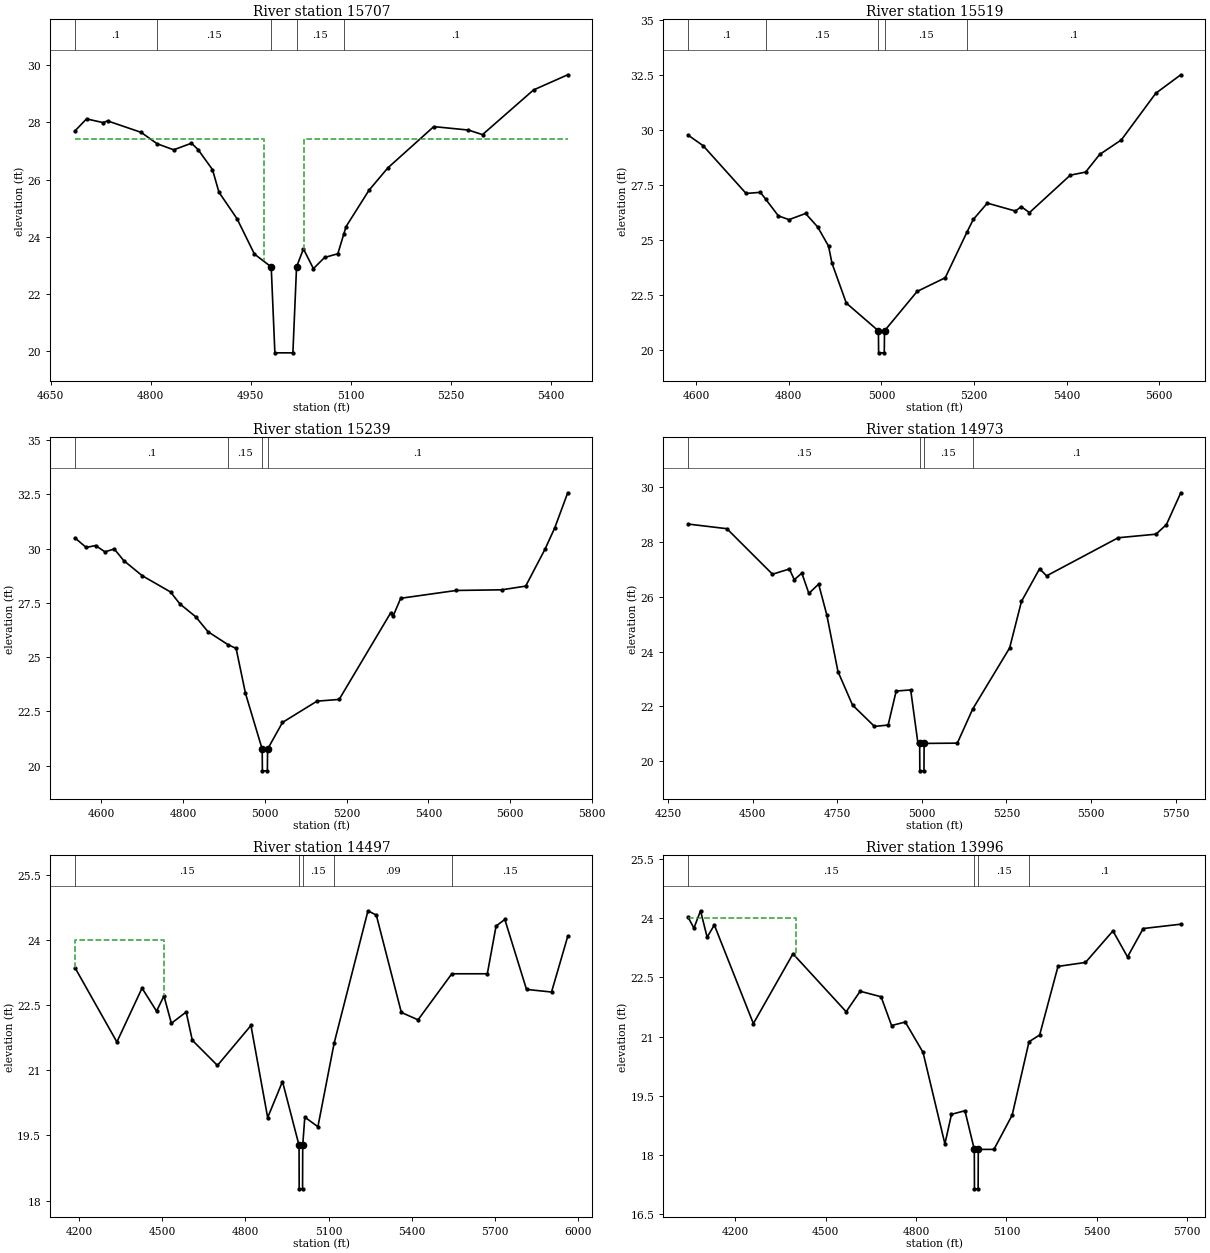
Type RM Length L Ch R = 1 ,15707   ,188,188,188
BEGIN DESCRIPTION:
Grier Swamp (Wise Rd) DS
END DESCRIPTION:
XS GIS Cut Line= 3
      2593756.49        757403.9      2593457.91       757309.02
      2593047.82       757194.77
#Sta/Elev= 30
  4686.7    27.7    4704   28.12  4728.9   27.99  4735.5   28.05  4785.8   27.65
    4810   27.25  4834.7   27.04  4861.4   27.27  4871.2   27.05  4892.9   26.35
  4902.6   25.56  4929.8   24.63  4955.8    23.4    4981   22.95  4986.5   19.95
  5013.5   19.95    5019   22.95  5029.3   23.58  5044.3   22.89    5061   23.28
  5080.9   23.41    5090   24.11  5093.3   24.36  5127.7   25.63    5156   26.41
  5224.8   27.85  5276.7   27.73  5297.9   27.57  5374.4   29.13  5425.7   29.66
#Mann= 5 ,-1,0
  4686.7      .1       0    4810     .15       0    4981     .05       0
    5019     .15       0    5090      .1       0
#XS Ineff= 2 , 0
       0    4970    27.4    5030       0    27.4
Permanent Ineff=
       F       F
Bank Sta=4981,5019
XS Rating Curve= 0 ,0
Exp/Cntr=0.5,0.3

Type RM Length L Ch R = 1 ,15519   ,280,280,280
BEGIN DESCRIPTION:
Grier Swamp 23.0
END DESCRIPTION:
XS GIS Cut Line= 3
      2593981.55       757266.06      2593576.33       757165.13
      2592936.57       757073.37
#Sta/Elev= 30
  4582.4   29.76  4614.9   29.28  4707.7   27.11  4738.6   27.16    4750   26.85
  4777.5   26.09  4800.4   25.92  4836.2    26.2  4862.2   25.59  4885.7   24.72
  4893.2   23.94  4924.1   22.13  4993.4   20.87  4993.9   19.87  5006.1   19.87
  5006.6   20.87  5077.1   22.66  5137.7   23.28    5185   25.37  5198.3   25.93
  5228.6   26.67  5289.3   26.31  5301.7   26.51  5319.6   26.24  5407.7   27.94
  5440.8   28.08  5471.1   28.88  5517.9   29.54  5592.3   31.66  5646.3    32.5
#Mann= 5 ,-1,0
  4582.4      .1       0    4750     .15       0  4993.4     .05       0
  5006.6     .15       0    5185      .1       0
Bank Sta=4993.4,5006.6
XS Rating Curve= 0 ,0
Exp/Cntr=0.3,0.1

Type RM Length L Ch R = 1 ,15239   ,266,266,266
BEGIN DESCRIPTION:
Grier Swamp 22.0
END DESCRIPTION:
XS GIS Cut Line= 3
      2594222.44       757173.43      2593793.67       756994.25
      2593110.72        756706.5
#Sta/Elev= 30
  4535.3   30.49  4562.7   30.05  4585.6   30.14  4608.6   29.85  4631.5   29.98
  4654.4   29.45  4699.8   28.75  4769.1      28    4792   27.45  4830.6   26.86
  4860.8   26.17    4910   25.57  4929.6    25.4  4952.5   23.33  4993.4   20.76
  4993.9   19.76  5006.1   19.76  5006.6   20.76  5043.1   21.99  5127.5   22.97
  5181.8   23.05  5307.9   27.04  5313.6   26.88  5332.4   27.71  5468.3   28.07
  5579.7    28.1  5638.2   28.27  5685.5   29.97  5709.3   30.95  5741.1   32.57
#Mann= 4 ,-1,0
  4535.3      .1       0    4910     .15       0  4993.4     .05       0
  5006.6      .1       0
Bank Sta=4993.4,5006.6
XS Rating Curve= 0 ,0
Exp/Cntr=0.3,0.1

Type RM Length L Ch R = 1 ,14973   ,476,476,476
BEGIN DESCRIPTION:
Grier Swamp 21.0
END DESCRIPTION:
XS GIS Cut Line= 3
      2594463.24       757154.86      2593901.69       756752.19
      2593158.85       756569.39
#Sta/Elev= 30
    4309   28.65  4423.7   28.48  4558.5   26.82  4608.3   27.01    4623   26.62
  4645.2   26.86    4666   26.12  4694.9   26.46  4719.1   25.33    4752   23.27
    4795   22.05  4859.8   21.27  4900.3   21.32    4924   22.56  4966.9    22.6
  4988.4   20.65  4993.4   20.65  4993.9   19.65  5006.1   19.65  5006.6   20.65
  5104.7   20.66    5150    21.9  5259.2   24.13  5294.3   25.83  5347.8   27.02
  5368.4   26.76    5580   28.15  5691.7   28.28  5722.6   28.63    5765   29.79
#Mann= 4 ,-1,0
    4309     .15       0  4993.4     .05       0  5006.6     .15       0
    5150      .1       0
Bank Sta=4993.4,5006.6
XS Rating Curve= 0 ,0
Exp/Cntr=0.3,0.1

Type RM Length L Ch R = 1 ,14497   ,501,501,501
BEGIN DESCRIPTION:
Grier Swamp 20.0
END DESCRIPTION:
XS GIS Cut Line= 3
      2595030.03       756510.33      2594221.26       756404.22
      2593261.82       756314.78
#Sta/Elev= 30
  4184.3   23.36  4335.6   21.65  4426.4   22.89  4478.8   22.36  4505.6   22.71
  4532.3   22.08  4585.8   22.34  4607.9   21.69  4698.7   21.11  4819.7   22.03
  4880.1   19.91  4933.6   20.74  4993.4   19.27  4993.9   18.27  5006.1   18.27
  5006.6   19.27  5014.2   19.92  5061.5    19.7    5120   21.62  5242.3   24.67
  5272.4   24.57  5362.8   22.33  5423.1   22.16    5545   23.22  5673.3   23.22
  5704.9   24.32  5736.5   24.47  5814.8   22.86  5905.2    22.8  5963.6   24.08
#Mann= 5 ,-1,0
  4184.3     .15       0  4993.4     .05       0  5006.6     .15       0
    5120     .09       0    5545     .15       0
#XS Ineff= 2 , 0
       0    4505      24               0
Permanent Ineff=
       F       F
Bank Sta=4993.4,5006.6
XS Rating Curve= 0 ,0
Exp/Cntr=0.3,0.1

Type RM Length L Ch R = 1 ,13996   ,669,669,669
BEGIN DESCRIPTION:
Grier Swamp 19.0
END DESCRIPTION:
XS GIS Cut Line= 3
      2595252.57       756434.14       2594427.5       755949.86
      2593757.99       755838.58
#Sta/Elev= 30
  4043.3   24.03  4062.8   23.75  4084.7   24.19  4106.7   23.52  4130.5   23.83
  4260.1   21.33  4391.6    23.1  4568.1   21.63  4614.5   22.15    4684   22.01
  4718.8   21.28  4764.3   21.37  4823.2    20.6  4895.8   18.28  4917.7   19.03
  4962.3   19.12  4993.4   18.14  4993.9   17.14  5006.1   17.14  5006.6   18.14
  5058.6   18.14  5119.1   19.01    5175   20.87  5210.3   21.04  5271.2   22.78
  5362.4   22.88  5453.6   23.68  5501.9   23.02    5554   23.74  5678.7   23.85
#Mann= 4 ,-1,0
  4043.3     .15       0  4993.4     .05       0  5006.6     .15       0
    5175      .1       0
#XS Ineff= 2 , 0
       0    4400      24               0
Permanent Ineff=
       F       F
Bank Sta=4993.4,5006.6
XS Rating Curve= 0 ,0
Exp/Cntr=0.3,0.1

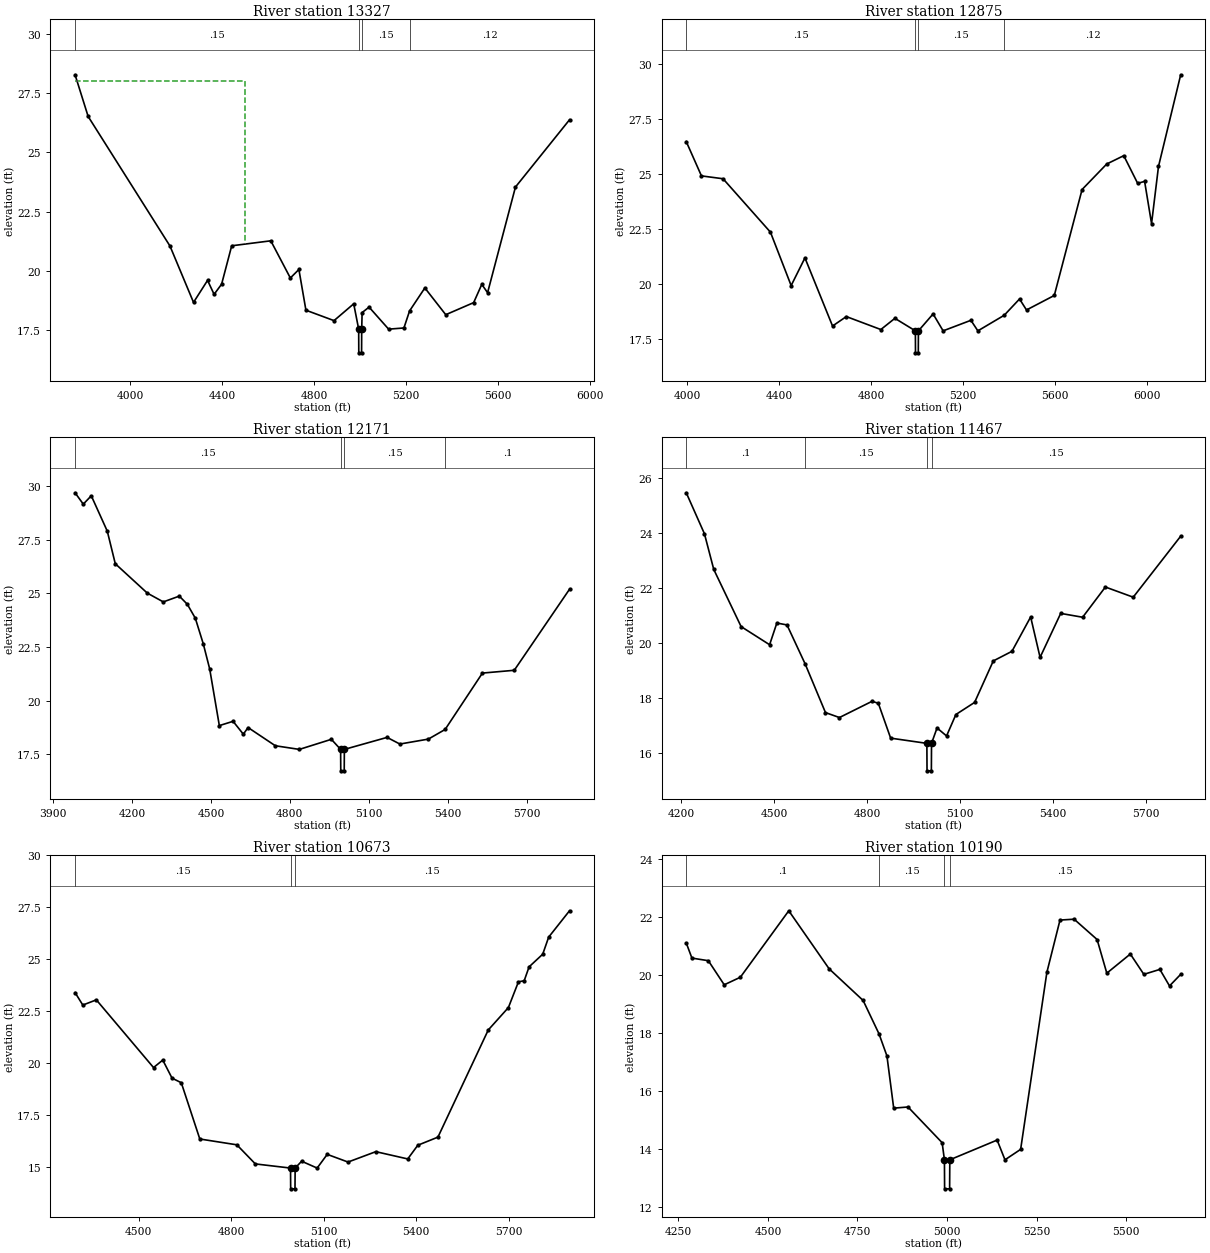
Type RM Length L Ch R = 1 ,13327   ,452,452,452
BEGIN DESCRIPTION:
Grier Swamp 18.0
END DESCRIPTION:
XS GIS Cut Line= 3
      2595715.77       755044.54      2594498.28       755285.48
      2593597.42       755422.31
#Sta/Elev= 30
  3758.9   28.28  3815.8   26.52    4172   21.05  4274.5   18.67  4335.6    19.6
  4364.1   19.01  4396.8   19.44  4440.7   21.06  4610.9   21.27    4696    19.7
  4733.2   20.06  4763.8   18.34  4886.1    17.9  4971.8   18.61  4993.4   17.54
  4993.9   16.54  5006.1   16.54  5006.6   17.54  5008.4   18.24  5038.7   18.47
  5123.8   17.54  5190.4   17.59    5215   18.31  5281.5   19.28  5372.5   18.15
  5493.9   18.66  5529.3   19.43  5554.6   19.08  5675.9   23.54  5911.2   26.38
#Mann= 4 ,-1,0
  3758.9     .15       0  4993.4     .05       0  5006.6     .15       0
    5215     .12       0
#XS Ineff= 2 , 0
       0    4500      28               0
Permanent Ineff=
       F       F
Bank Sta=4993.4,5006.6
XS Rating Curve= 0 ,0
Exp/Cntr=0.3,0.1

Type RM Length L Ch R = 1 ,12875   ,704,704,704
BEGIN DESCRIPTION:
Grier Swamp 17.0
END DESCRIPTION:
XS GIS Cut Line= 3
      2595486.08       754798.11      2594483.24        754834.6
      2593344.18       754975.98
#Sta/Elev= 30
  3996.5   26.46  4062.6    24.9  4156.6   24.77  4362.8   22.34  4452.9   19.91
  4512.9   21.17    4633   18.07    4693    18.5  4843.1   17.91  4904.3   18.42
  4993.4   17.85  4993.9   16.85  5006.1   16.85  5006.6   17.85  5070.5   18.62
  5114.1   17.85    5235   18.33  5265.3   17.85    5380   18.56  5446.6    19.3
  5476.9    18.8  5597.8   19.46  5718.7   24.28  5825.9   25.44  5900.1   25.82
  5960.6   24.56  5990.8   24.65    6021   22.73  6051.2   25.33  6147.8    29.5
#Mann= 4 ,-1,0
  3996.5     .15       0  4993.4     .05       0  5006.6     .15       0
    5380     .12       0
Bank Sta=4993.4,5006.6
XS Rating Curve= 0 ,0
Exp/Cntr=0.3,0.1

Type RM Length L Ch R = 1 ,12171   ,704,704,704
BEGIN DESCRIPTION:
Grier Swamp 16.0
END DESCRIPTION:
XS GIS Cut Line= 3
      2595300.78       753990.28      2594298.25       754156.43
      2593441.37       754256.44
#Sta/Elev= 30
  3983.8   29.69    4015   29.16  4045.4   29.55  4106.2    27.9  4136.6   26.38
  4258.3   25.01  4319.1    24.6  4379.9   24.87  4410.3   24.49  4440.7   23.84
  4471.1   22.64  4495.4   21.47    4532   18.83  4584.2   19.03  4623.2   18.43
  4641.2   18.74  4744.8   17.89    4836   17.72  4957.7   18.19  4992.9   17.72
  4993.4   16.72  5006.6   16.72  5007.1   17.72  5169.4   18.28    5218   17.97
  5326.2    18.2    5390   18.65  5531.8   21.28  5652.7   21.41  5862.7   25.19
#Mann= 4 ,-1,0
  3983.8     .15       0  4992.9     .05       0  5007.1     .15       0
    5390      .1       0
Bank Sta=4992.9,5007.1
XS Rating Curve= 0 ,0
Exp/Cntr=0.3,0.1

Type RM Length L Ch R = 1 ,11467   ,794,794,794
BEGIN DESCRIPTION:
Grier Swamp 15.0
END DESCRIPTION:
XS GIS Cut Line= 3
      2594908.59        753444.5      2594125.76       753477.07
      2593318.18       753552.49
#Sta/Elev= 30
  4216.5   25.46  4275.1   23.97  4305.2   22.67  4393.4   20.59  4485.3   19.93
  4508.7   20.72  4541.4   20.65    4600   19.23  4665.5   17.46  4710.5   17.28
  4815.6   17.87  4835.9    17.8  4875.7   16.53  4992.5   16.34    4993   15.34
    5007   15.34  5007.5   16.34  5025.3    16.9    5056   16.61  5086.1   17.39
  5146.4   17.83  5206.7   19.34  5266.9   19.69  5327.2   20.94  5357.6   19.47
  5424.1   21.07  5494.8   20.93  5568.2   22.03    5658   21.66  5811.1   23.88
#Mann= 4 ,-1,0
  4216.5      .1       0    4600     .15       0  4992.5     .05       0
  5007.5     .15       0
Bank Sta=4992.5,5007.5
XS Rating Curve= 0 ,0
Exp/Cntr=0.3,0.1

Type RM Length L Ch R = 1 ,10673   ,483,483,483
BEGIN DESCRIPTION:
Grier Swamp 14.0
END DESCRIPTION:
XS GIS Cut Line= 3
      2594804.25       752646.99      2594098.51       752683.93
      2593203.39       752754.46
#Sta/Elev= 30
  4293.3   23.39  4318.4   22.79  4362.3   23.04  4547.9   19.78  4577.9   20.14
    4608   19.27    4638   19.05  4698.1   16.34  4818.3   16.06  4878.3   15.14
  4992.5   14.94    4993   13.94    5007   13.94  5007.5   14.94  5028.6   15.27
  5078.9   14.94  5111.6    15.6  5179.1   15.23  5269.3   15.73  5372.9   15.38
  5405.6   16.04  5470.9   16.43  5634.2   21.59  5699.6   22.67  5732.2   23.91
  5750.8   23.96  5766.7   24.63    5811   25.24  5830.2   26.06  5897.9   27.33
#Mann= 3 ,-1,0
  4293.3     .15       0  4992.5     .05       0  5007.5     .15       0
Bank Sta=4992.5,5007.5
XS Rating Curve= 0 ,0
Exp/Cntr=0.3,0.1

Type RM Length L Ch R = 1 ,10190   ,507,507,507
BEGIN DESCRIPTION:
Grier Swamp 13.0
END DESCRIPTION:
XS GIS Cut Line= 3
      2594785.66       752515.44      2594128.37       752203.16
      2593570.21       751866.95
#Sta/Elev= 30
  4272.3   21.11  4288.1   20.59  4333.9    20.5  4378.2   19.67  4423.2   19.93
  4558.3   22.22  4670.9   20.22  4765.7   19.13    4810   17.98  4832.1   17.22
    4851   15.42  4890.9   15.46  4986.1   14.23  4992.5   13.64    4993   12.64
    5007   12.64  5007.5   13.64  5139.5   14.32  5161.4   13.64  5205.1      14
  5278.3    20.1  5314.9    21.9  5354.3   21.93  5418.4   21.23  5445.5   20.07
  5511.1   20.73  5548.8   20.03  5593.5    20.2  5620.4   19.63  5651.6   20.03
#Mann= 4 ,-1,0
  4272.3      .1       0    4810     .15       0  4992.5     .05       0
  5007.5     .15       0
Bank Sta=4992.5,5007.5
XS Rating Curve= 0 ,0
Exp/Cntr=0.3,0.1

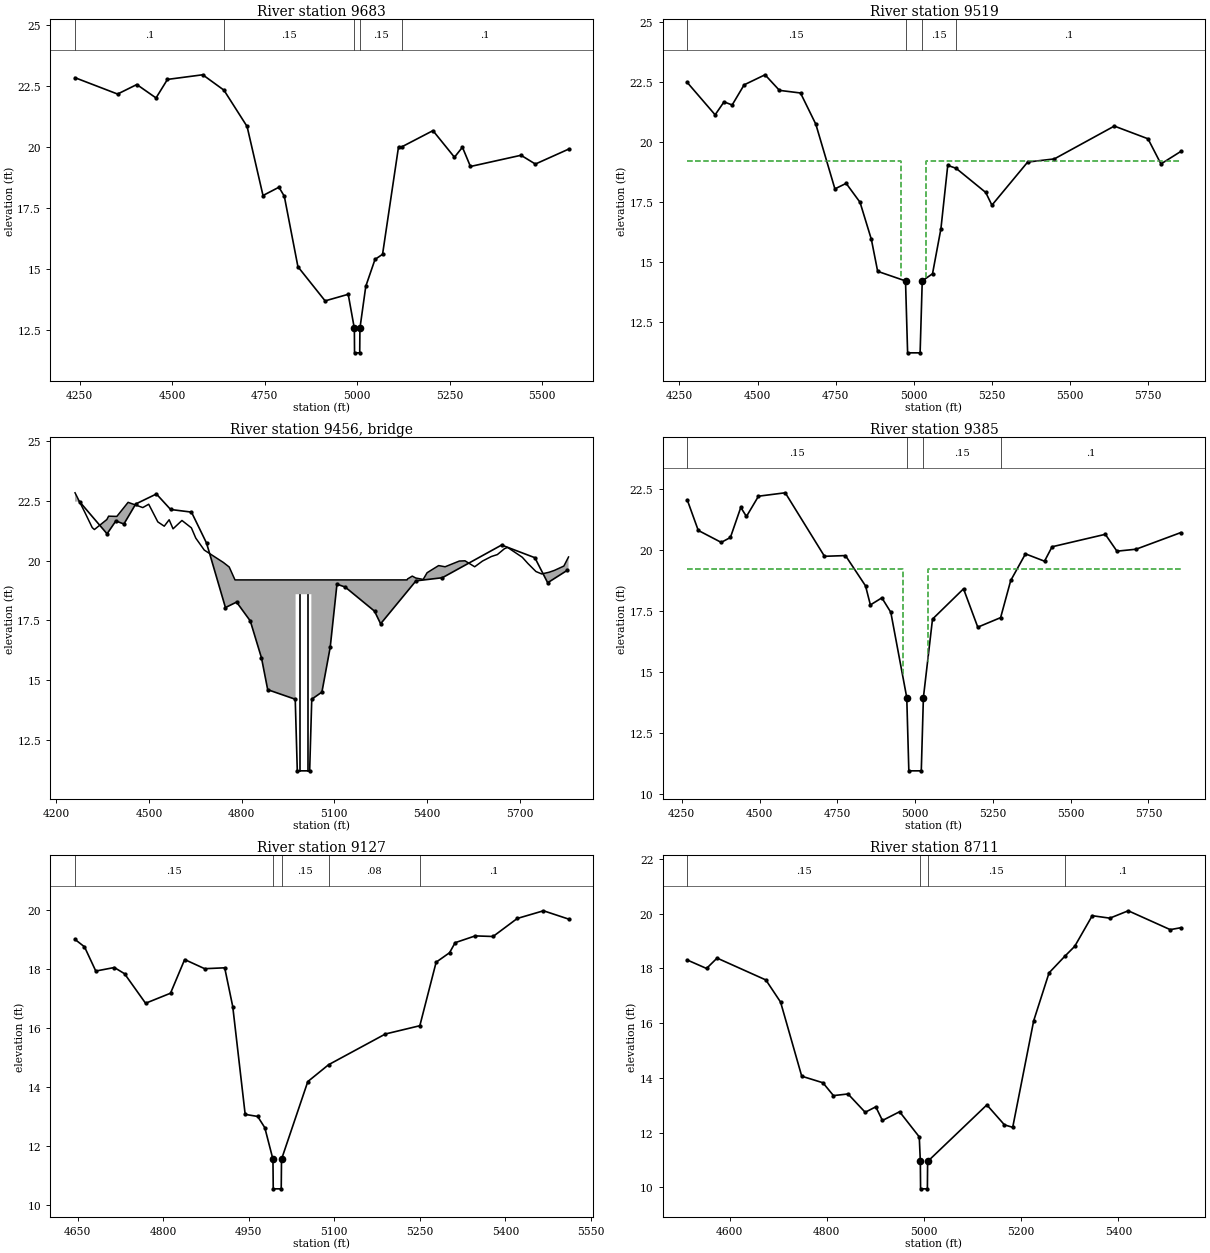
Type RM Length L Ch R = 1 ,9683    ,164,164,164
BEGIN DESCRIPTION:
Grier Swamp 12.0
END DESCRIPTION:
XS GIS Cut Line= 3
      2595011.74       752226.42      2594389.35       751786.09
      2593917.15       751464.52
#Sta/Elev= 30
  4237.6   22.83  4352.6   22.16  4404.6   22.55  4456.5      22  4487.4   22.76
  4582.7   22.95    4640   22.32  4702.6   20.83  4745.6      18  4788.7   18.34
  4803.2   17.97    4840   15.08  4913.5   13.68  4975.9   13.95  4992.5   12.55
    4993   11.55    5007   11.55  5007.5   12.55  5023.4   14.28  5048.3   15.38
  5068.7   15.59  5111.9      20    5120   19.99  5204.9   20.66    5263   19.57
  5284.6   19.98  5306.2   19.19  5442.9   19.65  5481.7   19.29  5571.3    19.9
#Mann= 5 ,-1,0
  4237.6      .1       0    4640     .15       0  4992.5     .05       0
  5007.5     .15       0    5120      .1       0
Bank Sta=4992.5,5007.5
XS Rating Curve= 0 ,0
Exp/Cntr=0.5,0.3

Type RM Length L Ch R = 1 ,9519    ,134,134,134
BEGIN DESCRIPTION:
Grier Swamp (HWY-65) US
END DESCRIPTION:
XS GIS Cut Line= 3
      2595067.33       752052.27      2594467.58       751644.94
      2593807.35       751103.57
#Sta/Elev= 30
    4275   22.48  4364.2   21.13  4392.7   21.67  4418.7   21.54    4457   22.38
  4523.9    22.8  4569.9   22.15  4637.4   22.04  4686.3   20.74  4747.4   18.04
  4783.4   18.27  4827.8   17.48  4864.1   15.93  4884.2    14.6  4973.3    14.2
    4980    11.2    5020    11.2  5026.8    14.2  5059.7    14.5  5086.6   16.38
  5108.4   19.02    5135    18.9    5230   17.89  5249.7   17.36  5364.2   19.16
  5449.4   19.29  5641.3   20.66    5749   20.13  5790.5   19.08  5853.8    19.6
#Mann= 4 ,-1,0
    4275     .15       0  4973.3     .05       0  5026.8     .15       0
    5135      .1       0
#XS Ineff= 2 , 0
       0    4960    19.2    5040       0    19.2
Permanent Ineff=
       F       F
Bank Sta=4973.3,5026.8
XS Rating Curve= 0 ,0
Exp/Cntr=0.5,0.3

Type RM Length L Ch R = 3 ,9456    ,,,
BEGIN DESCRIPTION:
Grier Swamp (HWY-65) TOR
Structure ID: LDS_GRS_01
Approximate Survey Structure
END DESCRIPTION:
Bridge Culvert--1,0,-1,-1, 0
Deck Dist Width WeirC Skew NumUp NumDn MinLoCord MaxHiCord MaxSubmerge Is_Ogee
48,30,3,0, 49, 49, , , 0.95, 0, 1,1,,
  4260.5  4292.3  4316.2  4323.2  4363.5  4369.2  4395.8  4432.3  4479.8    4499
  4528.5  4549.3  4565.2  4577.8  4606.6  4637.2  4651.4  4678.8  4740.8  4759.6
  4778.3  4974.5  4974.5  5025.5  5025.5  5335.3  5336.9  5352.2  5363.3  5387.5
  5400.1  5437.5  5458.4  5504.5  5522.9  5554.2  5579.6  5608.2  5627.5  5650.9
  5660.8  5708.2  5726.3  5752.6    5771  5794.9  5812.6  5842.9    5858
   22.85   22.03   21.39   21.31   21.73   21.87   21.86   22.45   22.23   22.37
   21.63   21.45   21.72   21.34   21.69   21.38   20.95   20.45   19.93   19.74
    19.2    19.2    19.2    19.2    19.2    19.2   19.24   19.36   19.28   19.22
    19.5    19.8   19.75   19.99      20   19.75   19.99   20.18   20.26   20.51
   20.56   20.15   19.89   19.55   19.45   19.52    19.6   19.78   20.16
   -8.89   -8.89   -8.89   -8.89   -8.89   -8.89   -8.89   -8.89   -8.89   -8.89
   -8.89   -8.89   -8.89   -8.89   -8.89   -8.89   -8.89   -8.89   -8.89   -8.89
   -8.89   -8.89    18.6    18.6   -8.89   -8.89   -8.89   -8.89   -8.89   -8.89
   -8.89   -8.89   -8.89   -8.89   -8.89   -8.89   -8.89   -8.89   -8.89   -8.89
   -8.89   -8.89   -8.89   -8.89   -8.89   -8.89   -8.89   -8.89   -8.89
  4260.5  4292.3  4316.2  4323.2  4363.5  4369.2  4395.8  4432.3  4479.8    4499
  4528.5  4549.3  4565.2  4577.8  4606.6  4637.2  4651.4  4678.8  4740.8  4759.6
  4778.3  4974.5  4974.5  5025.5  5025.5  5335.3  5336.9  5352.2  5363.3  5387.5
  5400.1  5437.5  5458.4  5504.5  5522.9  5554.2  5579.6  5608.2  5627.5  5650.9
  5660.8  5708.2  5726.3  5752.6    5771  5794.9  5812.6  5842.9    5858
   22.85   22.03   21.39   21.31   21.73   21.87   21.86   22.45   22.23   22.37
   21.63   21.45   21.72   21.34   21.69   21.38   20.95   20.45   19.93   19.74
    19.2    19.2    19.2    19.2    19.2    19.2   19.24   19.36   19.28   19.22
    19.5    19.8   19.75   19.99      20   19.75   19.99   20.18   20.26   20.51
   20.56   20.15   19.89   19.55   19.45   19.52    19.6   19.78   20.16
   -8.89   -8.89   -8.89   -8.89   -8.89   -8.89   -8.89   -8.89   -8.89   -8.89
   -8.89   -8.89   -8.89   -8.89   -8.89   -8.89   -8.89   -8.89   -8.89   -8.89
   -8.89   -8.89    18.6    18.6   -8.89   -8.89   -8.89   -8.89   -8.89   -8.89
   -8.89   -8.89   -8.89   -8.89   -8.89   -8.89   -8.89   -8.89   -8.89   -8.89
   -8.89   -8.89   -8.89   -8.89   -8.89   -8.89   -8.89   -8.89   -8.89
Pier Skew, UpSta & Num, DnSta & Num=  ,4987.3, 2 ,4987.3, 2 , 0 , 0 , 0 ,0,0
       1       1
    10.2    18.6
       1       1
    9.95    18.6
Pier Skew, UpSta & Num, DnSta & Num=  ,5012.8, 2 ,5012.8, 2 , 0 , 0 , 0 ,0,0
       1       1
    10.2    18.6
       1       1
    9.95    18.6
BR Coef= 1 , 1 , 0 ,1.25, 0 ,,,0.8,0,2,0,
WSPro=,,,, 1 ,,,, 0 ,,,, 0 ,,,,-1 ,-1 ,-1 , 0 , 0 , 0 , 0 , 0
BC Design=,, 0 ,, 0 ,,,,,,
BC HTab HWMax=22.8
BC Use User HTab Curves=0
BC User HTab FreeFlow(D)= 0

Type RM Length L Ch R = 1 ,9385    ,258,258,258
BEGIN DESCRIPTION:
Grier Swamp (HWY-65) DS
END DESCRIPTION:
XS GIS Cut Line= 3
      2595148.81       751970.71      2594553.22       751544.64
      2593877.77       751022.06
#Sta/Elev= 30
  4267.7   22.04  4303.1   20.79  4376.9    20.3  4406.4    20.5  4439.8   21.73
    4458   21.36  4496.7   22.19  4582.7   22.33  4708.9   19.73  4776.3   19.76
  4840.8   18.52  4856.4   17.74  4893.3   18.03    4922   17.44  4973.3   13.95
    4980   10.95    5020   10.95  5026.8   13.95  5056.1   17.16  5155.8    18.4
  5201.6   16.83    5275   17.22  5307.5   18.74  5354.9   19.83  5416.1   19.53
  5440.4   20.12  5611.5   20.63  5648.9   19.94  5710.3   20.02    5854    20.7
#Mann= 4 ,-1,0
  4267.7     .15       0  4973.3     .05       0  5026.8     .15       0
    5275      .1       0
#XS Ineff= 2 , 0
       0    4960    19.2    5040       0    19.2
Permanent Ineff=
       F       F
Bank Sta=4973.3,5026.8
XS Rating Curve= 0 ,0
Exp/Cntr=0.5,0.3

Type RM Length L Ch R = 1 ,9127    ,416,416,416
BEGIN DESCRIPTION:
Grier Swamp 11.0
END DESCRIPTION:
XS GIS Cut Line= 3
      2594954.16       751505.83      2594651.38       751321.46
      2594190.59       751101.25
#Sta/Elev= 30
  4645.5      19  4662.1   18.75  4681.9   17.93  4714.4   18.05  4732.3   17.84
  4769.2   16.84  4812.9   17.18  4837.7   18.32  4872.8   18.01  4907.9   18.04
    4922   16.73  4943.8   13.08  4965.7   13.01  4978.2   12.63  4992.5   11.56
    4993   10.56    5007   10.56  5007.5   11.56  5053.6   14.19    5090   14.76
  5189.6    15.8    5250   16.08  5278.6   18.23  5302.1   18.55  5311.9   18.89
  5347.1   19.12  5378.4    19.1  5420.8   19.71  5466.8   19.97  5510.7   19.69
#Mann= 5 ,-1,0
  4645.5     .15       0  4992.5     .05       0  5007.5     .15       0
    5090     .08       0    5250      .1       0
Bank Sta=4992.5,5007.5
XS Rating Curve= 0 ,0
Exp/Cntr=0.3,0.1

Type RM Length L Ch R = 1 ,8711    ,495,495,495
BEGIN DESCRIPTION:
Grier Swamp 10.0
END DESCRIPTION:
XS GIS Cut Line= 3
      2595130.75       751183.88      2594717.42       750925.96
       2594278.9       750631.17
#Sta/Elev= 30
  4512.8   18.31  4552.5      18  4574.2   18.38  4674.6   17.58  4704.9   16.77
  4748.4   14.06    4792   13.82  4813.7   13.35  4843.7   13.41    4879   12.74
  4900.8   12.94  4914.5   12.44  4949.8   12.76  4990.3   11.84  4992.5   10.94
    4993    9.94    5007    9.94  5007.5   10.94  5129.4   13.01  5165.6   12.28
  5182.6   12.19  5225.8   16.09  5257.4   17.84    5290   18.45  5310.2   18.81
  5346.3   19.93  5382.5   19.84  5420.4   20.11  5506.8   19.42  5528.4   19.49
#Mann= 4 ,-1,0
  4512.8     .15       0  4992.5     .05       0  5007.5     .15       0
    5290      .1       0
Bank Sta=4992.5,5007.5
XS Rating Curve= 0 ,0
Exp/Cntr=0.3,0.1