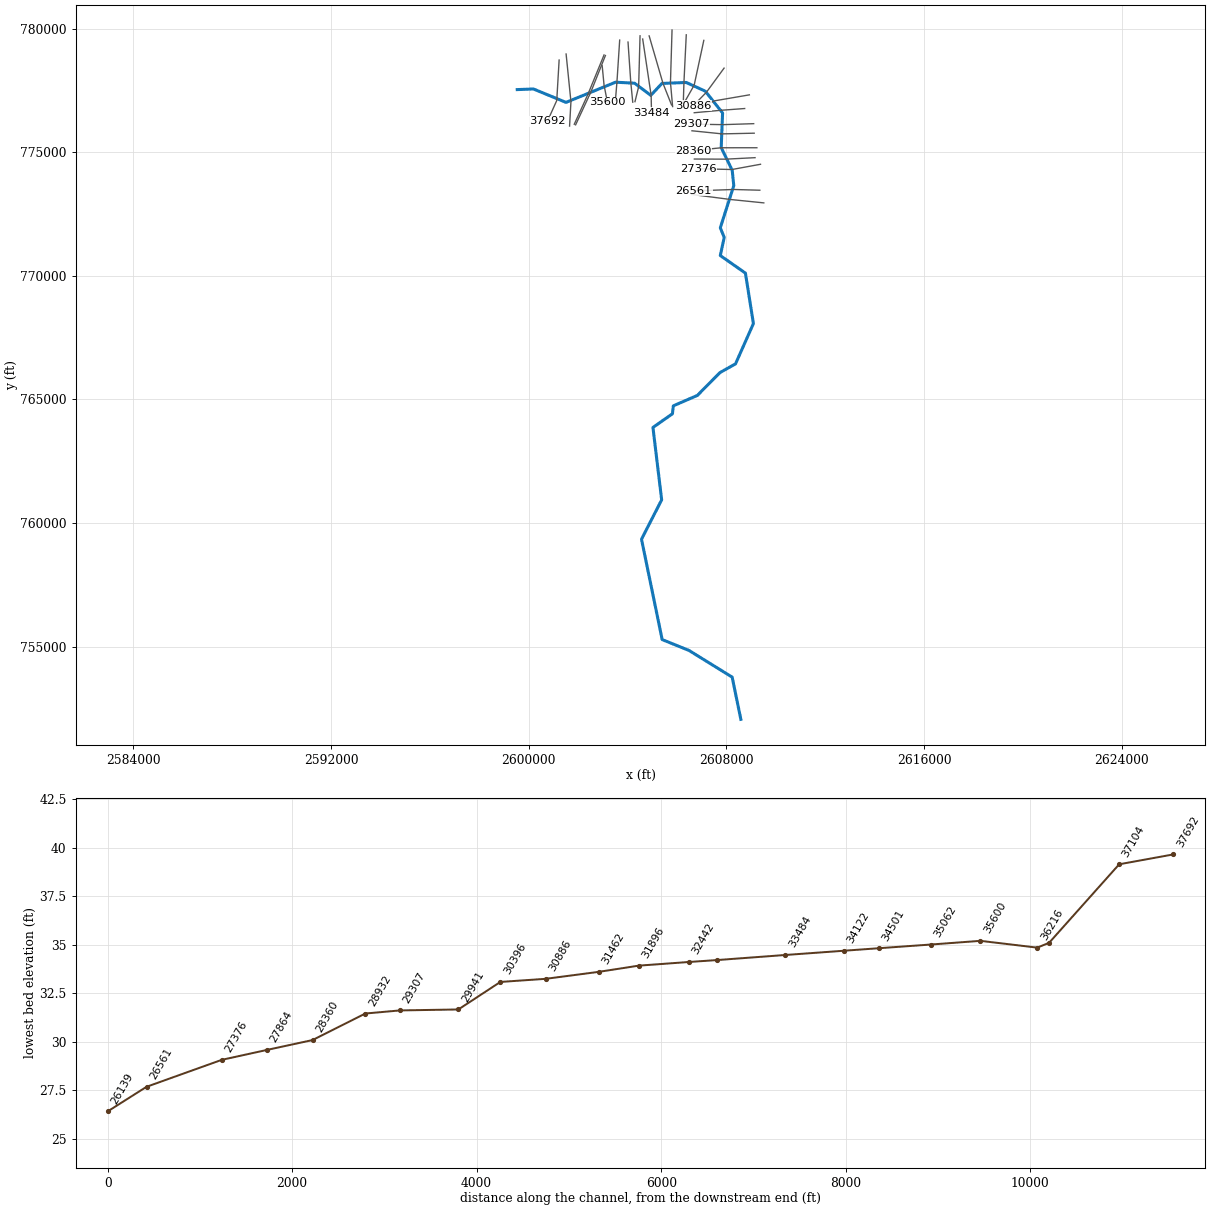
--- MapleSwamp.prj (project) ---

Proj Title=S-26-65 over Maple Swamp
Current Plan=p06
Default Exp/Contr=0.3,0.1
English Units
Geom File=g01
Geom File=g04
Geom File=g06
Geom File=g02
Flow File=f01
Flow File=f03
Flow File=f04
Plan File=p04
Plan File=p05
Plan File=p06
Plan File=p07
Plan File=p01
Y Axis Title=Elevation
X Axis Title(PF)=Main Channel Distance
X Axis Title(XS)=Station
BEGIN DESCRIPTION:
END DESCRIPTION:
DSS File=dss
DSS Export Rating Curves= 0
DSS Export Rating Curve Sorted= 0
DSS Export Volume Flow Curves= 0
DXF OffsetX= 0
DXF OffsetY= 0
DXF ScaleX= 1
DXF ScaleY= 10

--- MapleSwamp.p06 (plan) ---

Plan Title=Exisiting Conditions
Program Version=6.60
Short Identifier=EXT
Geom File=g04
Flow File=f01
Subcritical Flow
K Sum by GR= 0
Std Step Tol= 0.01
Critical Tol= 0.01
Num of Std Step Trials= 20
Max Error Tol= 0.3
Flow Tol Ratio= 0.001
Split Flow NTrial= 30
Split Flow Tol= 0.02
Split Flow Ratio= 0.02
Log Output Level= 0
Friction Slope Method= 1
Unsteady Friction Slope Method= 2
Unsteady Bridges Friction Slope Method= 1
Calc Critical at every XS
Parabolic Critical Depth
Global Vel Dist= 0 , 0 , 0
Global Log Level= 0
CheckData=True
Encroach Param=-1 ,0,0, 0
Flow Ratio Tolerance=0.1
Flow Ratio Min Ratio=0.5
Flow Ratio Max Ratio=4
Flow Ratio Max Iterations= 10
BEGIN DESCRIPTION:
Existing conditions: Cross-sections from 15357 to 591 overbanks were cut using LiDAR and surveyed data because the FEMA effective model cross-sections are not representative of the floodway.
END DESCRIPTION:
Computation Interval=1MIN
Output Interval=1HOUR
Instantaneous Interval=1HOUR
Mapping Interval=1HOUR
Computation Time Step Use Courant=        0
Computation Time Step Use Time Series=    0
Computation Time Step Count To Double=0
Computation Time Step Max Doubling=0
Computation Time Step Max Halving=0
Computation Time Step Residence Courant=0
Run HTab= 0
Run UNet= 0
Run Sediment= 0
Run PostProcess= 0
Run WQNet= 0
Run RASMapper= 0
UNET Theta= 1
UNET Theta Warmup= 1
UNET ZTol= 0.02
UNET ZSATol= 0.02
UNET MxIter= 20
UNET Max Iter WO Improvement= 0
UNET MaxInSteps= 0
UNET DtIC= 0
UNET DtMin= 0
UNET MaxCRTS= 20
UNET WFStab= 2
UNET SFStab= 1
UNET WFX= 1
UNET SFX= 1
UNET Gravity=32.17405
UNET 1D Methodology=Finite Difference
UNET DSS MLevel= 4
UNET Pardiso=0
UNET DZMax Abort= 100
UNET Use Existing IB Tables=-1
UNET Froude Reduction=False
UNET Froude Limit= 0.8
UNET Froude Power= 4
UNET D1 Cores= 0
UNET WindReference=Eulerian
UNET WindDragFormulation=Hsu (1988)
UNET D2 Coriolis=0
UNET D2 Cores= 0
UNET D2 Theta= 1
UNET D2 Theta Warmup= 1
UNET D2 Z Tol= 0.01
UNET D2 Volume Tol= 0.01
UNET D2 Max Iterations= 20
UNET D2 Advanced Convergence=0
UNET D2 WS Max Tol=0.15
UNET D2 WS RMS Tol=0.002
UNET D2 WS Stall Tol=1
UNET D2 Equation= 0
UNET D2 RampUpFraction=0.1
UNET D2 TimeSlices= 1
UNET D2 Turbulence Formulation=None
UNET D2 Eddy Viscosity=0.3
UNET D2 Transverse Eddy Viscosity=0.1
UNET D2 Smagorinsky Mixing=0.05
UNET D2 BCVolumeCheck=0
UNET D2 Cores=0
UNET D2 SolverType=PARDISO (Direct)
UNET D2 Minimum Iterations= 3
UNET D2 Maximum Iterations= 30
UNET D2 Restart Number= 10
UNET D2 Relaxation Coeff=1.3
UNET D2 SOR Precondition Iterations= 10
UNET D2 ILUT Maximum Fill= 8
UNET D2 ILUT Tolerance=1E-08
UNET D2 Convergence Tolerance=0.00001
PS Theta= 1
PS WS Tol= 0.01
PS Volume Tol= 0.01
PS Max Iterations= 20
PS Equation= 0
PS Advance Time Step=-1
PS Target Courant=0.9
PS Time Slices= 1
PS Iterate With 2D=0
PS Project Initial WSE from DS=-1
PS Ramp Up Initial WSE from US=-1
PS Cores=0
UNET D1D2 MaxIter= 0
UNET D1D2 ZTol=0.01
UNET D1D2 QTol=0.1
UNET D1D2 MinQTol=1
DSS File=dss
Write IC File= 0
Write IC File at Fixed DateTime=0
Write IC File at Sim End=0
Echo Input=False
Echo Parameters=False
Echo Output=False
Write Detailed= 0
HDF Write Warmup=0
HDF Write Time Slices=0
HDF Flush=0
HDF Compression= 1
HDF Chunk Size= 1
HDF Spatial Parts= 1
HDF Use Max Rows=0
HDF Fixed Rows= 1
Calibration Method= 0
Calibration Iterations= 20
Calibration Max Change=0.05
Calibration Tolerance=0.2
Calibration Maximum=1.5
Calibration Minimum=0.5
Calibration Optimization Method= 1
WQ AD Non Conservative
WQ ULTIMATE=-1
WQ Max Comp Step=1HOUR
WQ Output Interval=15MIN
WQ Output Selected Increments= 0
WQ Create Restart=0
WQ Fixed Restart=0
WQ System Summary=0
WQ Write To DSS=0
Sorting and Armoring Iterations= 10
XS Update Threshold= 0.02
Bed Roughness Predictor= 0
Processes Affected by Predictor=Sediment Only
Hydraulics Update Threshold= 0.02
Energy Slope Method= 1
Volume Change Method= 1
Sediment Retention Method= 0
Sediment TS Multiplier= 1
Warm Up Method= 0
XS Weighting Method= 0
Number of US Weighted Cross Sections= 1
Number of DS Weighted Cross Sections= 1
Upstream XS Weight=0
Main XS Weight=1
Downstream XS Weight=0
Number of DS XS's Weighted with US Boundary= 1
Upstream Boundary Weight= 1
Weight of XSs Associated with US Boundary= 0
Number of US XS's Weighted with DS Boundary= 1
Downstream Boundary Weight= 0.5
Weight of XSs Associated with DS Boundary= 0.5
Percentile Method= 0
Sediment Output Level= 3
Mass or Volume Output= 0
Output Increment Type= 1
Profile and TS Output Increment= 1
Transport Output Increment 1
XS Output Flag= 0
XS Output Increment= 10
Read HDF5 Sediment Hotstart= 0
Sediment Hotstart Type= 0
Write Gradation File= 0
Read Gradation Hotstart= 0
Write HDF5 File= 1
Write Binary Output= 1
Write DSS Sediment File= 0
DSS Sediment Output Type= 1
SV Curve= 0
Specific Gage Flag= 0
Subcell Erosion Methods= 0
Subcell Deposition Methods= 0
Advection Scheme= 1
Matrix Solver= 0
Implicit Weighting Factor= 1
Maximum Outer Loop Convergence Iterations= 5
Convergence Maximum Absolute= 0.001
Convergence RMSE= 0.0001
Grain Fractions Max Abs Error= 0.001
Max Subgrid Regions= 1
Max Subgrid Length Scale= 3.402823E+38
Initial Layer Thickness= 3
Min Layer Thickness= 0.1
Max Layer Thickness= 6
Number of Layers= 5

--- MapleSwamp.p01 (plan) ---

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Plan Title=Proposed Conditions
Short Identifier=PROP
Geom File=g02
Flow File=f01

--- MapleSwamp.p04 (plan) ---

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Plan Title=Sensitivity_Analysis
Short Identifier=SA
Geom File=g04
Flow File=f03

--- MapleSwamp.p05 (plan) ---

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Plan Title=Natural_Conditions
Short Identifier=NAT
Geom File=g06
Flow File=f01

--- MapleSwamp.p07 (plan) ---

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Plan Title=Duplicate_Effective
Short Identifier=DE
Geom File=g01
Flow File=f04
FEMA Duplicate Effective Model
HEC-RAS version 6.6

--- MapleSwamp.f01 (steady flow) ---

Flow Title=USGS_Regression Equations
Program Version=6.60
Number of Profiles= 6
Profile Names=2yr,10yr,25yr,50yr,100yr,500yr
River Rch & RM=Maple Swamp,Reach-1         ,37692
     280     766    1090    1390    1690    2450
River Rch & RM=Maple Swamp,Reach-1         ,15908
     515    1380    1940    2470    2990    4310
River Rch & RM=Maple Swamp,Reach-1         ,6151
     533    1430    2010    2550    3080    4440
Boundary for River Rch & Prof#=Maple Swamp,Reach-1         , 1
Up Type= 0
Dn Type= 3
Dn Slope=0.0007
Boundary for River Rch & Prof#=Maple Swamp,Reach-1         , 2
Up Type= 0
Dn Type= 3
Dn Slope=0.0007
Boundary for River Rch & Prof#=Maple Swamp,Reach-1         , 3
Up Type= 0
Dn Type= 3
Dn Slope=0.0007
Boundary for River Rch & Prof#=Maple Swamp,Reach-1         , 4
Up Type= 0
Dn Type= 3
Dn Slope=0.0007
Boundary for River Rch & Prof#=Maple Swamp,Reach-1         , 5
Up Type= 0
Dn Type= 3
Dn Slope=0.0007
Boundary for River Rch & Prof#=Maple Swamp,Reach-1         , 6
Up Type= 0
Dn Type= 3
Dn Slope=0.0007
DSS Import GetInterval= 0
DSS Import GetPeak= 0
DSS Import FillOption= 0

--- MapleSwamp.f03 (steady flow) ---

Flow Title=Sensitivity Analysis
Program Version=6.60
Number of Profiles= 3
Profile Names=-3ft,Normal Depth,+3ft
River Rch & RM=Maple Swamp,Reach-1         ,37692
    1690    1690    1690
River Rch & RM=Maple Swamp,Reach-1         ,15908
    2990    2990    2990
River Rch & RM=Maple Swamp,Reach-1         ,6151
    3080    3080    3080
Boundary for River Rch & Prof#=Maple Swamp,Reach-1         , 1
Up Type= 0
Dn Type= 1
Dn Known WS=11.57
Boundary for River Rch & Prof#=Maple Swamp,Reach-1         , 2
Up Type= 0
Dn Type= 1
Dn Known WS=14.57
Boundary for River Rch & Prof#=Maple Swamp,Reach-1         , 3
Up Type= 0
Dn Type= 1
Dn Known WS=17.57
DSS Import GetInterval= 0
DSS Import GetPeak= 0
DSS Import FillOption= 0

--- MapleSwamp.f04 (steady flow) ---

Flow Title=FEMA Flows
Program Version=6.60
Number of Profiles= 1
Profile Names=100yr
River Rch & RM=Maple Swamp,Reach-1         ,37981
    1235
River Rch & RM=Maple Swamp,Reach-1         ,35889
    1272
River Rch & RM=Maple Swamp,Reach-1         ,34790
    1349
River Rch & RM=Maple Swamp,Reach-1         ,30685
    1483
River Rch & RM=Maple Swamp,Reach-1         ,27665
    1512
River Rch & RM=Maple Swamp,Reach-1         ,26850
    1538
River Rch & RM=Maple Swamp,Reach-1         ,24161
    2149
River Rch & RM=Maple Swamp,Reach-1         ,20976
    2293
River Rch & RM=Maple Swamp,Reach-1         ,16197
    2389
River Rch & RM=Maple Swamp,Reach-1         ,10984
    2419
River Rch & RM=Maple Swamp,Reach-1         ,9050
    2437
River Rch & RM=Maple Swamp,Reach-1         ,6432
    2544
Boundary for River Rch & Prof#=Maple Swamp,Reach-1         , 1
Up Type= 0
Dn Type= 3
Dn Slope=0.0007
DSS Import GetInterval= 0
DSS Import GetPeak= 0
DSS Import FillOption= 0

--- MapleSwamp.g04 (geometry) ---

Geom Title=Exisiting Conditions
Program Version=6.60

River Reach=Maple Swamp     ,Reach-1
Reach XY= 30
      2599537.86       777539.22      2600191.34       777563.86
      2601509.94       777021.38       2603516.3       777838.93
      2604284.17         777797.      2604939.52       777305.48
      2605392.23       777788.37      2606375.26       777827.18
      2607147.02       777474.06      2607845.55       776592.54
      2607789.75       775192.58      2608234.95       774272.83
      2608298.55       773649.78      2607752.86       771946.89
      2607911.72       771559.59      2607753.19       770823.93
      2608769.52       770113.49      2609093.13       768070.89
      2608369.51       766441.66      2607739.07       766087.62
      2606824.59       765164.442605853.00670834764743.111426114
 2605816.7131639764422.016739173      2605027.77       763868.03
      2605380.56       760938.612604564.74355951 759345.62262389
2605401.09483324755284.991817042      2606487.15       754845.34
      2608232.84       753765.46      2608584.43       752057.63

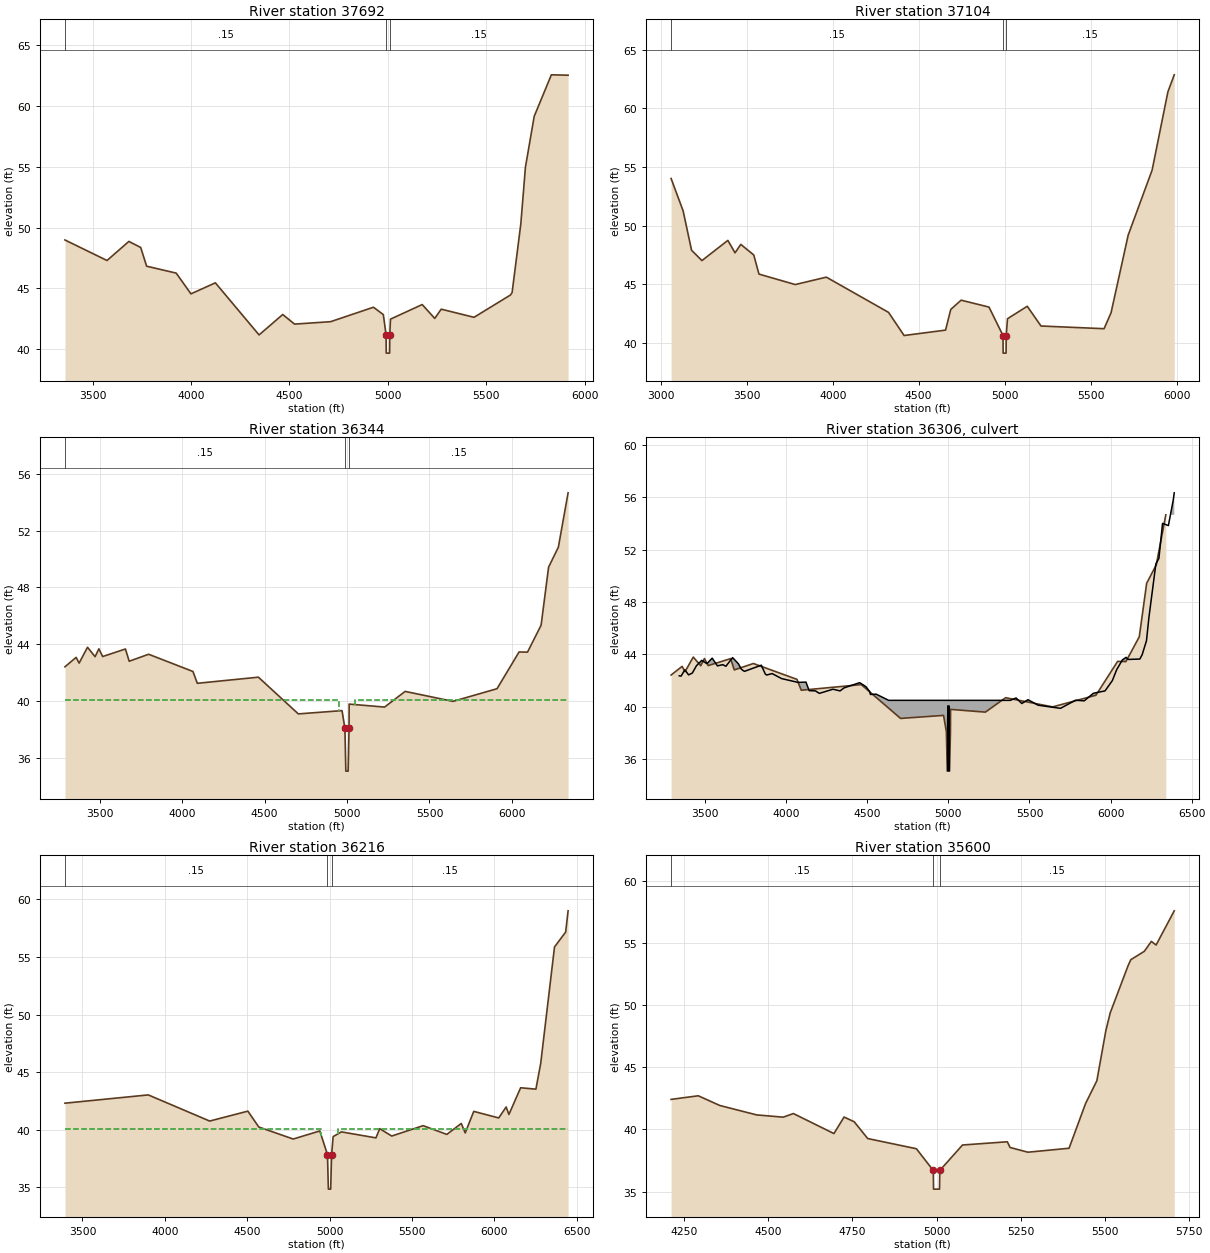
Type RM Length L Ch R = 1 ,37692   ,588.1,588.1,588.1
BEGIN DESCRIPTION:
Maple Swamp 60.0
END DESCRIPTION:
XS GIS Cut Line= 3
      2601231.68        778734.1      2601135.59       777096.71
      2600759.99       776262.47
#Sta/Elev= 30
  3359.8   48.98  3573.4   47.29  3684.5   48.86  3744.6   48.36  3774.6   46.82
  3924.9   46.25  3999.7   44.54  4123.7   45.45  4345.6   41.16  4465.8   42.84
  4525.9   42.05  4708.9   42.25  4926.7   43.44  4976.7   42.83  4990.6   41.16
  4991.4   39.66  5008.6   39.66  5009.4   41.16    5013   42.46  5174.1   43.66
  5237.7   42.52  5270.6   43.28  5437.3   42.61  5622.6   44.45  5630.6   44.65
  5674.8    50.3  5698.3   54.98  5742.8   59.16  5829.9   62.58  5914.9   62.55
#Mann= 3 ,-1,0
  3359.8     .15       0  4990.6     .05       0  5009.4     .15       0
Bank Sta=4990.6,5009.4
XS Rating Curve= 0 ,0
Exp/Cntr=0.3,0.1

Type RM Length L Ch R = 1 ,37104   ,759.3,759.3,759.3
BEGIN DESCRIPTION:
Maple Swamp 59.0
END DESCRIPTION:
XS GIS Cut Line= 3
      2601514.02       778978.47      2601709.72       777048.27
      2601654.32       776063.13
#Sta/Elev= 30
  3059.9   54.02  3129.8   51.27    3179   47.91  3239.3   47.03  3390.1   48.75
  3431.8   47.69  3465.4   48.41  3540.8   47.51    3571   45.88  3782.1   44.99
    3963   45.62  4324.8   42.62  4415.3   40.65  4656.5   41.11  4686.7   42.87
    4747   43.66  4909.2   43.07  4990.6   40.65  4991.4   39.15  5008.6   39.15
  5009.4   40.65  5016.7   42.08  5131.7   43.14  5211.7   41.46  5578.5   41.23
  5619.2   42.59  5718.8    49.2  5858.1   54.74  5949.8    61.4  5986.7   62.85
#Mann= 3 ,-1,0
  3059.9     .15       0  4990.6     .05       0  5009.4     .15       0
Bank Sta=4990.6,5009.4
XS Rating Curve= 0 ,0
Exp/Cntr=0.5,0.3

Type RM Length L Ch R = 1 ,36344   ,128.5,128.5,128.5
BEGIN DESCRIPTION:
Maple Swamp (SCL RR) US
END DESCRIPTION:
XS GIS Cut Line= 3
      2603048.88       778939.54      2602400.43       777356.93
      2601843.97       776137.06
#Sta/Elev= 30
  3289.7   42.43  3357.5   43.09  3375.7   42.69  3426.5    43.8  3472.5   43.14
  3495.5   43.69  3518.5   43.15  3656.5   43.68  3679.4   42.82  3797.1   43.31
  4065.9    42.1  4092.5   41.27  4462.7    41.7  4704.9   39.12    4970   39.35
  4987.5    38.1    4993    35.1    5007    35.1  5012.5    38.1  5013.1   39.81
    5228    39.6  5352.8    40.7  5642.8      40  5909.9   40.89  6043.5   43.47
  6094.8   43.46  6177.1   45.35  6222.6   49.43  6281.8   50.83  6340.8   54.65
#Mann= 3 ,-1,0
  3289.7     .15       0  4987.5     .05       0  5012.5     .15       0
#XS Ineff= 2 , 0
            4950    40.1    5050            40.1
Permanent Ineff=
       F       F
Bank Sta=4987.5,5012.5
XS Rating Curve= 0 ,0
Exp/Cntr=0.5,0.3

Type RM Length L Ch R = 2 ,36306   ,,,
BEGIN DESCRIPTION:
Maple Swamp (SCL RR) TOR
Structure ID: Maple Swamp_RR
Approximate Survey Structure
END DESCRIPTION:
Bridge Culvert--1,0,-1,-1, 0
Deck Dist Width WeirC Skew NumUp NumDn MinLoCord MaxHiCord MaxSubmerge Is_Ogee
15.79669,50,3,0, 60, 60, , , 0.95, 0, 1,1,,
  3339.9  3351.4  3374.5  3397.5  3420.6    3446  3478.3  3510.7    3543  3575.4
  3607.8  3627.9  3668.8  3704.8  3723.1    3742  3845.9  3870.5  3878.6  3912.8
  3970.9  4071.9  4121.4  4141.2  4180.2    4204  4288.3  4331.5  4356.5  4452.6
  4490.6  4513.8  4519.1  4554.6  4631.5  5381.3  5417.3  5452.5  5490.7  5552.9
  5691.1  5784.3  5837.4  5894.1  5965.8  6011.2  6037.4  6072.5  6095.6  6109.1
  6180.7  6195.1  6221.5  6236.3  6279.3  6298.1  6320.6  6356.6  6386.7  6392.7
   42.37   42.35   42.83   42.44   42.58   43.14   43.55    43.3   43.72   43.13
   43.22    43.1   43.76   43.29   42.87   42.71   43.18   42.51   42.43   42.54
   42.16   41.87   41.89   41.24   41.22   41.03   41.35   41.22   41.45   41.85
   41.55   41.18   40.95   40.97    40.5    40.5   40.68   40.26   40.55   40.13
   39.89   40.51   40.46   41.04   41.22   42.01   42.83   43.58   43.78   43.62
   43.65   43.99   45.05    46.8    50.9   51.33      54   53.83   55.79   56.33
   15.03   15.03   15.03   15.03   15.03   15.03   15.03   15.03   15.03   15.03
   15.03   15.03   15.03   15.03   15.03   15.03   15.03   15.03   15.03   15.03
   15.03   15.03   15.03   15.03   15.03   15.03   15.03   15.03   15.03   15.03
   15.03   15.03   15.03   15.03   15.03   15.03   15.03   15.03   15.03   15.03
   15.03   15.03   15.03   15.03   15.03   15.03   15.03   15.03   15.03   15.03
   15.03   15.03   15.03   15.03   15.03   15.03   15.03   15.03   15.03   15.03
  3339.9  3351.4  3374.5  3397.5  3420.6    3446  3478.3  3510.7    3543  3575.4
  3607.8  3627.9  3668.8  3704.8  3723.1    3742  3845.9  3870.5  3878.6  3912.8
  3970.9  4071.9  4121.4  4141.2  4180.2    4204  4288.3  4331.5  4356.5  4452.6
  4490.6  4513.8  4519.1  4554.6  4631.5  5381.3  5417.3  5452.5  5490.7  5552.9
  5691.1  5784.3  5837.4  5894.1  5965.8  6011.2  6037.4  6072.5  6095.6  6109.1
  6180.7  6195.1  6221.5  6236.3  6279.3  6298.1  6320.6  6356.6  6386.7  6392.7
   42.37   42.35   42.83   42.44   42.58   43.14   43.55    43.3   43.72   43.13
   43.22    43.1   43.76   43.29   42.87   42.71   43.18   42.51   42.43   42.54
   42.16   41.87   41.89   41.24   41.22   41.03   41.35   41.22   41.45   41.85
   41.55   41.18   40.95   40.97    40.5    40.5   40.68   40.26   40.55   40.13
   39.89   40.51   40.46   41.04   41.22   42.01   42.83   43.58   43.78   43.62
   43.65   43.99   45.05    46.8    50.9   51.33      54   53.83   55.79   56.33
   14.93   14.93   14.93   14.93   14.93   14.93   14.93   14.93   14.93   14.93
   14.93   14.93   14.93   14.93   14.93   14.93   14.93   14.93   14.93   14.93
   14.93   14.93   14.93   14.93   14.93   14.93   14.93   14.93   14.93   14.93
   14.93   14.93   14.93   14.93   14.93   14.93   14.93   14.93   14.93   14.93
   14.93   14.93   14.93   14.93   14.93   14.93   14.93   14.93   14.93   14.93
   14.93   14.93   14.93   14.93   14.93   14.93   14.93   14.93   14.93   14.93
Culvert=1,5,5,50,0.012,0.2,1,1,3,35.1,4997,34.85,4997,Culvert #1  , 0 ,38
    4997    4997
BC Culvert Barrel=1,,0
Culvert Bottom n=0.012
Culvert=1,5,5,50,0.012,0.2,1,1,3,35.1,5003,34.85,5003,Culvert #2  , 0 ,38
    5003    5003
BC Culvert Barrel=1,,0
Culvert Bottom n=0.012
BC Design=,, 0 ,, 0 ,,,,,,
BC HTab HWMax=54.65
BC Use User HTab Curves=0
BC User HTab FreeFlow(D)= 0

Type RM Length L Ch R = 1 ,36216   ,616.2,616.2,616.2
BEGIN DESCRIPTION:
Maple Swamp (SCL RR) DS
END DESCRIPTION:
XS GIS Cut Line= 3
      2603104.53        778917.1      2602509.29       777425.16
      2601898.47       776111.96
#Sta/Elev= 30
  3393.7   42.31  3899.6   43.03  4272.3   40.76  4504.2   41.62  4570.7   40.24
  4779.5    39.2    4941    39.9  4987.5   37.85    4993   34.85    5007   34.85
  5012.5   37.85    5022   39.41  5071.9   39.82  5281.9    39.3  5304.4    40.1
  5377.7   39.46  5568.2   40.36  5712.1    39.6  5799.8   40.55  5823.8   39.73
  5875.6    41.6  6027.1   41.03  6072.3   41.98    6089   41.33  6160.2   43.65
  6252.9   43.53    6282   45.76  6365.8   55.87  6433.6   57.17  6448.3   59.01
#Mann= 3 ,-1,0
  3393.7     .15       0  4987.5     .05       0  5012.5     .15       0
#XS Ineff= 2 , 0
            4950    40.1    5050            40.1
Permanent Ineff=
       F       F
Bank Sta=4987.5,5012.5
XS Rating Curve= 0 ,0
Exp/Cntr=0.5,0.3

Type RM Length L Ch R = 1 ,35600   ,537.6,537.6,537.6
BEGIN DESCRIPTION:
Maple Swamp 58.0
END DESCRIPTION:
XS GIS Cut Line= 3
      2602973.88       778501.77       2603049.7       777716.42
      2603186.61       777023.31
#Sta/Elev= 30
    4211   42.42  4291.8   42.71  4355.7   41.93  4465.6   41.17  4544.3   40.99
  4574.5   41.28    4695   39.67  4725.1      41  4755.3   40.62  4795.4   39.27
  4940.1   38.45  4990.4    36.7  4991.1    35.2  5008.9    35.2  5009.6    36.7
  5077.2   38.75  5210.4   39.01  5218.5   38.55  5271.6   38.17  5393.9   38.49
    5443   42.09  5476.5   43.92  5503.2   47.95  5516.2   49.38  5569.2   53.17
  5577.4   53.66  5617.5   54.33  5638.5   55.13  5652.6   54.84  5706.5   57.59
#Mann= 3 ,-1,0
    4211     .15       0  4990.4     .05       0  5009.6     .15       0
Bank Sta=4990.4,5009.6
XS Rating Curve= 0 ,0
Exp/Cntr=0.3,0.1

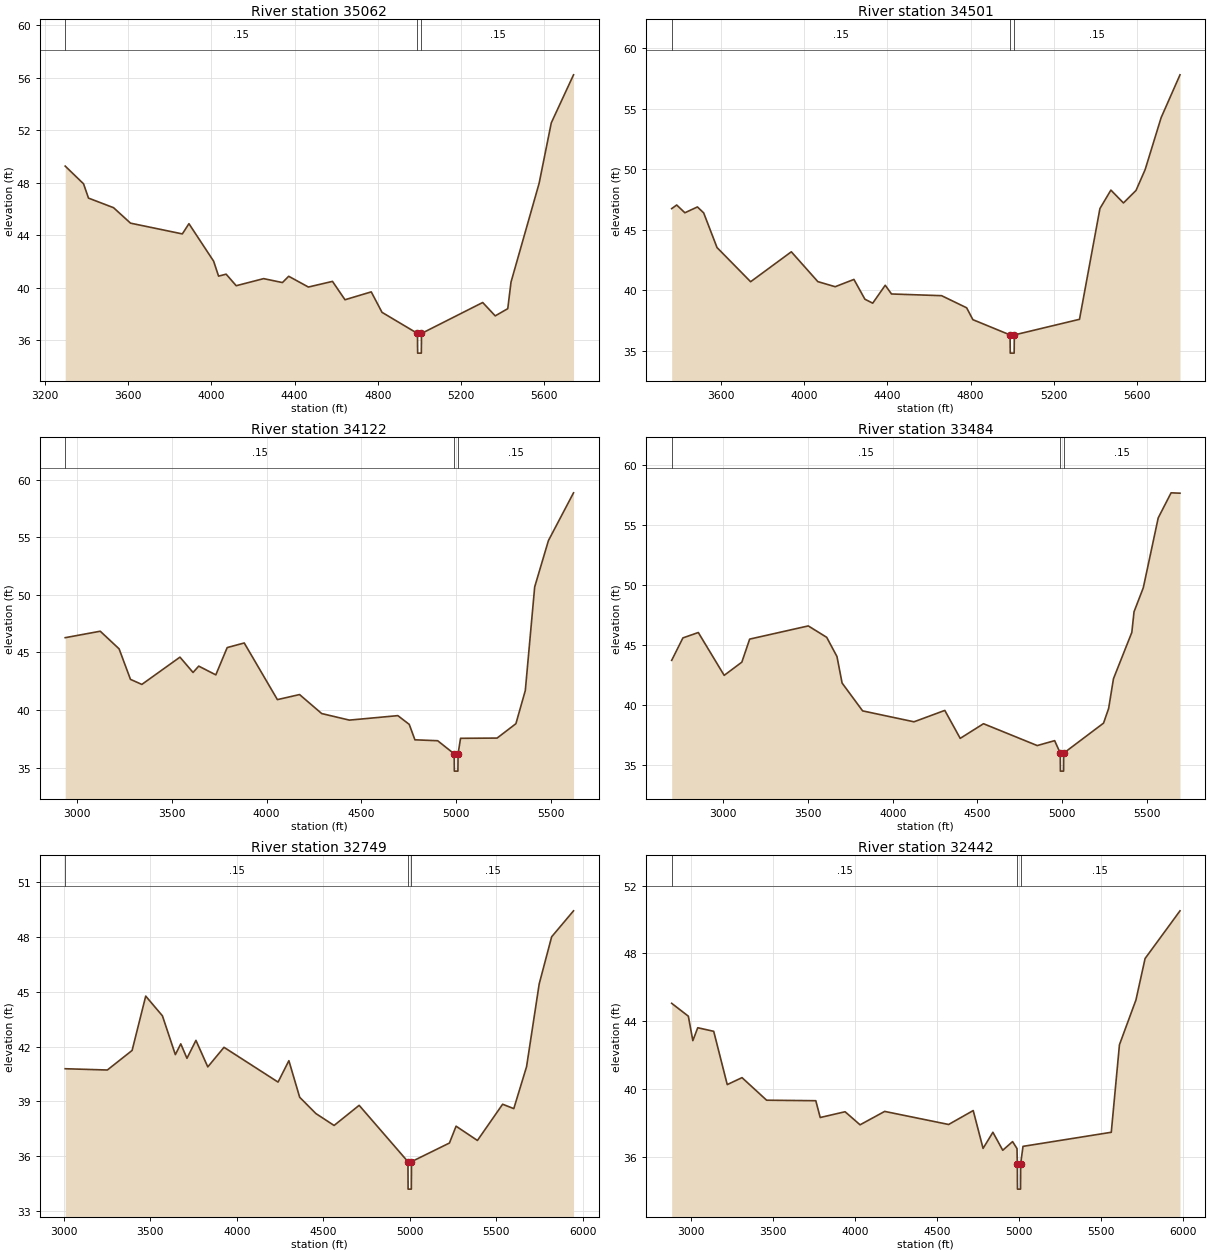
Type RM Length L Ch R = 1 ,35062   ,561.4,561.4,561.4
BEGIN DESCRIPTION:
Maple Swamp 57.0
END DESCRIPTION:
XS GIS Cut Line= 3
      2603681.94       779541.76      2603570.78        777842.8
      2603509.55       777105.03
#Sta/Elev= 30
  3297.4   49.27  3385.5   47.92  3409.4   46.83  3529.7    46.1  3611.3   44.92
  3860.4    44.1    3892   44.88  4010.7   42.02  4034.5   40.88  4070.8   41.03
  4119.2   40.15  4251.2   40.69  4341.4   40.39  4371.5   40.87    4466   40.05
  4581.9   40.48    4642   39.08  4768.2   39.68  4819.9   38.12  4990.4   36.51
  4991.1   35.01  5008.9   35.01  5009.6   36.51  5303.8   38.87    5364   37.85
  5424.2    38.4  5439.9   40.43  5574.8   47.95  5633.4   52.57  5740.3   56.23
#Mann= 3 ,-1,0
  3297.4     .15       0  4990.4     .05       0  5009.6     .15       0
Bank Sta=4990.4,5009.6
XS Rating Curve= 0 ,0
Exp/Cntr=0.3,0.1

Type RM Length L Ch R = 1 ,34501   ,378.7,378.7,378.7
XS GIS Cut Line= 5
2604019.22836304779462.3571542782604128.77974033777860.894022869
2604130.89252999777832.3713624742604136.96680026777772.156857197
 2604210.3914212777029.602973328
#Sta/Elev= 30
  3364.5   46.74  3388.6   47.04    3428    46.4  3488.1   46.88  3518.2   46.39
  3582.3   43.53  3743.7   40.71  3939.2   43.18  4066.5   40.72  4149.7    40.3
  4239.9    40.9  4292.5   39.27  4330.1   38.94  4390.2   40.42  4420.3    39.7
  4660.9   39.56  4781.2   38.56  4811.2   37.58  4989.8   36.32  4990.6   34.82
  5009.4   34.82  5010.2   36.32  5323.2   37.61  5421.4   46.75    5474   48.27
  5534.3   47.21  5594.6   48.24  5638.5   49.96  5715.1   54.24  5805.9   57.78
#Mann= 3 ,-1,0
  3364.5     .15       0  4989.8     .05       0  5010.2     .15       0
Bank Sta=4989.8,5010.2
XS Rating Curve= 0 ,0
Exp/Cntr(USF)=0,0
Exp/Cntr=0.3,0.1

Type RM Length L Ch R = 1 ,34122   ,637.7,637.7,637.7
BEGIN DESCRIPTION:
Maple Swamp 55.0
END DESCRIPTION:
XS GIS Cut Line= 3
      2604505.68       779714.18      2604448.85       777652.66
       2604300.8       777051.32
#Sta/Elev= 30
  2937.7   46.28  3122.5   46.84    3222   45.31    3282   42.66    3342   42.22
  3543.1   44.59  3612.1   43.26  3642.1   43.81  3732.2   43.05  3792.2   45.42
  3882.2   45.82  4057.1    40.9    4174   41.34  4290.8   39.69  4436.8   39.12
  4692.5   39.51  4752.6   38.75  4782.6   37.41  4902.6   37.33  4989.8   36.19
  4990.6   34.69  5009.4   34.69  5010.2   36.19  5023.3   37.54  5216.1   37.56
  5315.3   38.81  5364.9   41.69  5414.4   50.69  5486.8   54.71  5619.3   58.86
#Mann= 3 ,-1,0
  2937.7     .15       0  4989.8     .05       0  5010.2     .15       0
Bank Sta=4989.8,5010.2
XS Rating Curve= 0 ,0
Exp/Cntr=0.3,0.1

Type RM Length L Ch R = 1 ,33484   ,734.8,734.8,734.8
BEGIN DESCRIPTION:
Maple Swamp 54.0
END DESCRIPTION:
XS GIS Cut Line= 3
      2604612.74       779585.56      2604954.87       777305.48
      2604969.96       776608.55
#Sta/Elev= 30
  2694.4    43.7  2760.7   45.57  2851.7   46.02  3004.6   42.45  3108.8   43.55
  3155.1   45.47  3501.4   46.57  3610.1   45.62  3670.8   44.02  3701.1   41.81
  3822.4   39.49  4125.8   38.58  4307.8   39.53  4398.8    37.2  4536.4   38.42
  4853.9    36.6  4956.6   37.01  4989.8   35.97  4990.6   34.47  5009.4   34.47
  5010.2   35.97  5245.5   38.47  5275.5   39.69  5304.1   42.17  5412.5   46.03
  5425.6   47.75  5480.3   49.75  5568.4   55.57  5644.5   57.66  5697.1   57.63
#Mann= 3 ,-1,0
  2694.4     .15       0  4989.8     .05       0  5010.2     .15       0
Bank Sta=4989.8,5010.2
XS Rating Curve= 0 ,0
Exp/Cntr=0.3,0.1

Type RM Length L Ch R = 1 ,32749   ,307.5,307.5,307.5
BEGIN DESCRIPTION:
Maple Swamp 53.0
END DESCRIPTION:
XS GIS Cut Line= 3
      2604874.38        779711.3      2605431.29       777799.36
      2605779.99         776919.
#Sta/Elev= 30
  3008.6   40.79  3252.1   40.72  3395.3   41.79    3474   44.76  3570.7   43.68
  3645.3   41.56  3676.6   42.15  3712.4   41.36  3764.3   42.34  3832.8   40.89
  3926.5   41.96    4239   40.06  4301.5   41.23    4364   39.23  4457.7   38.34
  4562.9   37.69  4707.7   38.79  4989.8   35.71  4990.6   34.21  5009.4   34.21
  5010.2   35.71  5229.6   36.73    5268   37.65  5391.4   36.87  5537.1   38.85
  5601.6   38.61  5675.4    40.9  5748.5   45.43  5820.4      48  5946.9   49.42
#Mann= 3 ,-1,0
  3008.6     .15       0  4989.8     .05       0  5010.2     .15       0
Bank Sta=4989.8,5010.2
XS Rating Curve= 0 ,0
Exp/Cntr=0.3,0.1

Type RM Length L Ch R = 1 ,32442   ,546,546,546
BEGIN DESCRIPTION:
Maple Swamp 52.0
END DESCRIPTION:
XS GIS Cut Line= 3
      2605800.31         779949.      2605736.66       777830.85
      2605823.35       776852.38
#Sta/Elev= 30
  2880.9   45.06  2982.7    44.3    3010   42.86    3040   43.62  3137.4   43.41
    3220   40.27  3310.1   40.68  3460.2   39.35  3760.3   39.32  3787.2   38.33
  3938.9   38.67  4030.4    37.9  4180.5   38.69  4570.7   37.92  4720.7   38.74
  4780.8   36.51  4840.8   37.46  4900.8    36.4  4960.8   36.91  4987.9    36.5
  4989.8   35.61  4990.6   34.11  5009.4   34.11  5010.2   35.61  5024.5   36.63
    5563   37.46  5612.9   42.62  5713.6   45.26  5769.3    47.7  5982.3   50.51
#Mann= 3 ,-1,0
  2880.9     .15       0  4989.8     .05       0  5010.2     .15       0
Bank Sta=4989.8,5010.2
XS Rating Curve= 0 ,0
Exp/Cntr=0.3,0.1

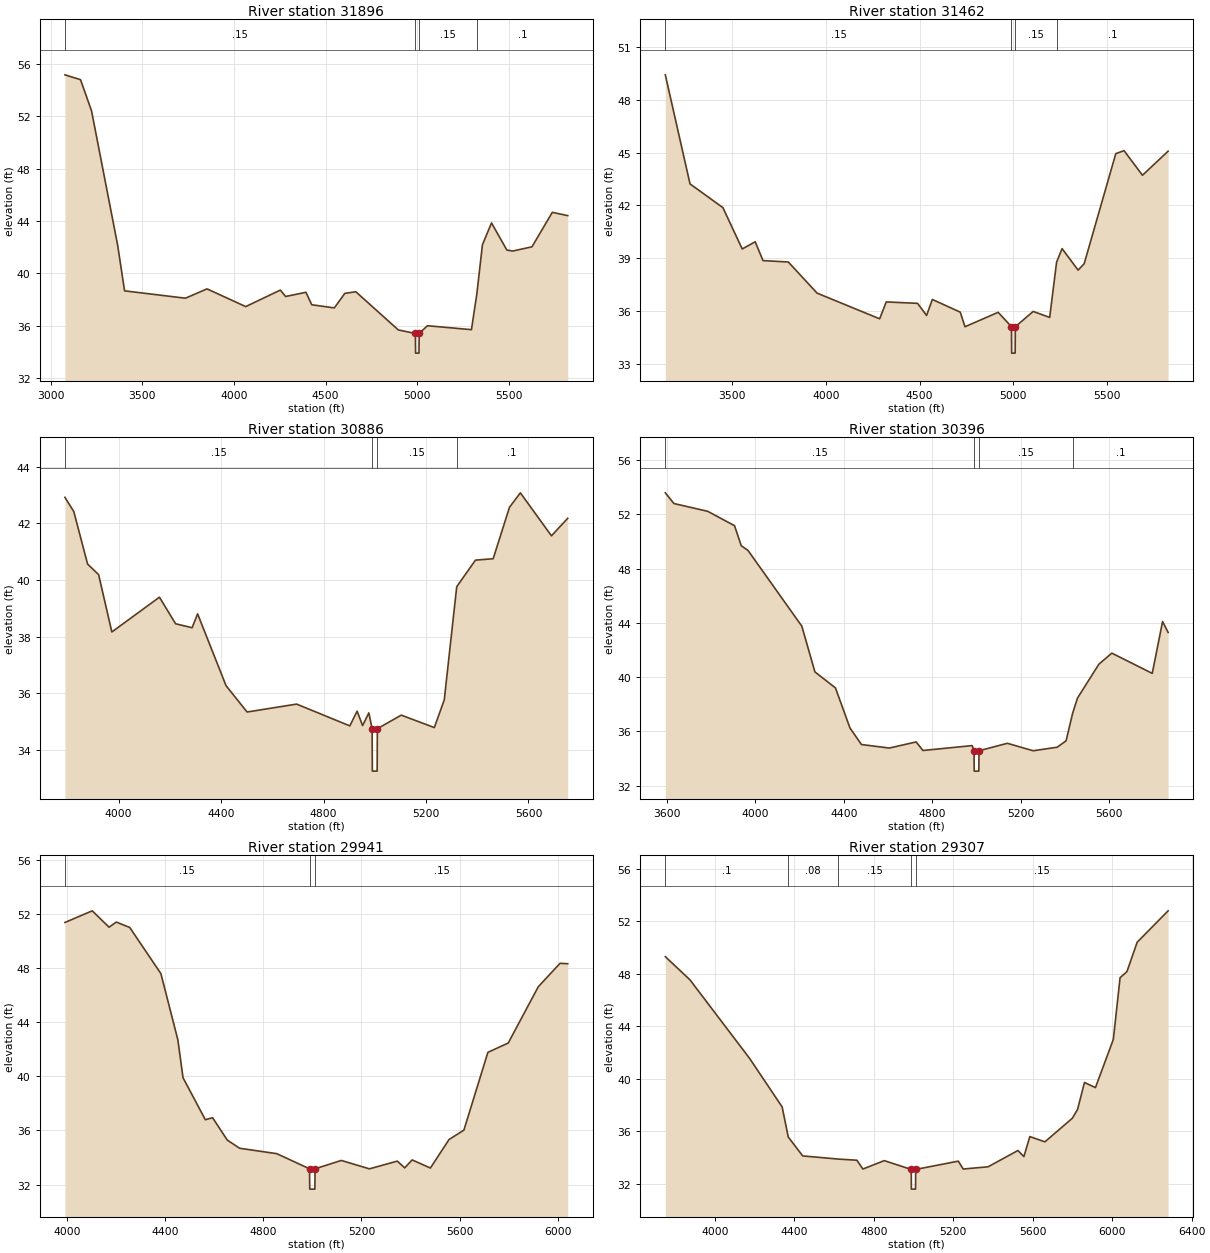
Type RM Length L Ch R = 1 ,31896   ,433.5,433.5,433.5
BEGIN DESCRIPTION:
Maple Swamp 51.0
END DESCRIPTION:
XS GIS Cut Line= 3
      2606376.23       779755.02      2606282.08       777835.33
      2606256.43       777015.03
#Sta/Elev= 30
    3078   55.15  3163.1   54.78  3223.2    52.4  3365.5   42.16  3403.4   38.67
  3735.3   38.11  3853.1   38.82  4064.2   37.47  4253.1   38.73  4281.7   38.24
  4392.8   38.56  4424.4   37.61  4547.5   37.37  4604.9   38.48  4664.9    38.6
  4896.6   35.69  4989.8   35.42  4990.6   33.92  5009.4   33.92  5010.2   35.42
  5055.4   36.01  5295.5   35.71    5325   38.44  5355.5   42.19    5405   43.85
  5488.8   41.78  5521.4   41.71  5625.6   42.03  5736.6   44.66  5820.7   44.41
#Mann= 4 ,-1,0
    3078     .15       0  4989.8     .05       0  5010.2     .15       0
    5325      .1       0
Bank Sta=4989.8,5010.2
XS Rating Curve= 0 ,0
Exp/Cntr=0.3,0.1

Type RM Length L Ch R = 1 ,31462   ,576.5,576.5,576.5
BEGIN DESCRIPTION:
Maple Swamp 50.0
END DESCRIPTION:
XS GIS Cut Line= 3
      2607085.74       779530.58      2606695.88       777717.72
       2606288.7       777001.24
#Sta/Elev= 30
  3145.7   49.42  3277.3   43.22  3452.5   41.87  3555.4   39.52  3624.5   39.93
  3666.1   38.86  3800.9   38.78  3954.3   37.01  4287.5   35.55  4322.6   36.51
  4489.5   36.43  4537.4   35.74  4568.2   36.65  4716.8   35.93  4742.1    35.1
  4918.8   35.92  4989.8    35.1  4990.6    33.6  5009.4    33.6  5010.2    35.1
  5105.3   35.97  5193.3   35.63    5230   38.77  5259.3   39.54  5344.6   38.32
  5376.9   38.68  5545.4   44.94  5589.4   45.11  5687.5   43.71  5824.1   45.08
#Mann= 4 ,-1,0
  3145.7     .15       0  4989.8     .05       0  5010.2     .15       0
    5230      .1       0
Bank Sta=4989.8,5010.2
XS Rating Curve= 0 ,0
Exp/Cntr=0.3,0.1

Type RM Length L Ch R = 1 ,30886   ,489.7,489.7,489.7
BEGIN DESCRIPTION:
Maple Swamp 49.0
END DESCRIPTION:
XS GIS Cut Line= 3
      2607905.85       778407.84      2607192.34       777431.46
      2606666.51       776892.05
#Sta/Elev= 30
  3790.7   42.92  3825.2   42.42  3879.2   40.56  3922.1   40.19  3973.8   38.16
  4159.6   39.39  4222.7   38.45  4287.1   38.31  4308.6    38.8  4419.7   36.26
  4501.8   35.33    4695   35.61  4902.7   34.84  4931.2   35.36  4952.6   34.85
    4977    35.3  4989.8   34.74  4990.6   33.24  5009.4   33.24  5010.2   34.74
  5103.6   35.22  5232.6   34.78  5271.4   35.76    5320   39.76  5393.1    40.7
  5462.3   40.75    5526   42.57  5568.4   43.08  5689.8   41.56  5753.3   42.18
#Mann= 4 ,-1,0
  3790.7     .15       0  4989.8     .05       0  5010.2     .15       0
    5320      .1       0
Bank Sta=4989.8,5010.2
XS Rating Curve= 0 ,0
Exp/Cntr=0.3,0.1

Type RM Length L Ch R = 1 ,30396   ,455,455,455
BEGIN DESCRIPTION:
Maple Swamp 48.0
END DESCRIPTION:
XS GIS Cut Line= 3
      2608928.62       777326.03      2607541.01       777087.89
      2606726.42        776791.6
#Sta/Elev= 30
  3592.1   53.58  3631.3   52.79  3783.5   52.22  3905.2   51.16  3935.7   49.68
  3966.1   49.34  4209.6   43.76  4268.9   40.39  4361.8   39.21  4427.5   36.26
  4479.4   35.04  4605.3   34.78  4727.1   35.23  4757.5    34.6  4980.4   34.96
  4988.8   34.58  4989.5   33.08  5010.5   33.08  5011.2   34.58  5139.6   35.13
  5256.1   34.58  5364.6   34.84  5405.1   35.31    5435   37.35  5456.8   38.46
  5553.7   40.96  5612.2   41.77    5795   40.28  5841.8    44.1  5866.8    43.3
#Mann= 4 ,-1,0
  3592.1     .15       0  4988.8     .05       0  5011.2     .15       0
    5435      .1       0
Bank Sta=4988.8,5011.2
XS Rating Curve= 0 ,0
Exp/Cntr=0.3,0.1

Type RM Length L Ch R = 1 ,29941   ,634.1,634.1,634.1
BEGIN DESCRIPTION:
Maple Swamp 47.0
END DESCRIPTION:
XS GIS Cut Line= 3
      2608739.78       776773.16      2607734.87       776698.22
      2606698.76       776602.69
#Sta/Elev= 30
  3992.3   51.37  4103.5   52.23  4172.1   51.02  4201.5    51.4  4256.3      51
  4383.2   47.59  4452.3    42.7  4473.4   39.89  4564.3   36.79  4593.7   36.94
  4653.9   35.28  4704.3   34.68  4855.5   34.28  4988.8   33.16  4989.5   31.66
  5010.5   31.66  5011.2   33.16    5118   33.78  5232.7   33.16  5346.3   33.73
  5376.5   33.23  5406.6   33.82    5481   33.22  5557.2   35.33  5617.5   36.02
  5715.3   41.77  5798.2   42.46  5920.6   46.62  6009.1   48.35  6040.5   48.32
#Mann= 3 ,-1,0
  3992.3     .15       0  4988.8     .05       0  5011.2     .15       0
Bank Sta=4988.8,5011.2
XS Rating Curve= 0 ,0
Exp/Cntr=0.3,0.1

Type RM Length L Ch R = 1 ,29307   ,374.7,374.7,374.7
BEGIN DESCRIPTION:
Maple Swamp 46.0
END DESCRIPTION:
XS GIS Cut Line= 3
      2609103.73       776160.39      2607855.66       776120.48
      2606574.34       776141.96
#Sta/Elev= 30
  3751.3   49.31  3875.1   47.55  4175.2   41.57  4339.2   37.87    4370   35.58
  4442.6   34.14    4620    33.9  4715.5   33.81  4745.5   33.14    4853   33.78
  4988.8   33.11  4989.5   31.61  5010.5   31.61  5011.2   33.11  5225.7   33.74
  5250.4   33.14  5375.6   33.31  5525.7   34.55  5555.7   34.09  5585.7   35.61
  5661.5   35.21  5799.7   37.01  5825.8   37.68  5860.7   39.73  5915.8   39.34
  6005.8   43.01  6039.8   47.71  6074.3   48.17  6125.8   50.41  6281.5    52.8
#Mann= 5 ,-1,0
  3751.3      .1       0    4370     .08       0    4620     .15       0
  4988.8     .05       0  5011.2     .15       0
Bank Sta=4988.8,5011.2
XS Rating Curve= 0 ,0
Exp/Cntr=0.3,0.1

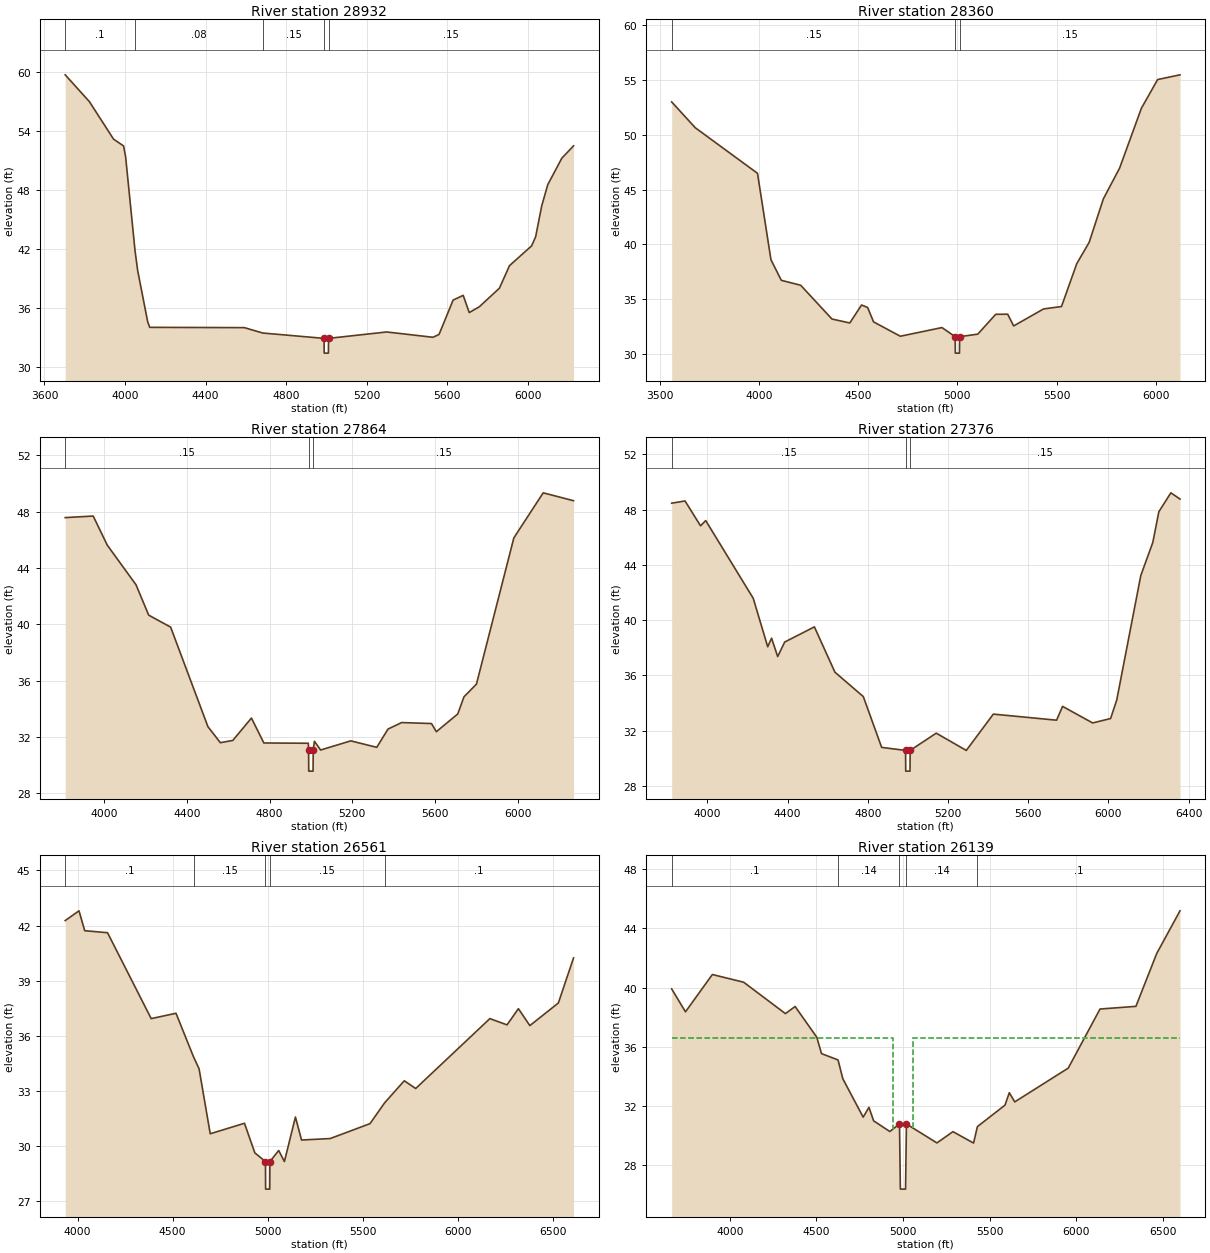
Type RM Length L Ch R = 1 ,28932   ,572.4,572.4,572.4
BEGIN DESCRIPTION:
Maple Swamp 45.0
END DESCRIPTION:
XS GIS Cut Line= 3
      2609125.02         775775.      2607828.32       775747.12
      2606606.63       775872.43
#Sta/Elev= 30
    3703   59.73    3823   57.01    3943    53.2    3993    52.5    4003   51.42
    4050   41.83    4063   39.84    4113   34.61    4123   34.07    4593   34.04
    4685   33.49  4988.8   32.95  4989.5   31.45  5010.5   31.45  5011.2   32.95
    5300    33.6    5530   33.06    5560   33.35    5630   36.84    5680   37.32
    5710   35.57    5760   36.16    5860   38.05    5910   40.34    6020   42.35
    6040   43.28    6070   46.41    6100   48.56    6170   51.26  6228.1   52.51
#Mann= 5 ,-1,0
    3703      .1       0    4050     .08       0    4685     .15       0
  4988.8     .05       0  5011.2     .15       0
Bank Sta=4988.8,5011.2
XS Rating Curve= 0 ,0
Exp/Cntr=0.3,0.1

Type RM Length L Ch R = 1 ,28360   ,496,496,496
BEGIN DESCRIPTION:
Maple Swamp 44.0
END DESCRIPTION:
XS GIS Cut Line= 3
      2609232.69       775185.95      2607792.19       775184.97
      2606675.71       775070.77
#Sta/Elev= 30
  3559.5   52.99  3678.1   50.64  3992.2   46.48    4060    38.6  4112.2   36.72
  4209.9   36.27  4367.6   33.19  4457.5   32.83  4516.9   34.47  4547.5   34.24
  4577.4   32.93  4712.2   31.62  4922.2   32.41  4988.8   31.58  4989.5   30.08
  5010.5   30.08  5011.2   31.58  5102.7   31.81  5193.2   33.62  5253.5   33.63
  5283.7   32.56  5434.4   34.11  5524.9   34.33  5601.6   38.23  5664.3   40.18
    5736   44.15  5818.2   46.97  5927.6   52.41  6009.7   55.03  6122.3   55.46
#Mann= 3 ,-1,0
  3559.5     .15       0  4988.8     .05       0  5011.2     .15       0
Bank Sta=4988.8,5011.2
XS Rating Curve= 0 ,0
Exp/Cntr=0.3,0.1

Type RM Length L Ch R = 1 ,27864   ,488,488,488
BEGIN DESCRIPTION:
Maple Swamp 43.0
END DESCRIPTION:
XS GIS Cut Line= 3
        2609159.       774784.66      2607972.86       774723.93
      2606703.37       774729.37
#Sta/Elev= 30
  3812.3   47.58  3947.6   47.69  4015.8   45.62  4154.6   42.81  4215.9   40.65
    4322    39.8  4502.2   32.73  4562.3   31.59  4622.4   31.75  4712.5   33.34
  4772.6   31.57  4987.4   31.55  4988.8   31.07  4989.5   29.57  5010.5   29.57
  5011.2   31.07  5016.9   31.69    5047   31.07  5192.9   31.72  5318.2   31.26
  5372.9   32.56  5438.7   33.02  5582.9   32.95  5606.3   32.37  5709.8   33.63
    5740   34.85  5800.2   35.75    5981   46.14  6122.9   49.34  6269.5   48.78
#Mann= 3 ,-1,0
  3812.3     .15       0  4988.8     .05       0  5011.2     .15       0
Bank Sta=4988.8,5011.2
XS Rating Curve= 0 ,0
Exp/Cntr=0.3,0.1

Type RM Length L Ch R = 1 ,27376   ,814.8,814.8,814.8
BEGIN DESCRIPTION:
Maple Swamp 42.0
END DESCRIPTION:
XS GIS Cut Line= 3
      2609380.15       774517.43      2608221.47       774304.99
      2606864.56       774337.75
#Sta/Elev= 30
    3822   48.47  3888.7   48.63    3966   46.83  3991.8   47.21  4228.8   41.58
    4301   38.07  4320.3   38.69  4350.8   37.36  4385.6   38.41  4533.8   39.51
  4636.1   36.23  4777.8   34.46  4869.3   30.78  4988.6   30.56  4989.3   29.06
  5010.7   29.06  5011.4   30.56  5141.5   31.81  5291.5   30.56  5426.3   33.19
  5741.7   32.75  5771.7   33.75  5921.7   32.55  6011.2   32.87  6041.8   34.21
  6161.8   43.23  6221.8   45.63  6251.8   47.85  6311.8   49.22  6357.3   48.77
#Mann= 3 ,-1,0
    3822     .15       0  4988.6     .05       0  5011.4     .15       0
Bank Sta=4988.6,5011.4
XS Rating Curve= 0 ,0
Exp/Cntr=0.3,0.1

Type RM Length L Ch R = 1 ,26561   ,421.8,421.8,421.8
BEGIN DESCRIPTION:
Maple Swamp 41.0
END DESCRIPTION:
XS GIS Cut Line= 3
      2609352.54       773467.51      2608287.96       773497.37
      2606680.32       773438.87
#Sta/Elev= 30
    3935   42.27  4007.6    42.8  4037.6   41.72  4157.6   41.61  4387.3   36.94
  4517.8   37.23    4610   34.86  4639.2   34.21  4697.8   30.68  4877.9   31.25
  4932.5   29.64  4988.4   29.17  4989.1   27.67  5010.9   27.67  5011.6   29.17
    5058   29.77    5088   29.17    5146   31.59  5178.1   30.34  5328.9   30.42
  5538.3   31.23    5615   32.36  5718.4   33.56  5778.5   33.14  6168.7   36.94
  6258.8    36.6  6318.8   37.48  6378.9   36.56    6529   37.79  6608.7   40.24
#Mann= 5 ,-1,0
    3935      .1       0    4610     .15       0  4988.4     .05       0
  5011.6     .15       0    5615      .1       0
Bank Sta=4988.4,5011.6
XS Rating Curve= 0 ,0
Exp/Cntr=0.5,0.3

Type RM Length L Ch R = 1 ,26139   ,91.4,91.4,91.4
BEGIN DESCRIPTION:
Maple Swamp (Adrian HWY) US
END DESCRIPTION:
XS GIS Cut Line= 3
      2609513.78       772955.11      2608184.51       773090.06
      2606597.42       773296.04
#Sta/Elev= 30
  3663.9   39.92  3743.7   38.37  3898.9   40.89  4079.8   40.37    4321   38.25
    4377   38.73  4501.9   36.66  4529.6   35.55    4625   35.12  4652.7   33.85
  4770.2   31.26  4803.5   31.92  4830.7   31.01  4924.1   30.29    4980    30.8
    4985    26.4    5015    26.4    5020    30.8  5196.2   29.52  5288.8   30.28
  5407.9   29.51    5430   30.62  5589.4   32.07  5614.4   32.91  5645.7   32.29
  5954.8   34.57  6138.4   38.56  6345.7   38.74  6466.3   42.32  6600.4   45.19
#Mann= 5 ,-1,0
  3663.9      .1       0    4625     .14       0    4980     .05       0
    5020     .14       0    5430      .1       0
#XS Ineff= 2 , 0
            4940    36.6    5060            36.6
Permanent Ineff=
       F       F
Bank Sta=4980,5020
XS Rating Curve= 0 ,0
Exp/Cntr=0.5,0.3