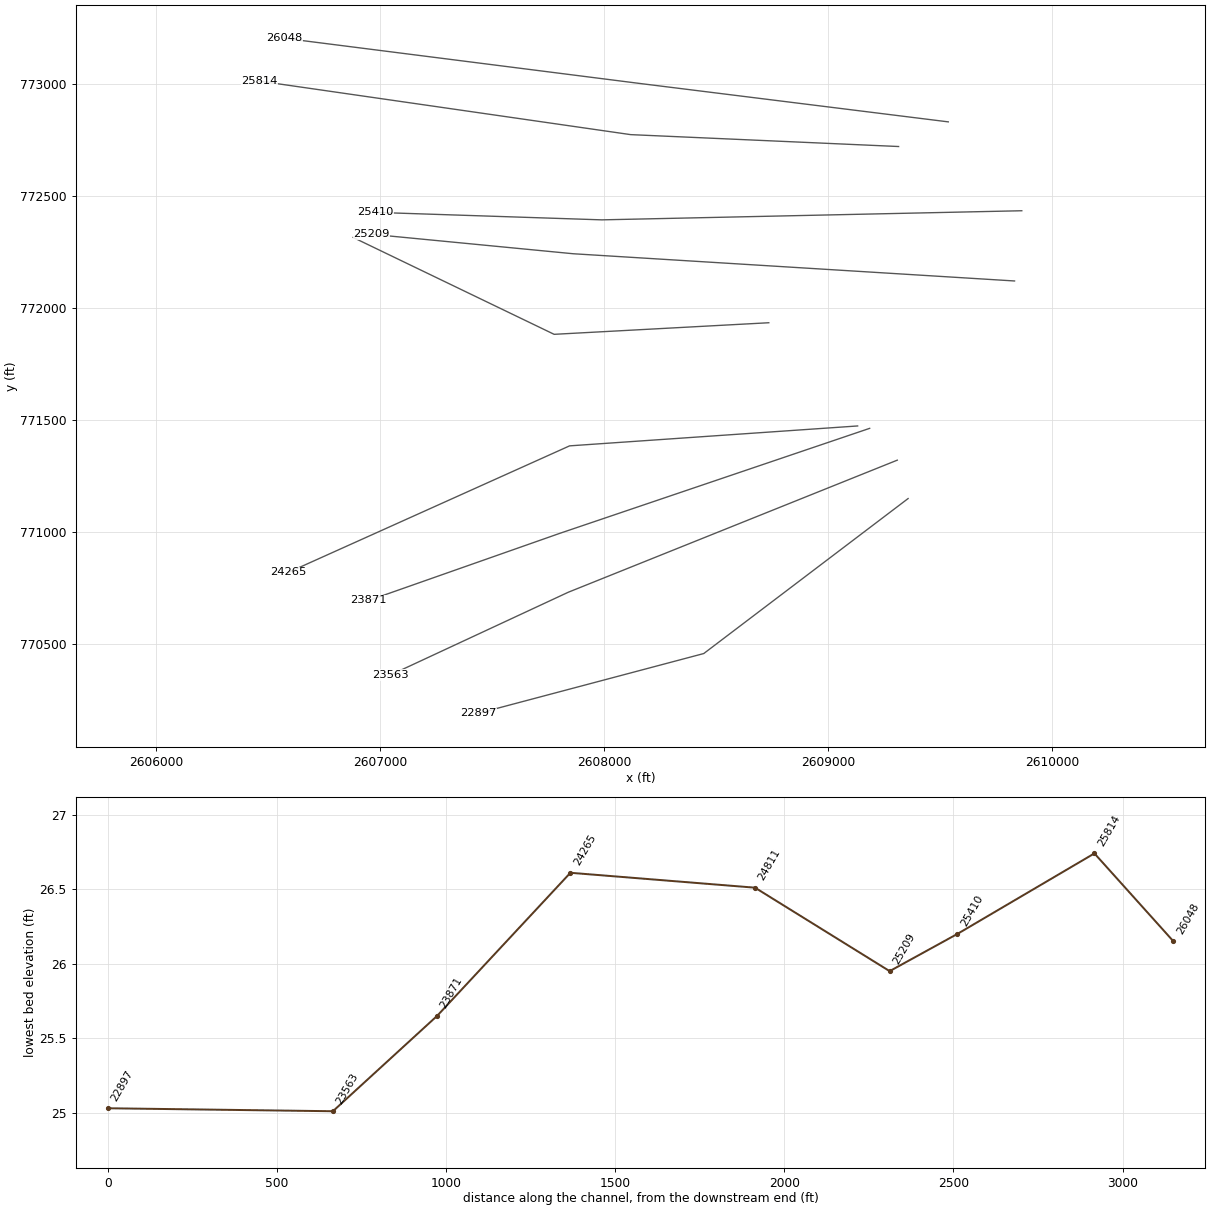
HEC-RAS study MapleSwamp.prj: S-26-65 over Maple Swamp

--- MapleSwamp.g04 (geometry) --- (continued)

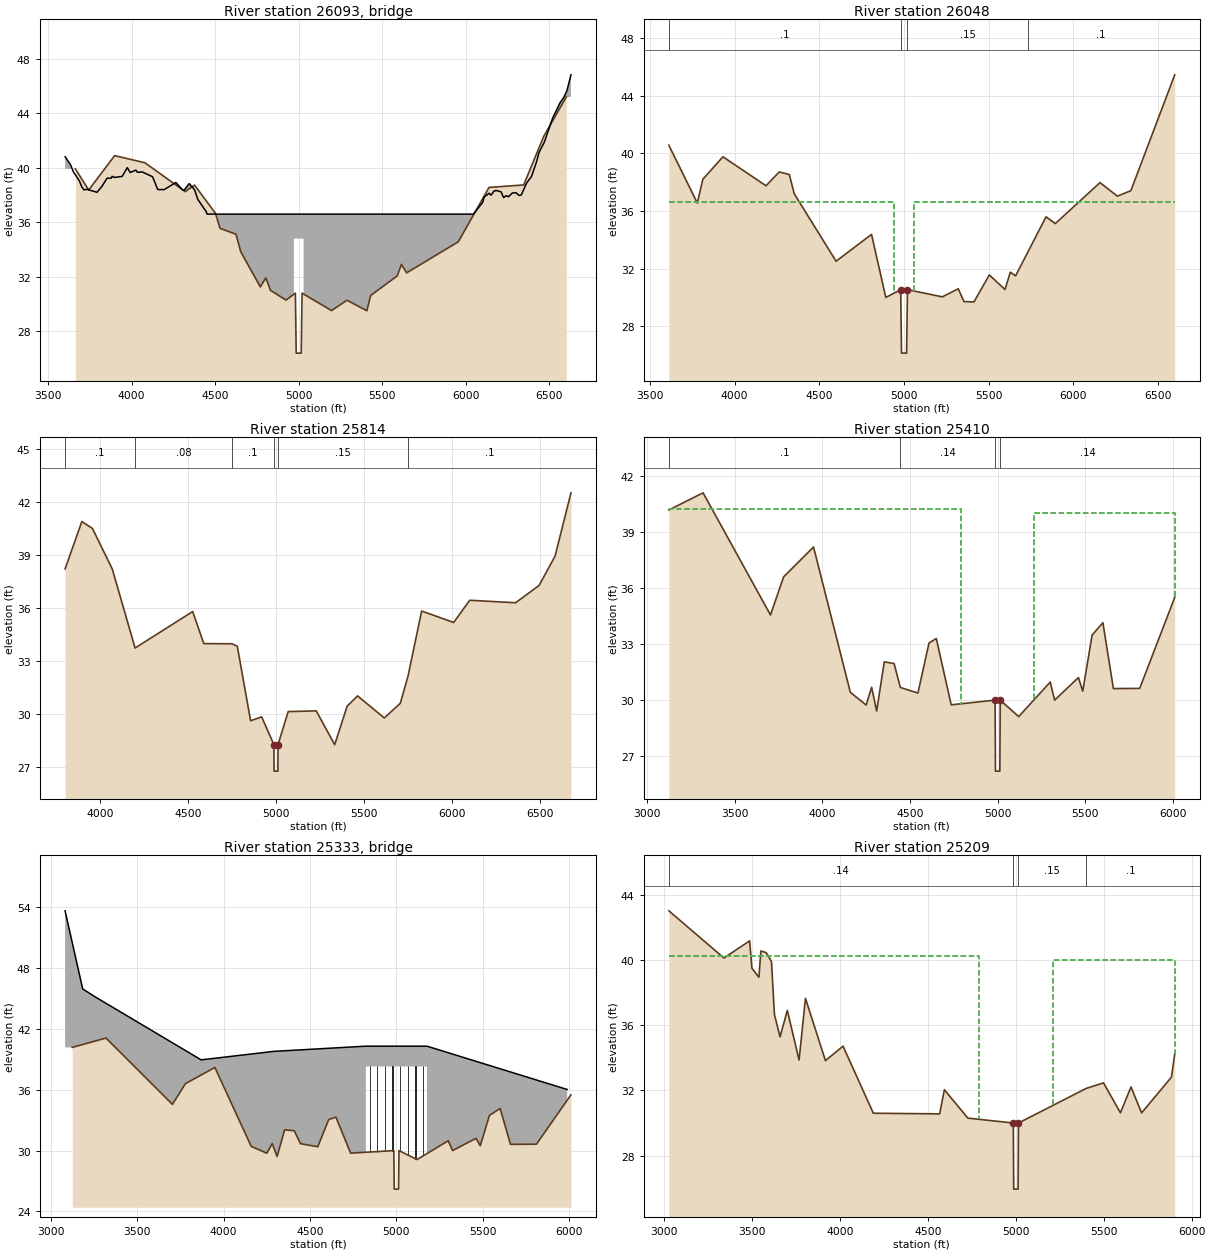
Type RM Length L Ch R = 3 ,26093   ,,,
BEGIN DESCRIPTION:
Maple Swamp (Adrian HWY) TOR
Structure ID: LDS_MPS_03
Approximate Survey Structure
END DESCRIPTION:
Bridge Culvert--1,0,-1,-1, 0
Deck Dist Width WeirC Skew NumUp NumDn MinLoCord MaxHiCord MaxSubmerge Is_Ogee
27.92324,35,3,0, 60, 60, , , 0.95, 0, 1,1,,
  3602.4  3633.8  3653.2  3687.1  3702.8  3715.4    3733  3793.3  3823.5  3853.7
  3878.7  3883.9  3898.5  3944.2  3974.4  3991.9  4025.8  4034.8  4064.9  4125.9
  4155.5  4159.2  4195.6  4264.8  4306.4  4313.8  4345.1  4376.4  4396.9    4445
  4452.1    4971    4971    5029    5029  6044.4  6099.7  6109.5  6138.4  6150.3
  6167.4  6180.5  6210.8  6225.4  6241.1  6254.4  6277.9  6301.6  6317.4  6331.8
  6362.1  6392.4  6422.6  6437.5  6469.1  6518.6  6563.6  6585.2  6604.2  6628.5
   40.81   40.25   39.68   39.05   38.59   38.38   38.42    38.2   38.65   39.24
   39.24   39.37   39.29   39.37   40.01   39.65   39.83   39.67   39.69   39.34
   38.43    38.4    38.4   38.92   38.37   38.35   38.84   38.39   37.67   36.81
    36.6    36.6    36.6    36.6    36.6    36.6   37.44   37.86   38.13   37.99
   38.28   38.34   38.23   37.81   37.95   37.87   38.15   38.16   37.97   38.01
   38.86   39.36   40.44   41.13   41.88   43.64   44.78   45.16   45.65   46.82
     6.4     6.4     6.4     6.4     6.4     6.4     6.4     6.4     6.4     6.4
     6.4     6.4     6.4     6.4     6.4     6.4     6.4     6.4     6.4     6.4
     6.4     6.4     6.4     6.4     6.4     6.4     6.4     6.4     6.4     6.4
     6.4     6.4    34.8    34.8     6.4     6.4     6.4     6.4     6.4     6.4
     6.4     6.4     6.4     6.4     6.4     6.4     6.4     6.4     6.4     6.4
     6.4     6.4     6.4     6.4     6.4     6.4     6.4     6.4     6.4     6.4
  3602.4  3633.8  3653.2  3687.1  3702.8  3715.4    3733  3793.3  3823.5  3853.7
  3878.7  3883.9  3898.5  3944.2  3974.4  3991.9  4025.8  4034.8  4064.9  4125.9
  4155.5  4159.2  4195.6  4264.8  4306.4  4313.8  4345.1  4376.4  4396.9    4445
  4452.1    4971    4971    5029    5029  6044.4  6099.7  6109.5  6138.4  6150.3
  6167.4  6180.5  6210.8  6225.4  6241.1  6254.4  6277.9  6301.6  6317.4  6331.8
  6362.1  6392.4  6422.6  6437.5  6469.1  6518.6  6563.6  6585.2  6604.2  6628.5
   40.81   40.25   39.68   39.05   38.59   38.38   38.42    38.2   38.65   39.24
   39.24   39.37   39.29   39.37   40.01   39.65   39.83   39.67   39.69   39.34
   38.43    38.4    38.4   38.92   38.37   38.35   38.84   38.39   37.67   36.81
    36.6    36.6    36.6    36.6    36.6    36.6   37.44   37.86   38.13   37.99
   38.28   38.34   38.23   37.81   37.95   37.87   38.15   38.16   37.97   38.01
   38.86   39.36   40.44   41.13   41.88   43.64   44.78   45.16   45.65   46.82
     6.4     6.4     6.4     6.4     6.4     6.4     6.4     6.4     6.4     6.4
     6.4     6.4     6.4     6.4     6.4     6.4     6.4     6.4     6.4     6.4
     6.4     6.4     6.4     6.4     6.4     6.4     6.4     6.4     6.4     6.4
     6.4     6.4    34.8    34.8     6.4     6.4     6.4     6.4     6.4     6.4
     6.4     6.4     6.4     6.4     6.4     6.4     6.4     6.4     6.4     6.4
     6.4     6.4     6.4     6.4     6.4     6.4     6.4     6.4     6.4     6.4
Abutment Skew #Up #Dn= , 2 , 2
    4971    4986
    34.8    26.4
    4971    4986
    34.8   26.15
Abutment Skew #Up #Dn= , 2 , 2
    5014    5029
    26.4    34.8
    5014    5029
   26.15    34.8
BR Coef=-1 ,-1 , 0 ,1.25, 0 ,,,0.8,0,2,0,
WSPro=,,,, 1 ,,,, 0 ,,,, 0 ,,,,-1 ,-1 ,-1 , 0 , 0 , 0 , 0 , 0
BC Design=,, 0 ,, 0 ,,,,,,
BC HTab HWMax=45.19
BC Use User HTab Curves=0
BC User HTab FreeFlow(D)= 0

Type RM Length L Ch R = 1 ,26048   ,233.6,233.6,233.6
BEGIN DESCRIPTION:
Maple Swamp (Adrian HWY) DS
END DESCRIPTION:
XS GIS Cut Line= 3
      2609536.82       772830.71      2608159.17       773002.33
      2606574.34        773203.9
#Sta/Elev= 30
  3611.7   40.56  3779.8   36.55  3812.3    38.2    3931   39.76  4185.2   37.75
  4263.5   38.71  4322.6   38.53    4352   37.19  4598.8   32.52  4807.9   34.38
  4892.3   30.01    4980   30.55    4985   26.15    5015   26.15    5020   30.55
  5225.8   30.05  5319.9   30.61  5353.7   29.72  5412.5    29.7  5503.2   31.57
  5595.8   30.56    5627   31.76  5658.3   31.51    5730   33.14  5837.9    35.6
  5892.6   35.13  6156.7   37.97  6258.8   37.03  6338.6   37.41  6597.6   45.44
#Mann= 4 ,-1,0
  3611.7      .1       0    4980     .05       0    5020     .15       0
    5730      .1       0
#XS Ineff= 2 , 0
            4940    36.6    5060            36.6
Permanent Ineff=
       F       F
Bank Sta=4980,5020
XS Rating Curve= 0 ,0
Exp/Cntr=0.5,0.3

Type RM Length L Ch R = 1 ,25814   ,404.8,404.8,404.8
BEGIN DESCRIPTION:
Maple Swamp 40.0
END DESCRIPTION:
XS GIS Cut Line= 3
      2609315.06       772720.56      2608118.74       772773.71
       2606460.8        773012.9
#Sta/Elev= 30
  3802.5   38.22  3897.7   40.91  3957.7   40.52  4070.3   38.22    4200   33.73
  4527.1    35.8    4590   33.98    4750   33.97  4780.5   33.83  4855.9    29.6
  4918.7   29.82  4988.4   28.24  4989.1   26.74  5010.9   26.74  5011.6   28.24
  5069.5   30.12  5228.9   30.16  5333.5   28.24  5404.3   30.43  5463.5   31.01
    5615   29.76    5706   30.59    5750   32.14  5827.2   35.83  6009.1   35.18
    6100   36.44  6360.7    36.3    6494   37.28    6585   38.95  6675.1   42.54
#Mann= 6 ,-1,0
  3802.5      .1       0    4200     .08       0    4750      .1       0
  4988.4     .05       0  5011.6     .15       0    5750      .1       0
Bank Sta=4988.4,5011.6
XS Rating Curve= 0 ,0
Exp/Cntr=0.5,0.3

Type RM Length L Ch R = 1 ,25410   ,200.5,200.5,200.5
BEGIN DESCRIPTION:
Maple Swamp (HWY-22) US
END DESCRIPTION:
XS GIS Cut Line= 3
      2609865.09       772433.63      2607989.93       772392.94
      2606980.28       772426.34
#Sta/Elev= 30
  3124.4   40.18  3319.5    41.1  3704.1   34.56  3779.1    36.6  3949.7    38.2
  4159.7   30.42  4249.9   29.74  4281.2   30.69  4309.8   29.42  4353.3   32.05
  4409.2   31.96    4445   30.68  4545.1   30.38  4608.4   33.06  4650.1    33.3
    4735   29.75  4985.3      30  4987.5    26.2  5012.5    26.2  5014.7      30
    5120   29.12  5300.1   30.97  5324.9      30  5460.8   31.21  5485.4   30.48
  5538.7   33.48  5600.3   34.15  5660.3   30.62  5810.4   30.63  6010.2    35.5
#Mann= 4 ,-1,0
  3124.4      .1       0    4445     .14       0  4985.3     .05       0
  5014.7     .14       0
#XS Ineff= 2 , 0
            4790   40.22    5210              40
Permanent Ineff=
       F       F
Bank Sta=4985.3,5014.7
XS Rating Curve= 0 ,0
Exp/Cntr=0.5,0.3

Type RM Length L Ch R = 3 ,25333   ,,,
BEGIN DESCRIPTION:
Maple Swamp (HWY-22) TOR
Structure ID: LDS_MPS_02A
Approximate Survey Structure
END DESCRIPTION:
Bridge Culvert--1,0,-1,-1, 0
Deck Dist Width WeirC Skew NumUp NumDn MinLoCord MaxHiCord MaxSubmerge Is_Ogee
13.09972,111,3,0, 10, 10, , , 0.95, 0, 1,1,,
  3082.7  3184.6  3252.3  3870.1  4291.6    4823    4823    5177    5177  5988.2
   53.65   45.95   45.21   38.95   39.79    40.3    40.3    40.3    40.3   36.03
    6.16    6.16    6.16    6.16    6.16    6.16    38.3    38.3    6.16    6.16
  3082.7  3184.6  3252.3  3870.1  4291.6    4823    4823    5177    5177  5988.2
   53.65   45.95   45.21   38.95   39.79    40.3    40.3    40.3    40.3   36.03
    6.16    6.16    6.16    6.16    6.16    6.16    38.3    38.3    6.16    6.16
Pier Skew, UpSta & Num, DnSta & Num=  ,4845.1, 2 ,4845.1, 2 , 0 , 0 , 0 ,0,0
     1.5     1.5
   29.61    38.3
     1.5     1.5
   29.81    38.3
Pier Skew, UpSta & Num, DnSta & Num=  ,4889.4, 2 ,4889.4, 2 , 0 , 0 , 0 ,0,0
     1.5     1.5
   29.93    38.3
     1.5     1.5
   29.91    38.3
Pier Skew, UpSta & Num, DnSta & Num=  ,4933.6, 2 ,4933.6, 2 , 0 , 0 , 0 ,0,0
     1.5     1.5
   29.41    38.3
     1.5     1.5
   28.98    38.3
Pier Skew, UpSta & Num, DnSta & Num=  ,4977.9, 2 ,4977.9, 2 , 0 , 0 , 0 ,0,0
     1.5     1.5
   30.73    38.3
     1.5     1.5
   30.39    38.3
Pier Skew, UpSta & Num, DnSta & Num=  ,5022.1, 2 ,5022.1, 2 , 0 , 0 , 0 ,0,0
     1.5     1.5
   30.29    38.3
     1.5     1.5
   30.64    38.3
Pier Skew, UpSta & Num, DnSta & Num=  ,5066.4, 2 ,5066.4, 2 , 0 , 0 , 0 ,0,0
     1.5     1.5
   29.56    38.3
     1.5     1.5
   29.14    38.3
Pier Skew, UpSta & Num, DnSta & Num=  ,5110.6, 2 ,5110.6, 2 , 0 , 0 , 0 ,0,0
     1.5     1.5
   29.33    38.3
     1.5     1.5
   29.92    38.3
Pier Skew, UpSta & Num, DnSta & Num=  ,5154.9, 2 ,5154.9, 2 , 0 , 0 , 0 ,0,0
     1.5     1.5
   29.21    38.3
     1.5     1.5
   30.32    38.3
Abutment Skew #Up #Dn= , 2 , 2
    4823    4836
    38.3   29.41
    4823    4836
    38.3   30.11
Abutment Skew #Up #Dn= , 2 , 2
    5164    5177
    29.3    38.3
    5164    5177
   30.41    38.3
BR Coef=-1 ,-1 ,-1 ,1.25, 0 ,,,0.8,0,2,0,
WSPro=,,,, 1 ,,,, 0 ,,,, 0 ,,,,-1 ,-1 ,-1 , 0 , 0 , 0 , 0 , 0
BC Design=,, 0 ,, 0 ,,,,,,
BC HTab HWMax=41.21
BC Use User HTab Curves=0
BC User HTab FreeFlow(D)= 0

Type RM Length L Ch R = 1 ,25209   ,397.9,397.9,397.9
BEGIN DESCRIPTION:
Maple Swamp (HWY-22) DS
END DESCRIPTION:
XS GIS Cut Line= 3
      2609832.75       772119.89        2607862.       772241.55
       2606962.4       772328.56
#Sta/Elev= 30
  3025.5      43  3338.8   40.11    3485   41.16  3498.2   39.48  3537.8   38.93
  3549.2   40.54  3579.3   40.44  3609.4   39.89  3626.3   36.64  3658.3   35.28
  3699.5    36.9  3766.4   33.86  3802.7   37.64  3916.4   33.82  4016.5   34.71
  4188.9    30.6  4566.2   30.56    4593   32.04  4726.8    30.3  4985.3      30
  4987.5   25.95  5012.5   25.95  5014.7      30    5400   32.12  5498.4   32.46
  5594.8   30.63    5655   32.21  5715.3   30.62    5885   32.81  5903.8   34.22
#Mann= 4 ,-1,0
  3025.5     .14       0  4985.3     .05       0  5014.7     .15       0
    5400      .1       0
#XS Ineff= 2 , 0
            4790   40.22    5210              40
Permanent Ineff=
       F       F
Bank Sta=4985.3,5014.7
XS Rating Curve= 0 ,0
Exp/Cntr=0.5,0.3

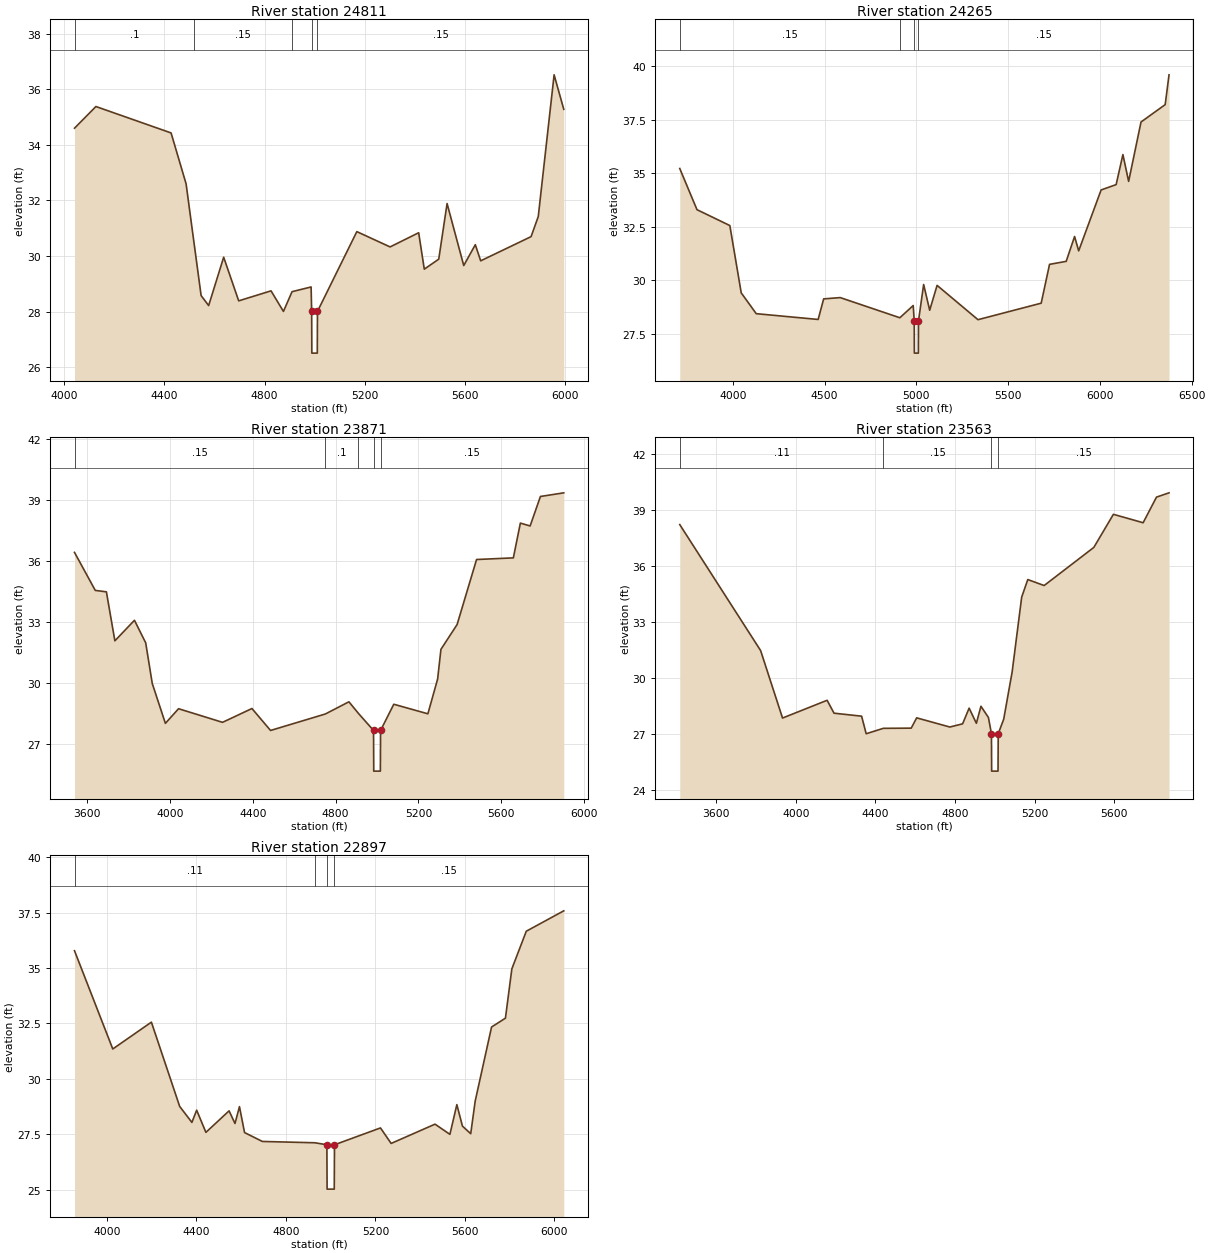
Type RM Length L Ch R = 1 ,24811   ,545.8,545.8,545.8
BEGIN DESCRIPTION:
Maple Swamp 39.0
END DESCRIPTION:
XS GIS Cut Line= 3
      2608735.49       771933.27      2607777.19       771881.52
      2606879.79       772314.29
#Sta/Elev= 30
  4040.3    34.6  4125.9   35.38  4426.4   34.43  4486.4    32.6    4520   30.35
  4546.5   28.58  4576.6   28.22  4636.7   29.96  4696.7   28.39    4826   28.75
  4875.6   28.01    4910   28.72  4986.2   28.89  4988.4   28.01  4989.1   26.51
  5010.9   26.51  5011.6   28.01    5169   30.88    5302   30.33  5416.2   30.84
  5438.7   29.53  5496.5   29.89  5529.8   31.89  5596.4   29.66  5642.7   30.41
  5664.1   29.83  5865.6    30.7  5894.3   31.42  5957.7   36.52  5996.3   35.28
#Mann= 5 ,-1,0
  4040.3      .1       0    4520     .15       0    4910      .1       0
  4988.4     .05       0  5011.6     .15       0
Bank Sta=4988.4,5011.6
XS Rating Curve= 0 ,0
Exp/Cntr=0.3,0.1

Type RM Length L Ch R = 1 ,24265   ,393.9,393.9,393.9
BEGIN DESCRIPTION:
Maple Swamp 38.0
END DESCRIPTION:
XS GIS Cut Line= 3
      2609132.24       771472.17      2607846.22       771383.23
      2606590.87       770818.07
#Sta/Elev= 30
  3710.9   35.22  3804.8    33.3  3983.8   32.56  4045.8   29.42  4127.6   28.45
  4464.9   28.18    4495   29.14  4585.2    29.2    4910   28.26  4982.8   28.83
  4988.4   28.11  4989.1   26.61  5010.9   26.61  5011.6   28.11  5039.7   29.81
  5072.6   28.61    5113   29.77  5335.8   28.17  5680.2   28.94  5725.6   30.75
  5816.3   30.89  5862.2   32.05  5884.4   31.38  6006.6   34.22  6088.5   34.47
  6125.4   35.87  6156.6   34.62  6224.1   37.39  6355.7    38.2  6376.7   39.59
#Mann= 4 ,-1,0
  3710.9     .15       0    4910      .1       0  4988.4     .05       0
  5011.6     .15       0
Bank Sta=4988.4,5011.6
XS Rating Curve= 0 ,0
Exp/Cntr=0.3,0.1

Type RM Length L Ch R = 1 ,23871   ,308.1,308.1,308.1
BEGIN DESCRIPTION:
Maple Swamp 37.0
END DESCRIPTION:
XS GIS Cut Line= 3
      2609185.92       771461.47      2607801.24       770991.98
      2606950.06       770692.59
#Sta/Elev= 30
  3537.9   36.41  3638.3   34.54    3692   34.47    3733   32.06  3827.6   33.07
    3882   31.96  3913.7   29.96  3977.1      28  4040.7   28.72  4253.4   28.05
  4395.4   28.73  4485.3   27.65    4750   28.46    4864   29.06    4910   28.49
    4983   27.65    4984   25.65    5016   25.65    5017   27.65  5080.9   28.94
  5245.6   28.47  5292.7   30.18  5308.7   31.64  5386.8   32.86  5480.9   36.06
  5658.6   36.14  5692.6   37.85  5739.7   37.71  5789.5   39.16  5902.3   39.34
#Mann= 5 ,-1,0
  3537.9     .15       0    4750      .1       0    4910     .12       0
    4983     .05       0    5017     .15       0
Bank Sta=4983,5017
XS Rating Curve= 0 ,0
Exp/Cntr=0.3,0.1

Type RM Length L Ch R = 1 ,23563   ,665.9,665.9,665.9
BEGIN DESCRIPTION:
Maple Swamp 36.0
END DESCRIPTION:
XS GIS Cut Line= 3
      2609309.18       771319.36       2607840.1       770729.17
      2607046.62       770359.65
#Sta/Elev= 30
  3416.8    38.2  3823.1   31.46  3933.2   27.85  4157.3    28.8  4191.8   28.11
  4330.6   27.95  4353.5   27.01    4440    27.3  4579.8   27.31  4607.3   27.86
  4773.8   27.37    4838   27.54  4870.8   28.38  4907.2   27.57  4930.2   28.48
  4967.8   27.88    4983   27.01    4984   25.01    5016   25.01    5017   27.01
  5044.6   27.79    5087   30.32  5134.9   34.32  5165.6   35.26  5247.8   34.94
  5497.4   36.98  5595.8   38.75  5745.2    38.3  5812.3   39.67  5875.3    39.9
#Mann= 4 ,-1,0
  3416.8     .11       0    4440     .15       0    4983     .05       0
    5017     .15       0
Bank Sta=4983,5017
XS Rating Curve= 0 ,0
Exp/Cntr=0.3,0.1

Type RM Length L Ch R = 1 ,22897   ,646.8,646.8,646.8
BEGIN DESCRIPTION:
Maple Swamp 35.0
END DESCRIPTION:
XS GIS Cut Line= 3
      2609357.48       771147.82       2608445.2       770455.39
      2607437.97       770188.06
#Sta/Elev= 30
  3854.7   35.78  4025.8   31.35  4198.5   32.56  4324.9   28.76  4379.5   28.04
  4400.9   28.59  4442.2   27.59  4545.8   28.56  4572.2   27.99  4592.2   28.75
    4615   27.58  4694.6   27.18    4930   27.12    4983   27.03    4984   25.03
    5016   25.03    5017   27.03  5222.7   27.79  5270.3   27.09  5466.5   27.96
    5533    27.5  5564.1   28.84  5589.2   27.87  5626.1   27.53  5646.1      29
  5719.3   32.34  5781.3   32.74  5809.9   34.96  5874.5   36.66  6042.1   37.58
#Mann= 4 ,-1,0
  3854.7     .11       0    4930     .15       0    4983     .05       0
    5017     .15       0
Bank Sta=4983,5017
XS Rating Curve= 0 ,0
Exp/Cntr=0.3,0.1