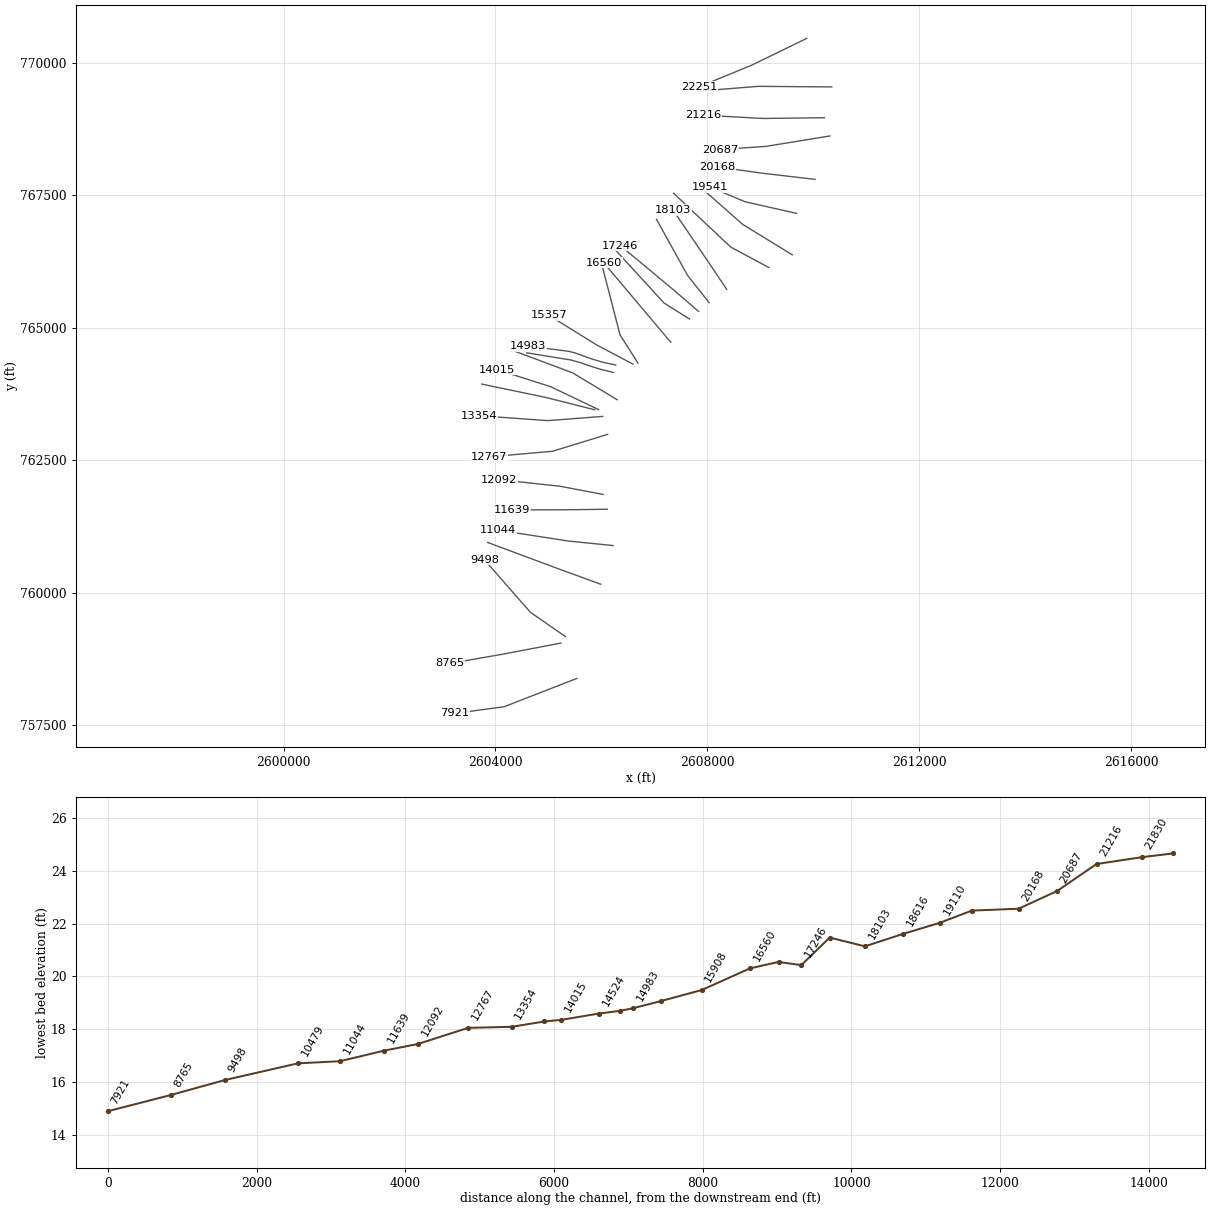
HEC-RAS study MapleSwamp.prj: S-26-65 over Maple Swamp

--- MapleSwamp.g04 (geometry) --- (continued)

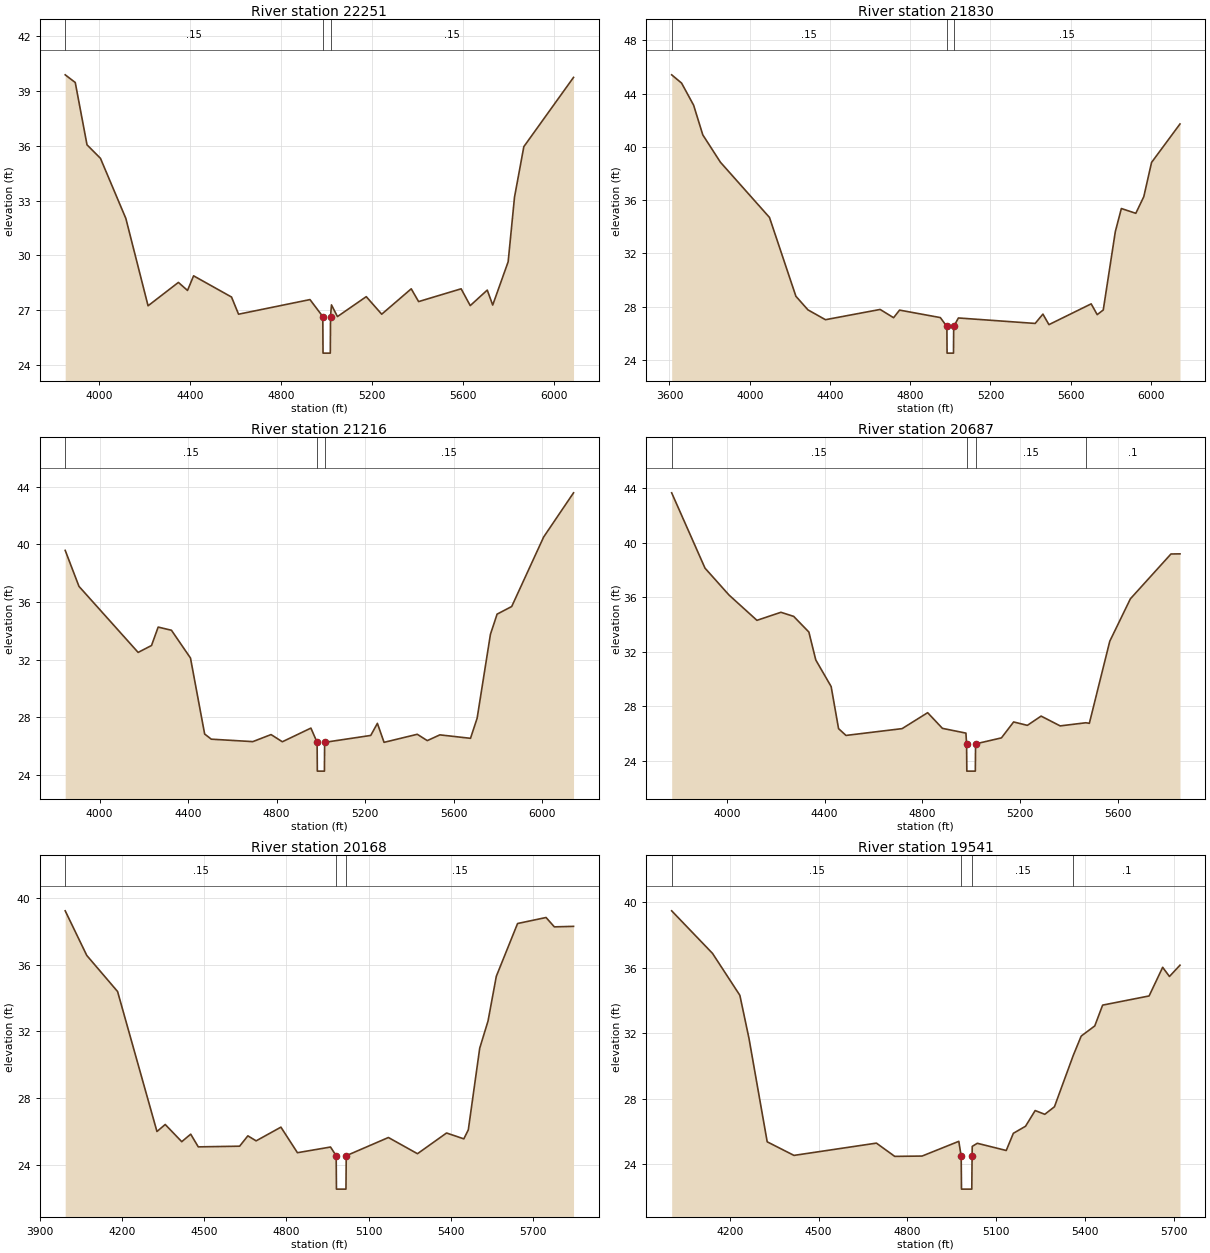
Type RM Length L Ch R = 1 ,22251   ,420.4,420.4,420.4
BEGIN DESCRIPTION:
Maple Swamp 34.0
END DESCRIPTION:
XS GIS Cut Line= 3
      2609877.57       770461.53      2608843.86       769958.05
      2607840.06       769544.65
#Sta/Elev= 30
  3850.2   39.88  3894.4   39.46  3946.1   36.05  4005.2   35.31  4116.9   32.02
  4214.6   27.24    4348   28.52  4388.1   28.08  4414.8   28.88  4581.6   27.72
  4612.5   26.78  4926.6   27.58    4983   26.65    4984   24.65    5016   24.65
    5017   26.65  5021.1   27.29  5047.4   26.65  5174.1   27.74  5242.1   26.78
  5371.9   28.17  5404.3   27.47  5591.3   28.17  5631.4   27.25  5706.2    28.1
  5730.2   27.28  5798.1   29.65  5826.1   33.19  5867.1   35.95  6085.6   39.74
#Mann= 3 ,-1,0
  3850.2     .15       0    4983     .05       0    5017     .15       0
Bank Sta=4983,5017
XS Rating Curve= 0 ,0
Exp/Cntr=0.3,0.1

Type RM Length L Ch R = 1 ,21830   ,613.8,613.8,613.8
BEGIN DESCRIPTION:
Maple Swamp 33.0
END DESCRIPTION:
XS GIS Cut Line= 3
      2610349.39       769544.66      2608960.33        769555.1
      2607818.64       769464.24
#Sta/Elev= 30
  3610.9   45.41  3660.3   44.79  3720.3   43.13  3766.1    40.9  3853.8   38.85
  4098.6    34.7  4230.3   28.78  4290.3   27.76  4377.6   27.02  4650.3   27.79
  4717.3   27.17  4747.1   27.74  4950.3   27.18    4983   26.51    4984   24.51
    5016   24.51    5017   26.51  5040.5   27.15  5423.2   26.74  5461.8   27.44
  5491.9   26.65  5702.5   28.21  5732.6    27.4  5762.7   27.75  5822.9   33.64
    5853   35.37    5925   35.01  5964.8   36.26  6003.5   38.83  6145.3   41.72
#Mann= 3 ,-1,0
  3610.9     .15       0    4983     .05       0    5017     .15       0
Bank Sta=4983,5017
XS Rating Curve= 0 ,0
Exp/Cntr=0.3,0.1

Type RM Length L Ch R = 1 ,21216   ,529.6,529.6,529.6
BEGIN DESCRIPTION:
Maple Swamp 32.0
END DESCRIPTION:
XS GIS Cut Line= 3
      2610209.99       768962.93      2609054.98       768948.78
      2607915.18       769011.18
#Sta/Elev= 30
  3844.9   39.59  3907.1   37.09  4174.4    32.5  4234.9   32.98  4264.9   34.26
  4324.9   34.04  4410.9   32.11  4474.9   26.83  4504.9   26.47  4692.4    26.3
    4775   26.79  4825.9   26.29    4955   27.24    4983   26.25    4984   24.25
    5016   24.25    5017   26.25  5225.3   26.73  5255.4   27.57  5285.4   26.25
  5435.6   26.81  5480.8   26.37  5537.6   26.77    5676   26.53    5706   27.93
  5766.1   33.76  5796.2   35.16  5862.2   35.69  6006.5   40.52  6141.5   43.59
#Mann= 3 ,-1,0
  3844.9     .15       0    4983     .05       0    5017     .15       0
Bank Sta=4983,5017
XS Rating Curve= 0 ,0
Exp/Cntr=0.3,0.1

Type RM Length L Ch R = 1 ,20687   ,518.6,518.6,518.6
BEGIN DESCRIPTION:
Maple Swamp 31.0
END DESCRIPTION:
XS GIS Cut Line= 3
      2610314.77       768618.94      2609104.15       768421.65
      2608250.25       768363.13
#Sta/Elev= 30
  3773.4   43.66    3910   38.13  4008.2   36.16  4122.7    34.3    4221   34.89
  4273.2   34.59  4335.5   33.44  4363.8   31.39  4426.7   29.44  4457.1   26.35
  4487.5   25.85  4717.5   26.35  4822.1   27.52  4882.6   26.37  4978.9   26.02
  4981.6   25.23  4982.6   23.23  5017.4   23.23  5018.4   25.23  5124.4   25.67
  5174.3   26.84  5230.6   26.59  5286.9   27.27    5365   26.55    5470   26.78
  5484.5   26.74  5568.3   32.77  5652.7   35.88  5818.9   39.17  5855.9   39.18
#Mann= 4 ,-1,0
  3773.4     .15       0  4981.6     .05       0  5018.4     .15       0
    5470      .1       0
Bank Sta=4981.6,5018.4
XS Rating Curve= 0 ,0
Exp/Cntr=0.3,0.1

Type RM Length L Ch R = 1 ,20168   ,627.7,627.7,627.7
BEGIN DESCRIPTION:
Maple Swamp 30.0
END DESCRIPTION:
XS GIS Cut Line= 3
      2610033.01       767799.45      2609031.18       767916.14
      2608190.56       768035.16
#Sta/Elev= 30
  3991.4   39.22  4070.2   36.55  4182.8   34.39  4326.7   26.01  4356.9   26.43
  4417.3    25.4    4450   25.85  4477.7   25.09  4628.7   25.13  4658.9   25.75
  4689.1   25.45  4779.7   26.27  4840.1   24.74  4960.9   25.08  4981.6   24.56
  4982.6   22.56  5017.4   22.56  5018.4   24.56  5172.5   25.65  5278.7   24.68
    5385   25.92  5448.1   25.57  5464.5   26.11  5506.2      31  5536.5   32.62
  5566.8    35.3  5644.5   38.46  5748.6   38.82  5778.9   38.26    5849   38.29
#Mann= 3 ,-1,0
  3991.4     .15       0  4981.6     .05       0  5018.4     .15       0
Bank Sta=4981.6,5018.4
XS Rating Curve= 0 ,0
Exp/Cntr=0.3,0.1

Type RM Length L Ch R = 1 ,19541   ,430.6,430.6,430.6
BEGIN DESCRIPTION:
Maple Swamp 29.0
END DESCRIPTION:
XS GIS Cut Line= 3
      2609684.52       767157.12      2608713.26       767376.83
      2608049.17       767655.77
#Sta/Elev= 30
  4004.2   39.49  4142.1   36.89  4234.4   34.33  4265.2    31.7  4326.7   25.38
  4417.1   24.55  4695.4    25.3  4757.3   24.49  4849.6   24.51  4973.6   25.41
  4981.6   24.49  4982.6   22.49  5017.4   22.49  5018.4   24.49  5018.9    25.1
  5036.1   25.29  5133.7   24.85  5157.7    25.9  5198.8   26.33  5231.3   27.29
  5263.8   27.06  5296.4   27.52    5360   30.66  5386.8   31.84  5432.6   32.46
  5459.1   33.73    5616   34.29  5661.8   36.04  5684.7   35.48  5720.3   36.17
#Mann= 4 ,-1,0
  4004.2     .15       0  4981.6     .05       0  5018.4     .15       0
    5360      .1       0
Bank Sta=4981.6,5018.4
XS Rating Curve= 0 ,0
Exp/Cntr=0.3,0.1

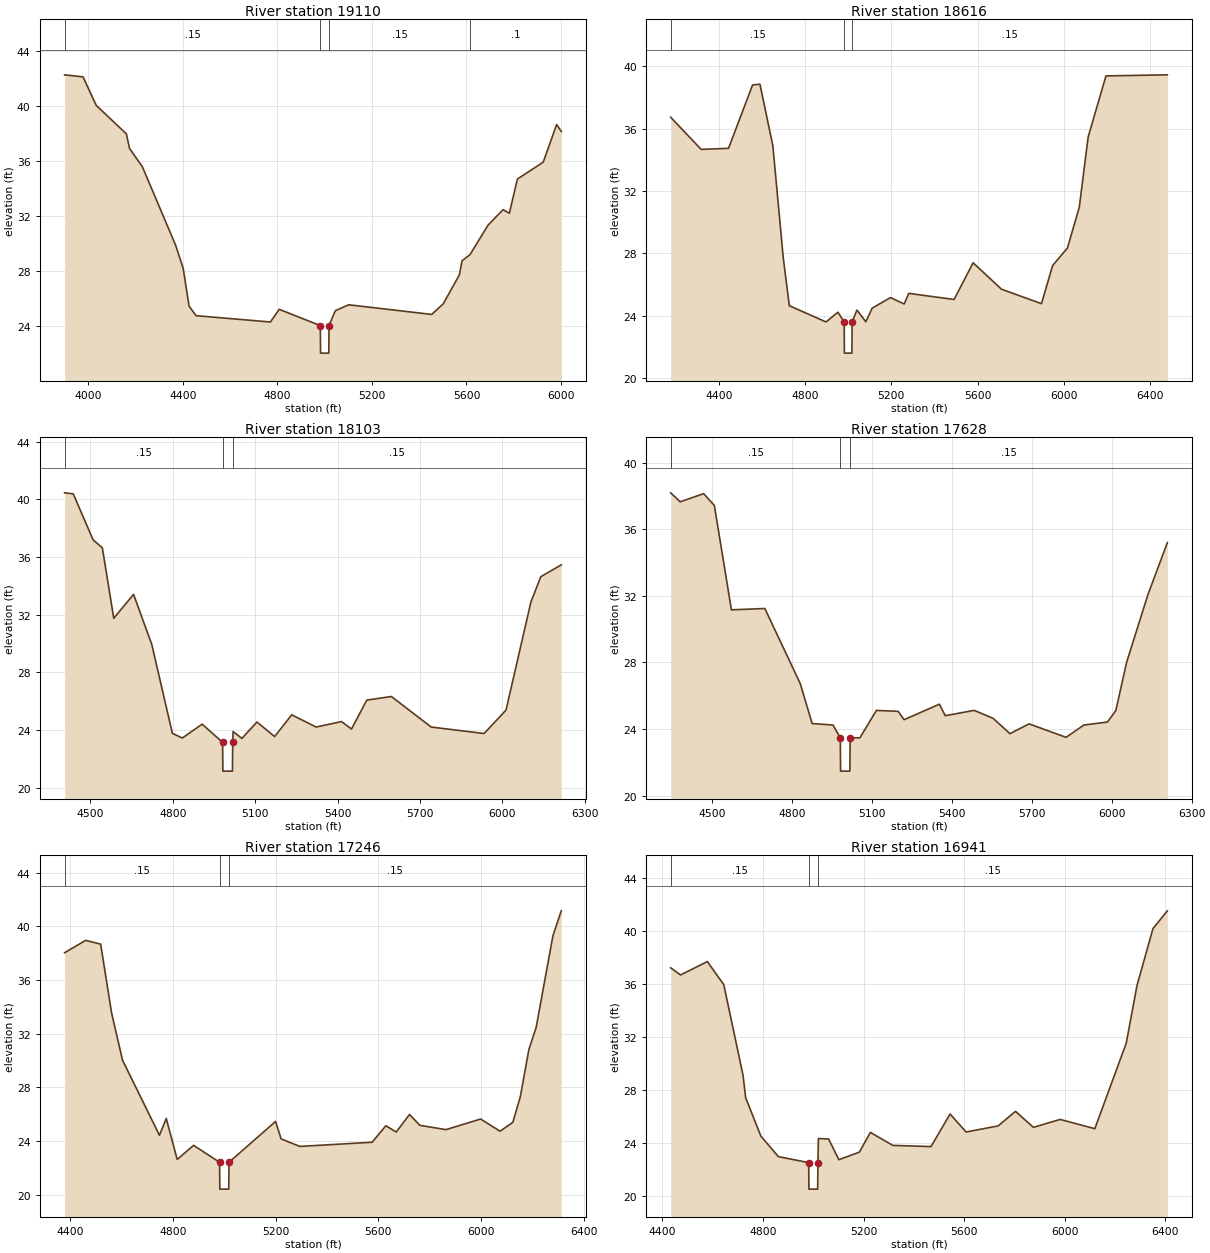
Type RM Length L Ch R = 1 ,19110   ,494.3,494.3,494.3
BEGIN DESCRIPTION:
Maple Swamp 28.0
END DESCRIPTION:
XS GIS Cut Line= 3
      2609604.06       766374.34      2608666.04       766950.23
       2607915.2       767612.83
#Sta/Elev= 30
  3899.3   42.24  3977.3   42.09  4033.1   40.02  4160.8   37.95    4174    36.9
  4228.8   35.55  4368.8   29.88  4400.8   28.21  4426.2   25.44  4455.6   24.75
  4770.2   24.29  4807.6   25.21  4981.6   24.03  4982.6   22.03  5017.4   22.03
  5018.4   24.03    5045   25.11  5101.4   25.54    5453   24.84  5501.5    25.6
    5570   27.71  5581.6   28.74    5615   29.18  5691.3   31.32  5755.1   32.45
  5781.6   32.19  5815.8   34.67  5925.1    35.9  5981.7   38.63  6001.4   38.13
#Mann= 4 ,-1,0
  3899.3     .15       0  4981.6     .05       0  5018.4     .15       0
    5615      .1       0
Bank Sta=4981.6,5018.4
XS Rating Curve= 0 ,0
Exp/Cntr=0.3,0.1

Type RM Length L Ch R = 1 ,18616   ,512.9,512.9,512.9
BEGIN DESCRIPTION:
Maple Swamp 27.0
END DESCRIPTION:
XS GIS Cut Line= 3
      2609164.39       766133.07      2608439.67       766522.45
       2607362.9       767537.82
#Sta/Elev= 30
  4177.3   36.73  4318.5   34.67  4445.5   34.74  4556.9    38.8    4591   38.85
  4650.9    34.9    4699   27.74  4727.2   24.65  4897.5   23.61  4952.6   24.23
  4981.6   23.61  4982.6   21.61  5017.4   21.61  5018.4   23.61  5040.8   24.37
    5082   23.62  5111.2   24.49  5196.1   25.17  5259.8   24.76    5281   25.44
  5491.1   25.05  5579.5    27.4  5710.7   25.71  5896.4   24.78  5947.9   27.22
  6016.8   28.35  6071.6   30.96  6112.9   35.47  6195.3   39.38    6480   39.45
#Mann= 3 ,-1,0
  4177.3     .15       0  4981.6     .05       0  5018.4     .15       0
Bank Sta=4981.6,5018.4
XS Rating Curve= 0 ,0
Exp/Cntr=0.3,0.1

Type RM Length L Ch R = 1 ,18103   ,474.6,474.6,474.6
BEGIN DESCRIPTION:
Maple Swamp 26.0
END DESCRIPTION:
XS GIS Cut Line= 3
      2608364.58       765723.91      2608034.62       766217.12
      2607352.17        767221.5
#Sta/Elev= 30
  4406.6   40.46    4438   40.39  4510.2    37.2    4544   36.64  4585.5   31.75
  4657.5   33.41  4723.6   29.95  4798.9   23.76    4835   23.44  4907.2    24.4
  4981.6   23.14  4982.6   21.14  5017.4   21.14  5018.4   23.14  5019.8   23.89
  5051.8   23.41  5106.6   24.55    5171   23.54  5233.2   25.05  5322.1    24.2
  5414.5   24.58  5450.8   24.06  5506.4   26.07  5595.9   26.32    5741    24.2
  5933.5   23.75  6013.2   25.38  6103.7   32.87  6139.9   34.64  6214.3   35.46
#Mann= 3 ,-1,0
  4406.6     .15       0  4981.6     .05       0  5018.4     .15       0
Bank Sta=4981.6,5018.4
XS Rating Curve= 0 ,0
Exp/Cntr=0.3,0.1

Type RM Length L Ch R = 1 ,17628   ,381.7,381.7,381.7
BEGIN DESCRIPTION:
Maple Swamp 25.0
END DESCRIPTION:
XS GIS Cut Line= 3
       2608033.1       765473.06      2607626.74       765986.51
       2607041.2       767044.03
#Sta/Elev= 30
  4345.2   38.19  4380.8   37.65  4468.8   38.14    4509   37.43    4573   31.16
  4698.4   31.24  4831.3   26.73  4875.9   24.33  4954.1   24.24  4981.6   23.47
  4982.6   21.47  5017.4   21.47  5018.4   23.47  5055.2   23.47  5117.1   25.12
  5198.8   25.06  5220.9   24.56  5353.3   25.49  5375.4    24.8  5484.1   25.12
  5555.1   24.64  5618.2   23.72  5689.8   24.31  5828.8    23.5  5895.6   24.24
  5984.2   24.42  6015.4   25.11    6056   28.01  6135.6   32.06  6208.8    35.2
#Mann= 3 ,-1,0
  4345.2     .15       0  4981.6     .05       0  5018.4     .15       0
Bank Sta=4981.6,5018.4
XS Rating Curve= 0 ,0
Exp/Cntr=0.3,0.1

Type RM Length L Ch R = 1 ,17246   ,305.8,305.8,305.8
BEGIN DESCRIPTION:
Maple Swamp 24.0
END DESCRIPTION:
XS GIS Cut Line= 3
      2607834.74       765306.82      2607363.54       765712.08
      2606354.95        766550.7
#Sta/Elev= 30
  4378.5   38.03  4460.1   38.95  4518.8   38.67  4561.4   33.54  4603.9   30.03
  4747.6   24.44  4774.1   25.69  4816.7   22.64  4880.5   23.69  4981.6   22.43
  4982.6   20.43  5017.4   20.43  5018.4   22.43  5199.7   25.47  5221.2   24.17
  5293.9   23.61  5575.5   23.92  5628.9   25.15  5669.3   24.68  5721.1   25.99
  5761.3   25.18    5863   24.86  5997.8   25.65  6073.3   24.74    6123    25.4
  6152.3   27.31  6185.5   30.81  6214.1   32.48  6279.3    39.3  6311.7   41.15
#Mann= 3 ,-1,0
  4378.5     .15       0  4981.6     .05       0  5018.4     .15       0
Bank Sta=4981.6,5018.4
XS Rating Curve= 0 ,0
Exp/Cntr=0.3,0.1

Type RM Length L Ch R = 1 ,16941   ,381.2,381.2,381.2
XS GIS Cut Line= 6
2607663.03915865765162.1287914282607317.86565341765380.157168759
2607188.07094694765462.3635095792607183.85640032765464.959821024
2606400.84357699766318.1206746062606231.62611154766502.444958671
#Sta/Elev= 30
  4432.9   37.25  4472.1   36.71  4578.6   37.72  4643.9   35.98  4720.5   29.15
  4730.9   27.45  4791.5   24.55  4861.3      23  4981.6   22.55  4982.6   20.55
  5017.4   20.55  5018.4   22.55  5020.3   24.37    5061   24.33  5101.7   22.77
  5183.1   23.34  5227.1   24.83  5316.1   23.85  5468.2   23.76    5544   26.22
  5607.7   24.86  5735.1   25.32  5804.2   26.42  5875.4   25.21  5981.6   25.81
  6119.7   25.11  6244.7   31.57  6287.2    35.9  6350.9   40.21  6408.1   41.55
#Mann= 3 ,-1,0
  4432.9     .15       0  4981.6     .05       0  5018.4     .15       0
Bank Sta=4981.6,5018.4
XS Rating Curve= 0 ,0
Exp/Cntr(USF)=0,0
Exp/Cntr=0.3,0.1

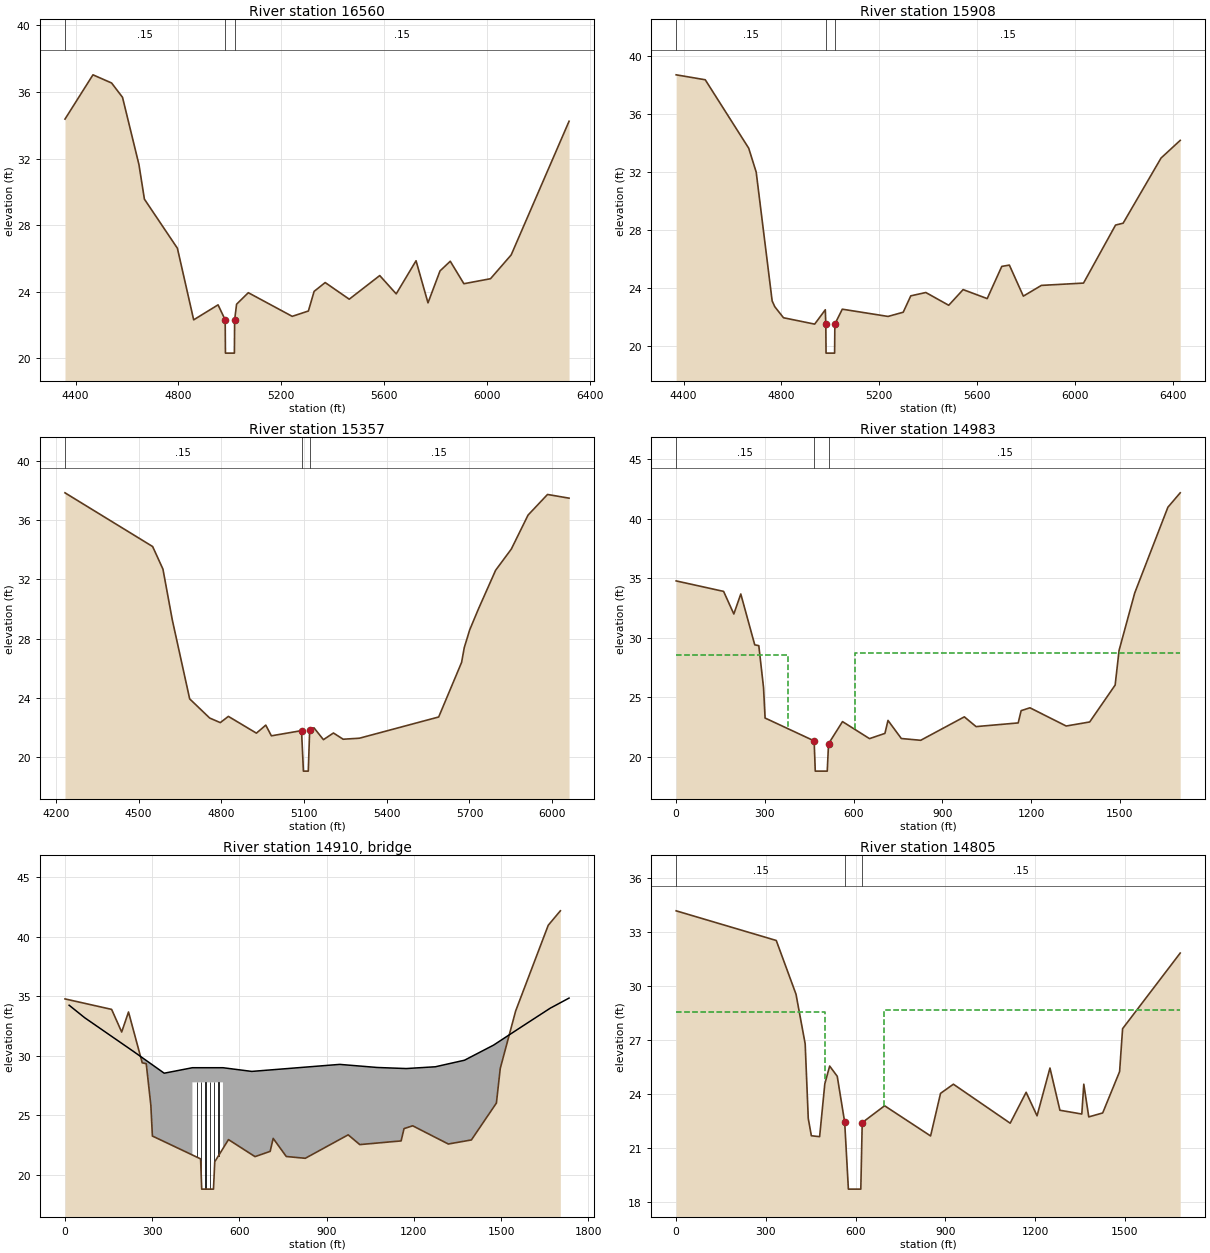
Type RM Length L Ch R = 1 ,16560   ,651.5,651.5,651.5
BEGIN DESCRIPTION:
Maple Swamp 22.0
END DESCRIPTION:
XS GIS Cut Line= 3
      2607310.11       764724.83      2606896.75       765215.26
      2606046.31       766223.49
#Sta/Elev= 30
  4358.6   34.37  4467.4   37.03  4539.8   36.54  4582.3   35.68  4646.2   31.64
  4667.5   29.56  4795.8   26.61  4859.1   22.31  4953.9   23.21  4981.6   22.31
  4982.6   20.31  5017.4   20.31  5018.4   22.31    5026   23.25  5071.6   23.94
  5242.3   22.52  5305.2   22.84  5327.5   24.02  5370.5   24.55  5464.1   23.55
  5582.7   24.97  5646.8   23.87  5723.9   25.86  5770.4   23.33  5817.2   25.25
    5857   25.83    5910   24.48  6013.5   24.78  6093.9   26.21    6319   34.24
#Mann= 3 ,-1,0
  4358.6     .15       0  4981.6     .05       0  5018.4     .15       0
Bank Sta=4981.6,5018.4
XS Rating Curve= 0 ,0
Exp/Cntr=0.3,0.1

Type RM Length L Ch R = 1 ,15908   ,551.1,551.1,551.1
BEGIN DESCRIPTION:
Maple Swamp 21.0
END DESCRIPTION:
XS GIS Cut Line= 3
      2606691.25       764329.67      2606353.35       764861.62
      2605994.11       766245.87
#Sta/Elev= 30
  4369.8   38.68  4488.7   38.34  4666.4   33.62    4697   31.97  4762.2   23.09
    4773   22.69  4808.5   21.93    4936   21.49  4979.5   22.48  4981.5   21.49
  4982.5   19.49  5017.5   19.49  5018.5   21.49  5048.9   22.52  5235.9   22.02
  5297.9   22.31  5328.9   23.44  5390.3   23.67  5483.9   22.79  5542.8   23.87
  5641.2   23.25  5700.8   25.47  5731.8   25.56  5788.9   23.42  5862.7   24.16
  6034.9   24.32  6165.8   28.32  6196.8   28.45  6351.7   32.94  6430.1   34.16
#Mann= 3 ,-1,0
  4369.8     .15       0  4981.5     .05       0  5018.5     .15       0
Bank Sta=4981.5,5018.5
XS Rating Curve= 0 ,0
Exp/Cntr=0.3,0.1

Type RM Length L Ch R = 1 ,15357   ,373.7,373.7,373.7
BEGIN DESCRIPTION:
Maple Swamp 20.0
END DESCRIPTION:
XS GIS Cut Line= 3
      2606594.28        764313.3       2605915.6       764671.07
      2605013.64       765230.37
#Sta/Elev= 30
  4232.8   37.83  4550.7   34.21  4588.1   32.69    4622   29.27  4685.1   23.94
  4757.6   22.65  4796.1   22.34  4825.5   22.76  4927.2   21.63  4961.1   22.17
  4981.5   21.45 5090.88    21.8 5097.73   19.07 5115.33   19.07 5120.35   21.83
    5136   21.99  5170.3   21.19  5206.6   21.64  5241.9   21.22  5301.1   21.29
  5588.4   22.72  5671.5    26.4  5681.1   27.39  5700.8   28.59    5733   30.02
  5794.9   32.61  5851.9   34.04  5912.6   36.33  5983.2   37.72  6061.3   37.47
#Mann= 3 ,0,0
  4232.8     .15       0 5090.88     .05       0 5120.35     .15       0
Bank Sta=5090.88,5120.35
XS Rating Curve= 0 ,0
Exp/Cntr=0.5,0.3

Type RM Length L Ch R = 1 ,14983   ,178.4,178.4,178.4
BEGIN DESCRIPTION:
Maple Swamp (HWY-65) US
END DESCRIPTION:
XS GIS Cut Line= 6
2606270.99543383 764294.697914162606020.25670458764349.151248127
2605826.05042104764407.279025191      2605492.18         764527.
2605378.51949651764553.548940603 2604612.5311043 764655.20192812
#Sta/Elev= 30
       0   34.78  160.37    33.9  194.95      32  218.45   33.68  265.63   29.41
  279.33   29.34  295.24   25.84  300.58   23.26  466.37   21.34  470.14    18.8
  510.62    18.8     515    21.1  562.23   22.96  653.45   21.53  705.54   21.97
  715.93   23.06  760.97   21.54  826.44   21.39  973.91   23.36 1013.62   22.54
 1155.94   22.85 1165.86   23.88 1195.65   24.12 1318.11   22.59 1397.54   22.93
 1483.59   26.03 1496.83   28.94 1549.78   33.77 1661.85   40.97 1703.46   42.18
#Mann= 3 ,0,0
       0     .15       0  466.37     .05       0     515     .15       0
#XS Ineff= 2 , 0
         377.495   28.54 603.875           28.69
Permanent Ineff=
       F       F
Bank Sta=466.37,515
XS Rating Curve= 0 ,0
Exp/Cntr=0.5,0.3

Type RM Length L Ch R = 3 ,14910   ,,,
BEGIN DESCRIPTION:
Maple Swamp (HWY-65) TOR
Structure ID: LDS_MPS_02
Approximate Survey Structure
END DESCRIPTION:
Bridge Culvert--1,0,-1,-1, 0
Deck Dist Width WeirC Skew NumUp NumDn MinLoCord MaxHiCord MaxSubmerge Is_Ogee
60.69,27.5,3,0, 18, 17, , , 0.95, 0, 2,2,,
  14.185  67.655 235.905 341.185 438.185 438.185 543.185 543.185 642.285 944.585
1073.6851173.3851273.5851373.7851473.7851573.9851668.5851733.385
   34.25    33.2   30.36   28.54      29      29      29      29   28.69   29.28
   29.02   28.93   29.08   29.63    30.9    32.5      34   34.85
                                           27.77   27.77
                                                                
       0  143.48  341.73     447     544     544     649     649   748.1  1050.4
  1149.5  1249.2  1349.4  1449.6  1549.6  1649.8  1719.2
   34.25    33.2   30.36   28.54      29      29      29      29   28.69   29.28
   29.02   28.93   29.08   29.63    30.9    32.5      34
                                           27.77   27.77
                                                        
Pier Skew, UpSta & Num, DnSta & Num=  ,453.185, 2 ,559, 2 , 0 , 0 , 0 ,,
       1       1
   13.99   27.77
       1       1
   13.99   27.77
Pier Skew, UpSta & Num, DnSta & Num=  ,468.185, 2 ,574, 2 , 0 , 0 , 0 ,,
       1       1
   13.99   27.77
       1       1
   13.99   27.77
Pier Skew, UpSta & Num, DnSta & Num=  ,483.185, 2 ,589, 2 , 0 , 0 , 0 ,,
       1       1
   13.99   27.77
       1       1
   13.99   27.77
Pier Skew, UpSta & Num, DnSta & Num=  ,498.185, 2 ,604, 2 , 0 , 0 , 0 ,,
       1       1
   13.99   27.77
       1       1
   13.99   27.77
Pier Skew, UpSta & Num, DnSta & Num=  ,513.185, 2 ,619, 2 , 0 , 0 , 0 ,,
       1       1
   13.99   27.77
       1       1
   13.99   27.77
Pier Skew, UpSta & Num, DnSta & Num=  ,528.185, 2 ,634, 2 , 0 , 0 , 0 ,,
       1       1
   13.99   27.77
       1       1
   13.99   27.77
Abutment Skew #Up #Dn= , 2 , 2
 438.185 458.185
    27.7    17.7
     544     564
    27.7    17.7
Abutment Skew #Up #Dn= , 2 , 2
 523.185 543.185
   17.77   27.77
     629     649
   17.77   27.77
BR Coef=-1 , 1 , 1 ,0.9, 0 ,,,0.8,0,1.2,0,
WSPro=,,,, 1 ,,,, 0 ,,,, 0 ,,,,-1 ,-1 ,-1 , 0 , 0 , 0 , 0 , 0
BC Design=,, 0 ,, 0 ,,6,453.185,559,15,1
BC HTab HWMax=42.97
BC Use User HTab Curves=0
BC User HTab FreeFlow(D)= 0

Type RM Length L Ch R = 1 ,14805   ,280.5,280.5,280.5
BEGIN DESCRIPTION:
Maple Swamp (HWY-65) DS
END DESCRIPTION:
XS GIS Cut Line= 6
2606230.15242302764153.3335826612605956.41891485764221.747375249
2605717.76125913764299.580046683 2605609.6181506764338.869154525
2605425.12236869  764389.45403362604591.13352491764525.198147551
#Sta/Elev= 30
       0   34.19  334.55   32.54  400.54   29.55  431.18   26.79  441.53   22.63
  451.88   21.67  479.49   21.62  496.83   24.56  513.07   25.55  538.37   24.98
  563.19   22.43  575.61    18.7  617.11    18.7  621.84    22.4  696.63   23.34
  850.33   21.66  883.58   24.03  926.51   24.54 1116.29   22.37 1169.63   24.09
 1206.05   22.78 1249.26   25.44 1282.51   23.09 1355.65   22.88 1362.29   24.54
 1378.92   22.72 1425.46   22.94 1481.97   25.24 1491.95   27.63 1684.52   31.84
#Mann= 3 ,0,0
       0     .15       0  563.19     .05       0  621.84     .15       0
#XS Ineff= 2 , 0
         498.895   28.54 694.105           28.69
Permanent Ineff=
       F       F
Bank Sta=563.19,621.84
XS Rating Curve= 0 ,0
Exp/Cntr=0.5,0.3

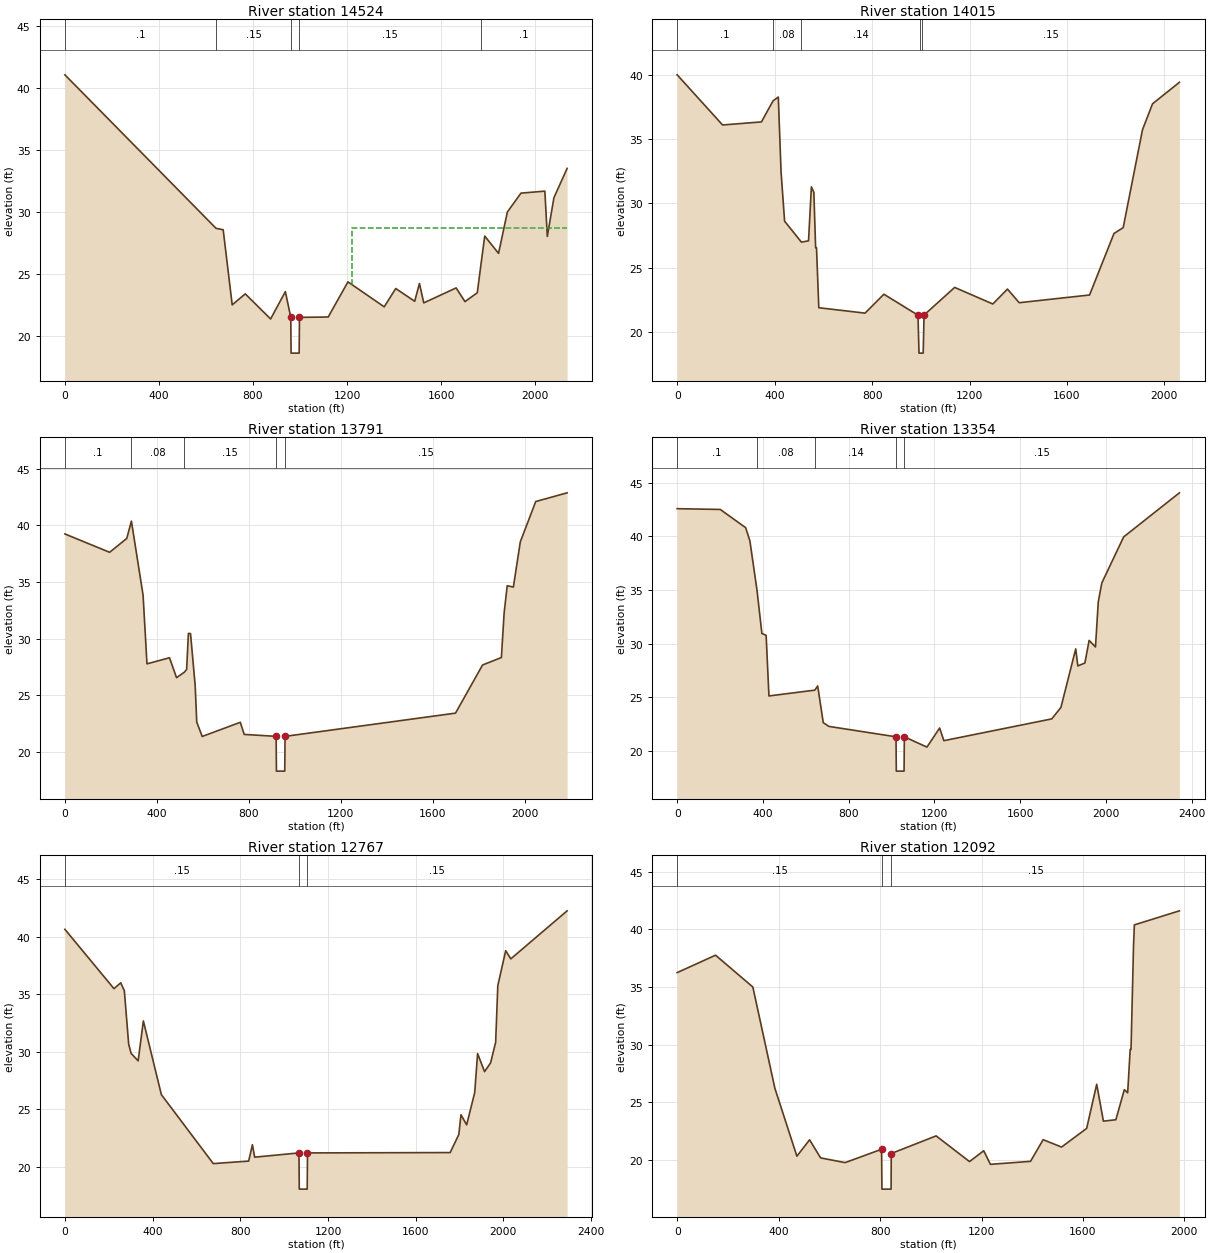
Type RM Length L Ch R = 1 ,14524   ,509.7,509.7,509.7
BEGIN DESCRIPTION:
Maple Swamp 19.0
END DESCRIPTION:
XS GIS Cut Line= 3
       2606299.2       763639.26      2605460.96       764145.41
      2604377.67       764551.49
#Sta/Elev= 30
       0   41.09   642.6   28.69   673.2   28.57   711.6    22.5   767.1   23.39
     875   21.36   937.7   23.57   960.7   21.49961.9998    18.6996.4001    18.6
   997.7   21.49  1119.9   21.52    1204   24.36  1358.2   22.34  1407.2   23.82
  1487.8   22.79    1508   24.23  1526.4   22.66  1664.1   23.87  1701.6   22.76
  1754.1   23.48  1768.1   25.54  1785.7   28.06  1844.5   26.66  1881.9      30
  1939.8   31.53  2041.4   31.69  2051.9   28.03    2080   31.16  2136.1   33.53
#Mann= 5 ,-1,0
       0      .1       0   642.6     .15       0   960.7    .052       0
   997.7     .15       0  1768.1      .1       0
#XS Ineff= 2 , 0
                         1221.89           28.69
Permanent Ineff=
       F       F
Bank Sta=960.7,997.7
XS Rating Curve= 0 ,0
Exp/Cntr=0.5,0.3

Type RM Length L Ch R = 1 ,14015   ,224,224,224
BEGIN DESCRIPTION:
Maple Swamp 18.0
END DESCRIPTION:
XS GIS Cut Line= 3
      2605946.63       763453.24      2605045.68       763884.86
      2604033.18       764206.97
#Sta/Elev= 30
       0      40   186.3    36.1   345.9   36.34   393.6   37.98   415.1   38.27
   426.4   32.44   440.9   28.62     510   26.99   539.1   27.09   550.9   31.29
     561   30.86   568.2   26.56   571.9   26.56   581.3   21.89   771.2   21.47
   848.4   22.94  988.45   21.31   992.6   18.36 1009.84   18.36 1013.27   21.32
    1139   23.47  1295.7   22.18  1355.7   23.34  1403.9   22.28  1692.7   22.88
  1792.9   27.66  1830.8   28.12    1910   35.73  1951.3   37.75  2061.5   39.42
#Mann= 5 ,-1,0
       0      .1       0   393.6     .08       0     510     .14       0
996.2998    .052       0  1004.7     .15       0
Bank Sta=988.45,1013.27
XS Rating Curve= 0 ,0
Exp/Cntr=0.3,0.1

Type RM Length L Ch R = 1 ,13791   ,437.1,437.1,437.1
BEGIN DESCRIPTION:
Maple Swamp 17.0
END DESCRIPTION:
XS GIS Cut Line= 3
      2605872.17       763450.02      2604962.43        763680.6
      2603742.02       763935.25
#Sta/Elev= 30
       0   39.24   194.6   37.62   269.1   38.84   289.4   40.37   340.2   33.83
   357.1   27.77   455.2   28.31   485.7   26.55   519.5   27.03   529.7   27.28
   537.4   30.46   546.6   30.44   566.9   25.84   573.7   22.63   597.4   21.36
   763.2   22.61   780.2   21.54919.1001   21.37920.3999    18.3956.6001    18.3
957.8999   21.37  1699.6   23.42  1817.3   27.67  1899.2   28.33  1911.2   32.28
  1924.6   34.67  1951.4   34.55  1981.5   38.54  2048.6    42.1  2185.2   42.87
#Mann= 5 ,-1,0
       0      .1       0   289.4     .08       0   519.5     .15       0
919.1001    .052       0957.8999     .15       0
Bank Sta=919.1001,957.8999
XS Rating Curve= 0 ,0
Exp/Cntr=0.3,0.1

Type RM Length L Ch R = 1 ,13354   ,586,586,586
BEGIN DESCRIPTION:
Maple Swamp 16.0
END DESCRIPTION:
XS GIS Cut Line= 3
      2606024.98         763325.      2604987.82       763245.56
      2603688.63       763338.41
#Sta/Elev= 30
       0   42.57     201    42.5   319.4    40.8   339.2   39.57   372.1      35
   395.1   30.94   414.9   30.76     428   25.11   641.9   25.65   655.4   26.04
   681.4   22.62   707.7   22.27  1020.8    21.3  1022.1    18.1  1058.3    18.1
  1059.6    21.3    1165   20.34  1224.2   22.12    1244   20.94  1747.2   22.97
    1790   24.04  1859.1    29.5  1868.9   27.91  1901.8   28.18  1921.6   30.29
  1951.2   29.68  1964.3   33.89  1980.8   35.65  2082.7   39.94  2342.7   44.05
#Mann= 5 ,-1,0
       0      .1       0   372.1     .08       0   641.9     .14       0
  1020.8    .052       0  1059.6     .15       0
Bank Sta=1020.8,1059.6
XS Rating Curve= 0 ,0
Exp/Cntr=0.3,0.1

Type RM Length L Ch R = 1 ,12767   ,675.8,675.8,675.8
BEGIN DESCRIPTION:
Maple Swamp 15.0
END DESCRIPTION:
XS GIS Cut Line= 3
      2606117.24       762986.01      2605078.07       762666.77
      2603879.09       762561.43
#Sta/Elev= 30
       0   40.66   223.8    35.5   254.7   36.01   271.1   35.32   290.9   30.67
     302   29.87   334.1   29.22   357.9   32.69     440   26.28   676.8   20.28
   838.2    20.5   855.3   21.92   865.6   20.84  1067.7   21.21    1069   18.06
  1105.2   18.06  1106.5   21.21  1757.2   21.24  1796.7   22.81  1806.6   24.53
  1832.5   23.65  1869.2   26.46  1882.4   29.85  1914.2   28.28  1941.6   29.04
  1964.7   30.83  1974.6   35.76  2010.5    38.8  2033.9   38.09  2290.7   42.27
#Mann= 3 ,-1,0
       0     .15       0  1067.7    .052       0  1106.5     .15       0
Bank Sta=1067.7,1106.5
XS Rating Curve= 0 ,0
Exp/Cntr=0.3,0.1

Type RM Length L Ch R = 1 ,12092   ,452.6,452.6,452.6
BEGIN DESCRIPTION:
Maple Swamp 14.0
END DESCRIPTION:
XS GIS Cut Line= 3
       2606032.3       761851.79      2605221.51       762006.37
      2604073.23       762130.79
#Sta/Elev= 30
       0   36.24   151.3   37.75   298.3   34.99   385.1   26.21     472   20.31
   522.1   21.73   565.5   20.16   662.3   19.75     806   20.91807.2998   17.45
   843.5   17.45   844.1   20.54  1021.1   22.07  1152.7   19.84  1208.8   20.78
  1235.2    19.6  1393.3   19.86  1443.1   21.74  1515.7    21.1  1614.7   22.72
  1654.3   26.55  1680.7   23.35  1729.8   23.47  1763.2   26.08  1776.4   25.81
  1786.3   29.57  1789.6   29.56  1799.5   38.59  1802.8   40.38  1980.4    41.6
#Mann= 3 ,-1,0
       0     .15       0     806    .052       0844.7998     .15       0
Bank Sta=806,844.1
XS Rating Curve= 0 ,0
Exp/Cntr=0.3,0.1

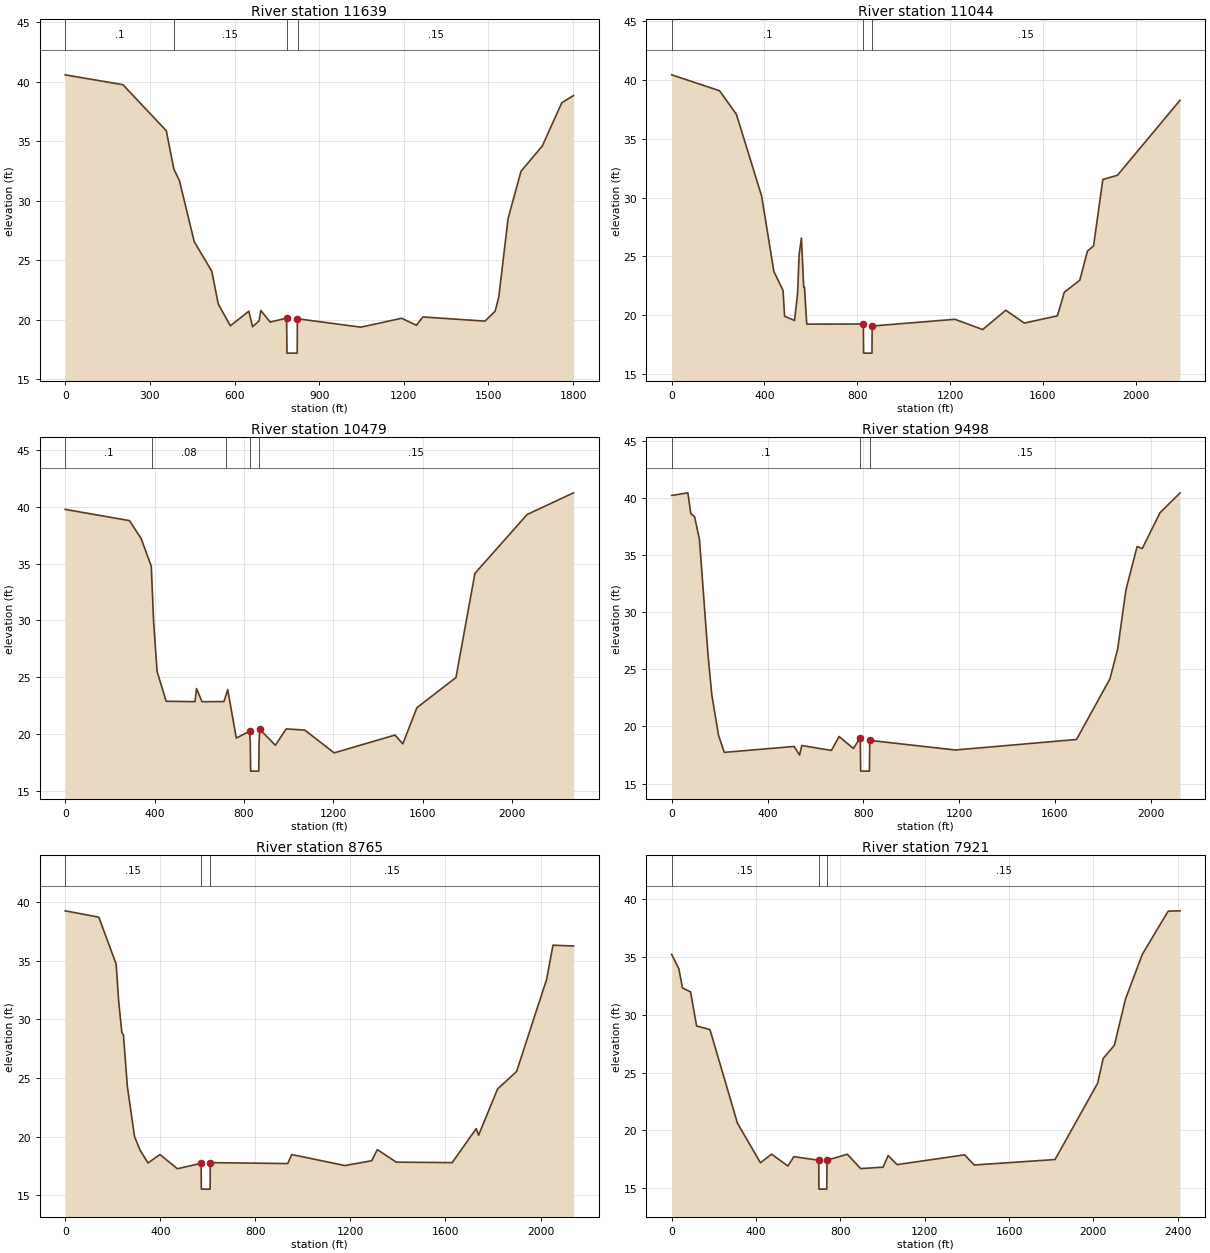
Type RM Length L Ch R = 1 ,11639   ,595,595,595
BEGIN DESCRIPTION:
Maple Swamp 13.0
END DESCRIPTION:
XS GIS Cut Line= 3
      2606111.14       761572.78      2605307.21       761562.06
      2604309.81       761560.65
#Sta/Elev= 30
       0   40.59   204.6   39.76   358.2   35.89     385   32.67   404.7    31.7
   457.2   26.57   519.5   24.08   542.5   21.32   585.2    19.5   650.8   20.72
   663.9   19.41   686.9   19.91   693.4   20.78   726.3   19.81  784.57   20.14
785.8999    17.2822.1001    17.2  822.79   20.09  1047.8   19.38  1192.1   20.13
  1244.6   19.54  1267.6   20.24  1487.4   19.89  1523.5   20.72  1536.6   21.93
  1569.4   28.51  1615.4   32.49  1690.8   34.61  1759.7   38.24  1801.4   38.85
#Mann= 4 ,-1,0
       0      .1       0     385     .15       0784.6001    .052       0
823.3999     .15       0
Bank Sta=784.57,822.79
XS Rating Curve= 0 ,0
Exp/Cntr=0.3,0.1

Type RM Length L Ch R = 1 ,11044   ,564.8,564.8,564.8
BEGIN DESCRIPTION:
Maple Swamp 12.0
END DESCRIPTION:
XS GIS Cut Line= 3
      2606220.38       760887.39      2605379.14       760972.13
      2604048.95       761178.53
#Sta/Elev= 30
       0   40.41   206.5   39.06   279.1   37.06   387.9   30.12   440.7   23.72
   480.2   22.12   486.8   19.93   529.7   19.57   542.9   21.85   549.5   25.16
   559.4   26.56   569.3   22.38   572.6   22.38   582.5   19.26  826.45   19.27
827.3999    16.8863.6001    16.8  864.43    19.1  1221.4   19.67    1341    18.8
  1440.6   20.44  1520.2   19.35    1663   19.96  1692.9   21.97  1759.5   22.98
  1792.5   25.45    1819    25.9  1858.9   31.53    1922   31.89  2191.6   38.25
#Mann= 3 ,0,0
       0      .1       0  826.45     .05       0  864.43     .15       0
Bank Sta=826.45,864.43
XS Rating Curve= 0 ,0
Exp/Cntr=0.3,0.1

Type RM Length L Ch R = 1 ,10479   ,981.1,981.1,981.1
BEGIN DESCRIPTION:
Maple Swamp 11.0
END DESCRIPTION:
XS GIS Cut Line= 3
      2605989.85       760156.52      2605192.76        760447.1
      2603854.91       760944.99
#Sta/Elev= 30
       0   39.79   287.7    38.8     340   37.22   385.4   34.78   395.9   29.86
   411.4   25.51   451.8   22.88     581   22.84     588      24   612.4   22.84
   710.8   22.85   727.7    23.9   766.1   19.63   825.4   20.24828.7998   19.22
830.1001   16.72866.6997   16.72     868   19.22   870.9   20.41   940.9      19
   989.3   20.44  1072.5   20.34  1204.2   18.33  1476.6    19.9  1511.5   19.12
  1574.5   22.31  1749.5   24.97  1834.4   34.15  2068.1   39.34  2275.9   41.25
#Mann= 5 ,-1,0
       0      .1       0388.3999     .08       0718.3999     .13       0
828.7998    .052       0     868     .15       0
Bank Sta=825.4,870.9
XS Rating Curve= 0 ,0
Exp/Cntr=0.3,0.1

Type RM Length L Ch R = 1 ,9498    ,733.3,733.3,733.3
BEGIN DESCRIPTION:
Maple Swamp 10.0
END DESCRIPTION:
XS GIS Cut Line= 3
      2605322.69       759167.85      2604659.46       759627.79
       2603794.2       760617.49
#Sta/Elev= 30
       0   40.21    67.6   40.44    79.9   38.63    95.9   38.34   115.9   36.36
   151.8   26.24   167.8   22.72   195.7   19.22   219.7   17.73   510.9   18.25
   533.9    17.5   543.1   18.33   666.8    17.9   698.8   19.12   758.6   18.07
   786.6      19   787.5   18.59788.8003   16.09825.3999   16.09826.7002   18.59
   826.9   18.78  1184.3   17.94  1689.8   18.86  1829.2   24.16  1861.4   26.76
  1896.2   31.96  1942.7   35.74  1964.3   35.57  2038.4    38.7  2121.7   40.43
#Mann= 3 ,-1,0
       0      .1       0   787.5     .05       0826.7002     .15       0
Bank Sta=786.6,826.9
XS Rating Curve= 0 ,0
Exp/Cntr=0.3,0.1

Type RM Length L Ch R = 1 ,8765    ,843.9,843.9,843.9
BEGIN DESCRIPTION:
Maple Swamp 9.0
END DESCRIPTION:
XS GIS Cut Line= 3
      2605235.11       759046.19      2604153.55       758839.16
       2603131.1       758661.87
#Sta/Elev= 30
       0   39.25  141.39   38.71  214.51    34.7   224.9   31.56  238.27   28.88
  244.95   28.66  261.65   24.26  291.71      20   315.1   18.84   348.5   17.75
  398.61   18.47  472.09   17.26  571.94   17.72   572.7   15.52   609.7   15.52
  610.54   17.78  936.41    17.7  953.11   18.47 1176.68   17.53 1289.89   17.94
  1313.3   18.89 1393.12   17.82 1628.29   17.78 1729.43   20.68 1739.42   20.12
 1819.33   24.06 1899.25   25.55 2025.78   33.41 2052.42   36.32  2138.9   36.25
#Mann= 3 ,-1,0
       0     .15       0  571.94     .05       0  610.54     .15       0
Bank Sta=571.94,610.54
XS Rating Curve= 0 ,0
Exp/Cntr=0.3,0.1

Type RM Length L Ch R = 1 ,7921    ,1107.5,1107.5,1107.5
BEGIN DESCRIPTION:
Maple Swamp 8.0
END DESCRIPTION:
XS GIS Cut Line= 3
      2605537.84       758379.27       2604163.1       757844.74
      2603235.94       757719.37
#Sta/Elev= 30
       0   35.23    33.8      34    51.4   32.32   89.64   31.98  118.28   29.03
  181.64   28.72  311.88   20.62  421.01   17.19  473.81   17.94  551.28   16.91
  579.41   17.72   697.3   17.41   698.5   14.91   735.5   14.91   736.7   17.41
  832.86   17.93  896.22   16.69 1002.44   16.81 1026.47   17.82 1068.71   17.03
 1389.04   17.88  1434.8      17 1817.92   17.47 2019.88   24.07 2046.36   26.22
 2099.33   27.36  2152.3   31.37 2231.76   35.23 2354.45   38.97  2410.6      39
#Mann= 3 ,-1,0
       0     .15       0   697.3     .05       0   736.7     .15       0
Bank Sta=697.3,736.7
XS Rating Curve= 0 ,0
Exp/Cntr=0.3,0.1