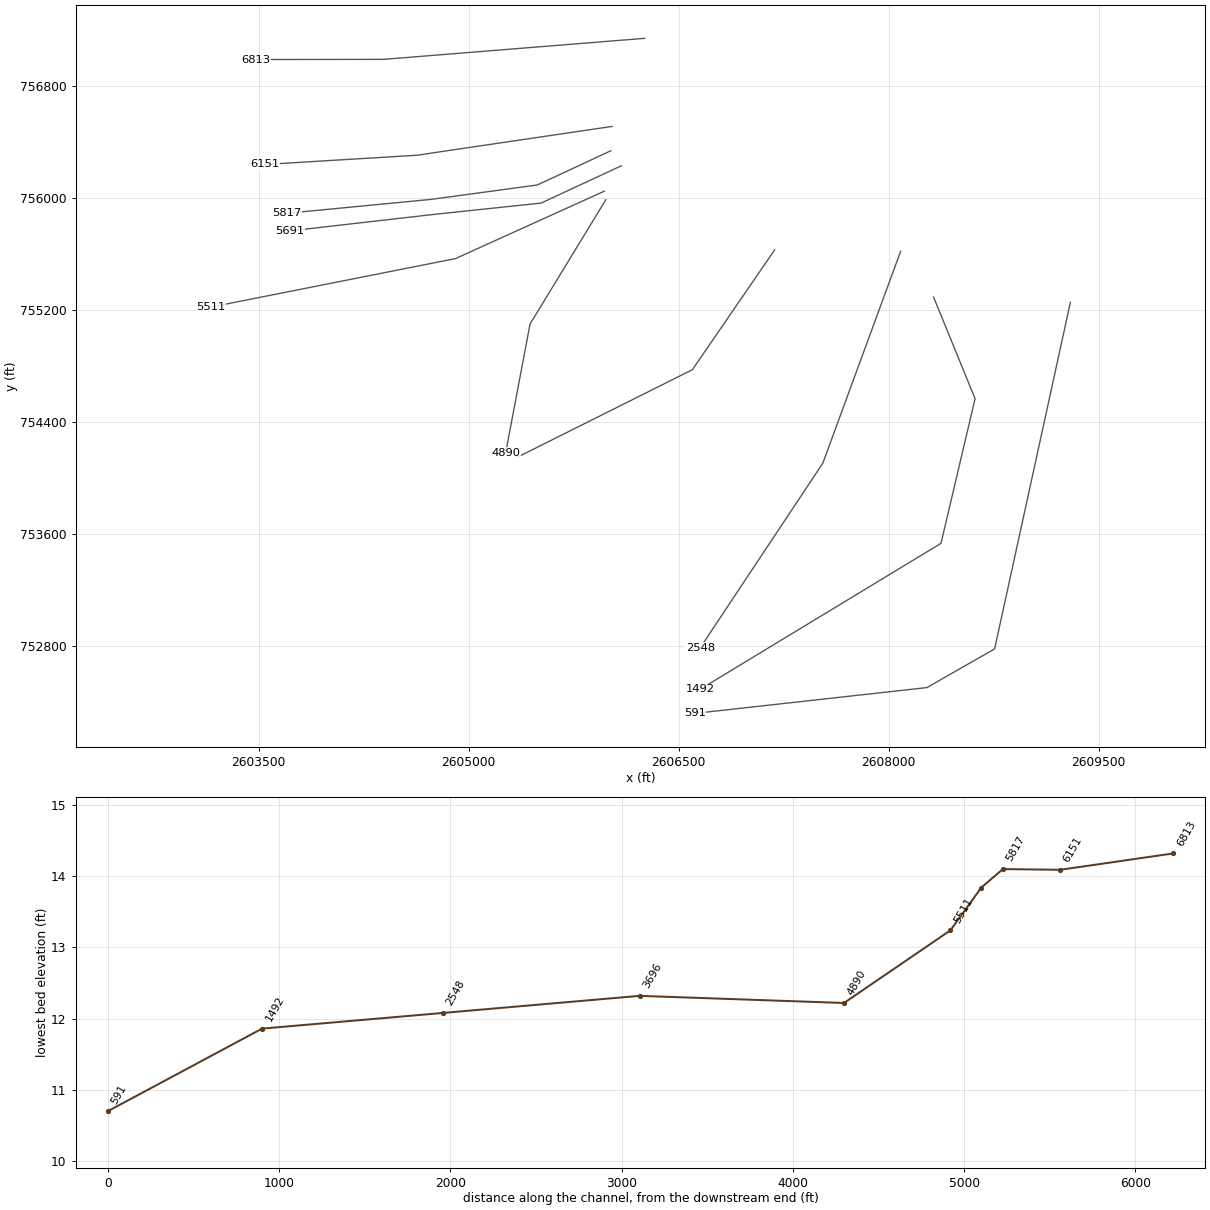
HEC-RAS study MapleSwamp.prj: S-26-65 over Maple Swamp

--- MapleSwamp.g04 (geometry) --- (continued)

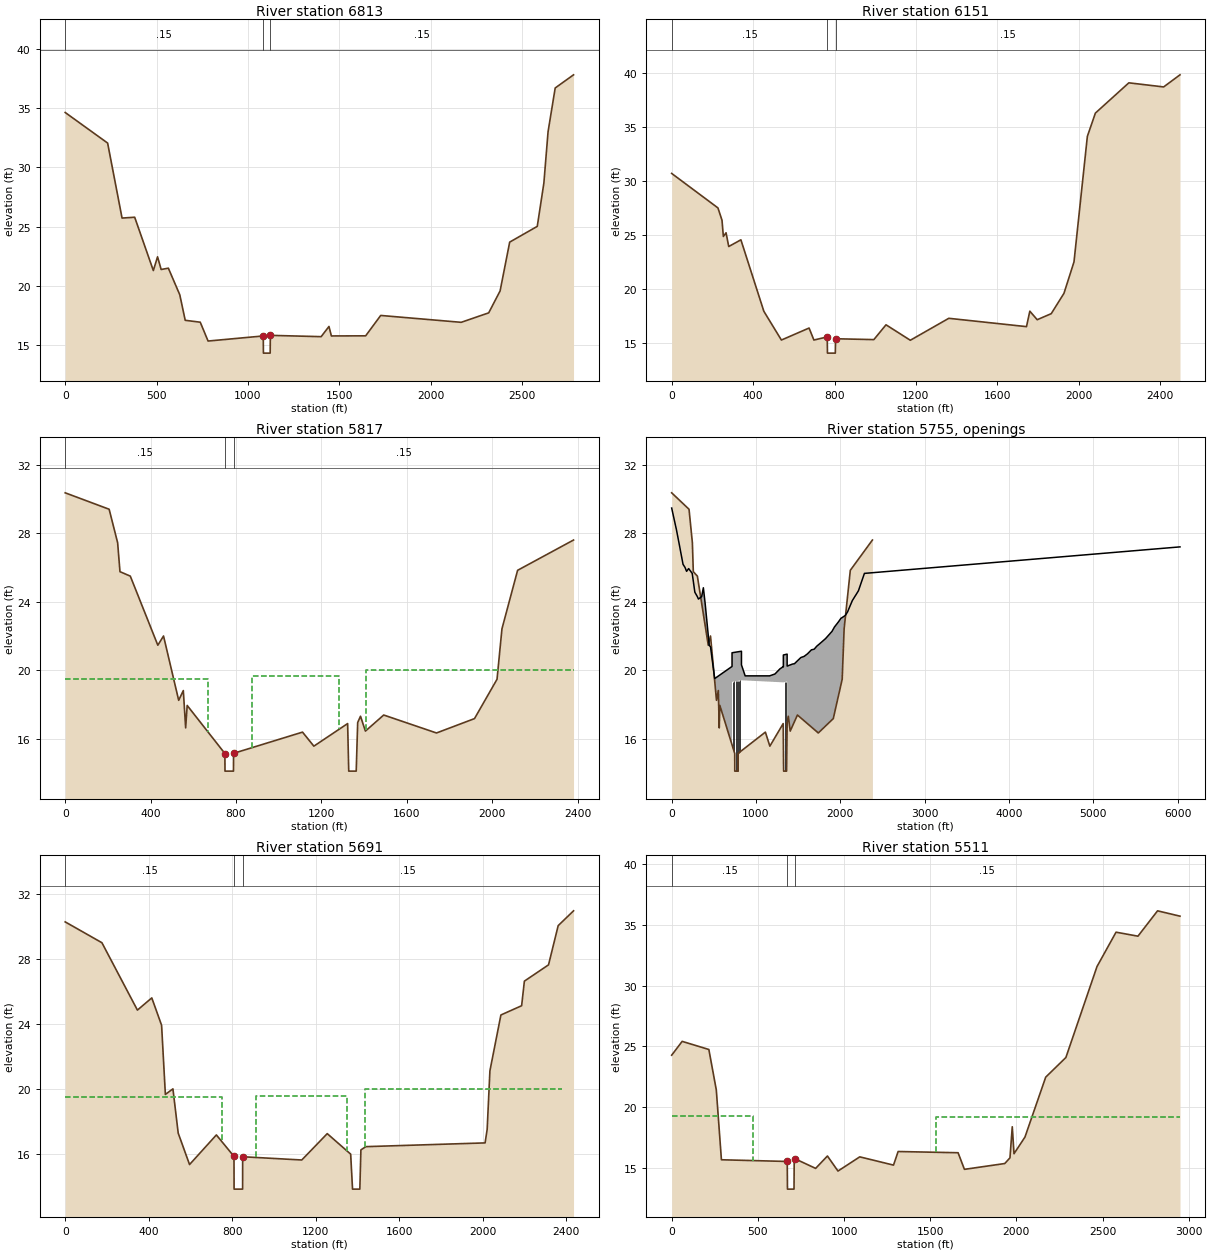
Type RM Length L Ch R = 1 ,6813    ,662,662,662
BEGIN DESCRIPTION:
Maple Swamp 7.0
END DESCRIPTION:
XS GIS Cut Line= 3
      2606256.07       757139.43      2604391.01       756989.26
      2603480.51       756988.03
#Sta/Elev= 30
       0   34.63   232.1   32.05   311.1   25.72  380.22   25.79  482.26   21.29
   505.3   22.45  525.04   21.38  564.54   21.49  627.08   19.24   656.7   17.09
  738.99   16.93  781.78   15.34 1083.83   15.77  1084.6   14.32  1121.6   14.32
 1122.64   15.82 1400.57   15.71 1443.36   16.57 1456.53   15.77 1644.14   15.78
 1726.43    17.5 2166.87   16.92 2317.44   17.72 2379.78   19.57 2432.27   23.69
 2583.19   25.02 2619.28   28.67 2642.25   33.01 2681.27    36.7  2781.6   37.81
#Mann= 3 ,-1,0
       0     .15       0 1083.83     .05       0 1122.64     .15       0
Bank Sta=1083.83,1122.64
XS Rating Curve= 0 ,0
Exp/Cntr=0.3,0.1

Type RM Length L Ch R = 1 ,6151    ,334.1,334.1,334.1
XS GIS Cut Line= 6
2606023.27567147756510.1735210862604834.47600654756334.871384243
2604637.37371215756305.2100602962604627.57540168756304.216163674
2604153.89617531 756275.640474692603542.84476962756238.518487706
#Sta/Elev= 30
       0   30.71   227.4   27.52   247.3   26.38   253.9   24.88   267.2   25.22
   280.4   23.95   340.1   24.57   452.9   17.96   539.1    15.3   675.1   16.41
   698.8    15.3  764.32   15.59  765.37   14.09  803.97   14.09  805.19   15.42
   993.4   15.34  1053.1   16.71  1172.5   15.28  1361.6   17.31  1743.3   16.54
  1759.7   17.97  1795.9   17.18  1864.9   17.74  1927.4   19.62  1976.7   22.53
  2042.4   34.14  2081.8   36.29  2246.2   39.09  2417.1   38.71  2497.5   39.83
#Mann= 3 ,0,0
       0     .15       0  764.32     .05       0  805.19     .15       0
Bank Sta=764.32,805.19
XS Rating Curve= 0 ,0
Exp/Cntr(USF)=0,0
Exp/Cntr=0.5,0.3

Type RM Length L Ch R = 1 ,5817    ,125.9,125.9,125.9
BEGIN DESCRIPTION:
Maple Swamp (Co Jo Rd) US
END DESCRIPTION:
XS GIS Cut Line= 4
2606014.47930916756336.3196717752605489.55930916756092.069671775
2604730.09930916755988.9496717752603699.54930916755889.799671775
#Sta/Elev= 30
       0   30.37   205.8   29.41   245.6   27.45   256.5   25.76   304.9    25.5
   433.8   21.46   460.5      22   531.5   18.24   553.2   18.81   564.1   16.63
   571.3   17.94  747.89   15.13  748.38    14.1  788.01    14.1  788.52   15.14
  1111.4   16.38  1164.6   15.56  1322.7   16.88  1327.9    14.1  1362.9    14.1
  1369.8   16.94    1383   17.31    1406   16.44  1491.7   17.38  1738.9   16.33
  1916.9   17.17  2022.4   19.47  2045.5   22.42  2118.8   25.84  2380.7   27.61
#Mann= 3 ,0,0
       0     .15       0  747.89     .05       0  788.52     .15       0
#XS Ineff= 3 ,-1
       0  668.65   19.51  875.05 1284.55   19.67 1409.55  2380.7      20
Permanent Ineff=
       F       F       F
Bank Sta=747.89,788.52
XS Rating Curve= 0 ,0
Exp/Cntr=0.5,0.3

Type RM Length L Ch R = 4 ,5755    ,,,
BEGIN DESCRIPTION:
Maple Swamp (Co Jo Rd) TOR
Structure ID: Maple Swamp_CJR
Approximate Survey Structure. The top of bridge is curb
END DESCRIPTION:
Bridge Culvert--1,0,-1,-1, 0
Deck Dist Width WeirC Skew NumUp NumDn MinLoCord MaxHiCord MaxSubmerge Is_Ogee
47.23342,28.5,3,0, 50, 50, , , 0.95, 0, 2,2,,
       0    56.2    89.9   134.7   158.1   176.7   201.4   243.7   274.8   304.7
   317.4   355.4   375.9   396.5   445.9   460.3   510.1  715.85  715.85  827.85
  827.85   871.5    1162  1225.1  1284.3  1317.3 1324.55 1324.55 1369.55 1369.55
  1432.8  1455.9  1531.8  1571.4    1611  1657.2  1690.1  1719.8  1772.4  1825.4
  1901.3    1931  1977.1  2006.8  2059.6    2086  2142.6  2214.7  2285.9  6028.9
   29.48   28.22   27.36   26.19   26.01   25.78   25.94   25.66   24.56    24.3
   24.16    24.3   24.82   23.93   21.44   21.38   19.51   20.22   21.02   21.11
   20.31   19.67   19.67   19.78   20.08   20.19   20.19   20.89   20.94   20.24
   20.36   20.38   20.74   20.81   20.96   21.19   21.23    21.4   21.62   21.85
   22.27   22.53   22.82   23.03    23.2   23.41   24.07   24.64   25.66   27.21
                                                                                
                                                                   19.32   19.41
                                                           19.29   19.34
                                                                                
                                                                                
       0    91.2   139.7   184.2   212.9   232.3     254   290.7   329.9     357
   376.2   420.5   442.2   487.9   503.7   555.2   586.3   777.6   777.6   889.6
   889.6   928.1    1209  1250.9  1301.5  1351.1 1370.95 1370.95 1415.95 1415.95
  1467.1    1493    1559  1618.4    1658  1714.1  1737.1  1766.8  1816.3  1855.9
  1918.6  1964.8  2007.8  2040.6  2076.2  2116.5  2172.6  2238.6    2321  2423.3
   29.48   28.22   27.14   26.23   25.84   25.58   25.63   25.66   24.94   24.04
   24.73   24.78   23.96   21.33   21.56   19.51   19.51   20.22   21.02   21.11
   20.31   19.67   19.67   19.58   19.81   20.16   20.19   20.89   20.94   20.24
   20.37   20.46   20.69   20.81   20.96   21.06   21.23    21.4   21.66   21.91
   22.03   22.45   22.78   22.94   22.92   23.31   23.79    24.5   25.53   26.96
                                                                                
                                                                   19.32   19.41
                                                           19.29   19.34
                                                                                
                                                                                
Pier Skew, UpSta & Num, DnSta & Num=  ,729.85, 2 ,791.6, 2 , 0 , 0 , 0 ,,
       1       1
       0      20
       1       1
       0      20
Pier Skew, UpSta & Num, DnSta & Num=  ,743.85, 2 ,805.6, 2 , 0 , 0 , 0 ,,
       1       1
       0      20
       1       1
       0      20
Pier Skew, UpSta & Num, DnSta & Num=  ,757.85, 2 ,819.6, 2 , 0 , 0 , 0 ,,
       1       1
       0      20
       1       1
       0      20
Pier Skew, UpSta & Num, DnSta & Num=  ,771.85, 2 ,833.6, 2 , 0 , 0 , 0 ,,
       1       1
       0      20
       1       1
       0      20
Pier Skew, UpSta & Num, DnSta & Num=  ,785.85, 2 ,847.6, 2 , 0 , 0 , 0 ,,
       1       1
       0      20
       1       1
       0      20
Pier Skew, UpSta & Num, DnSta & Num=  ,799.85, 2 ,861.6, 2 , 0 , 0 , 0 ,,
       1       1
       0      20
       1       1
       0      20
Pier Skew, UpSta & Num, DnSta & Num=  ,813.85, 2 ,875.6, 2 , 0 , 0 , 0 ,,
       1       1
       0      20
       1       1
       0      20
Pier Skew, UpSta & Num, DnSta & Num=  ,1339.55, 2 ,1385.95, 2 , 0 , 0 , 0 ,,
       1       1
       0    28.2
       1       1
       0    28.2
Pier Skew, UpSta & Num, DnSta & Num=  ,1354.55, 2 ,1400.95, 2 , 0 , 0 , 0 ,,
       1       1
       0    28.2
       1       1
       0    28.2
Abutment Skew #Up #Dn= , 2 , 2
  715.85  721.85
   19.32   16.32
   777.6   783.6
   19.32   16.32
Abutment Skew #Up #Dn= , 2 , 2
  821.85  827.85
   16.41   19.41
   883.6   889.6
   16.41   19.41
Abutment Skew #Up #Dn= , 2 , 2
 1324.55 1330.55
   19.29   16.29
 1370.95 1376.95
   19.29   16.29
Abutment Skew #Up #Dn= , 2 , 2
 1363.55 1369.55
   16.34   19.34
 1409.95 1415.95
   16.34   19.34
BR Coef=-1 ,-1 ,-1 ,0.9, 0 ,,,0.8,0,1.2,0,
WSPro=,,,, 1 ,,,, 0 ,,,, 0 ,,,,-1 ,-1 ,-1 , 0 , 0 , 0 , 0 , 0
BC Mult= 3 ,0,1083.7,0,1130.28
BC Mult= 3 ,1083.7,4000,1130.28,4000
BC Design=,, 0 ,, 0 ,,,,,,
BC HTab HWMax=30.34
BC Use User HTab Curves=0
BC User HTab FreeFlow(D)= 0

Type RM Length L Ch R = 1 ,5691    ,180.1,180.1,180.1
BEGIN DESCRIPTION:
Maple Swamp (Co Jo Rd) DS
END DESCRIPTION:
XS GIS Cut Line= 4
2606089.06714504756228.8342747832605516.53714504755962.704274783
2604758.30714504755882.7142747832603723.95714504755764.294274783
#Sta/Elev= 30
       0   30.26   175.9   28.98   345.9   24.84   414.7   25.59   461.7   23.91
   479.8   19.66     516      20   541.3   17.28   595.6   15.35   724.1   17.17
  808.46   15.85  808.93   13.84  849.77   13.84  850.04   15.83  1133.2   15.63
  1255.2   17.25  1367.4   15.99  1376.3   13.84  1411.3   13.84  1416.4   16.25
    1440   16.45  2011.3   16.68  2021.2   17.51  2034.4   21.11    2087   24.54
  2186.3   25.11  2199.5   26.62  2315.1   27.62  2361.4   30.03  2434.9   30.94
#Mann= 3 ,0,0
       0     .15       0  808.46     .05       0  850.04     .15       0
#XS Ineff= 3 ,-1
       0   752.5   19.51   914.7 1349.25   19.58 1437.55  2380.7      20
Permanent Ineff=
       F       F       F
Bank Sta=808.46,850.04
XS Rating Curve= 0 ,0
Exp/Cntr=0.5,0.3

Type RM Length L Ch R = 1 ,5511    ,621.4,621.4,621.4
BEGIN DESCRIPTION:
Maple Swamp 5.0
END DESCRIPTION:
XS GIS Cut Line= 3
      2605968.59       756047.89      2604904.81       755566.09
      2603157.48       755219.89
#Sta/Elev= 30
       0   24.28   60.84   25.42  215.72   24.75  258.93   21.42  288.64   15.66
  670.35   15.52   671.8   13.24   709.8   13.24  710.77   15.42  712.74   15.76
   835.2   14.95  903.63   15.97  964.86   14.73  1091.2    15.9 1287.05   15.22
  1313.8   16.34 1661.64   16.24 1698.43   14.87 1932.56   15.35 1962.66   15.82
 1976.04   18.38 1986.07   16.16 2049.62   17.53 2170.03   22.47 2287.09   24.09
  2467.7   31.59 2578.07   34.42 2705.16   34.09 2818.88   36.18  2949.1   35.74
#Mann= 3 ,-1,0
       0     .15       0  670.35     .05       0  712.74     .15       0
#XS Ineff= 2 , 0
           470.3   19.24  1531.3           19.19
Permanent Ineff=
       F       F
Bank Sta=670.35,712.74
XS Rating Curve= 0 ,0
Exp/Cntr=0.5,0.3

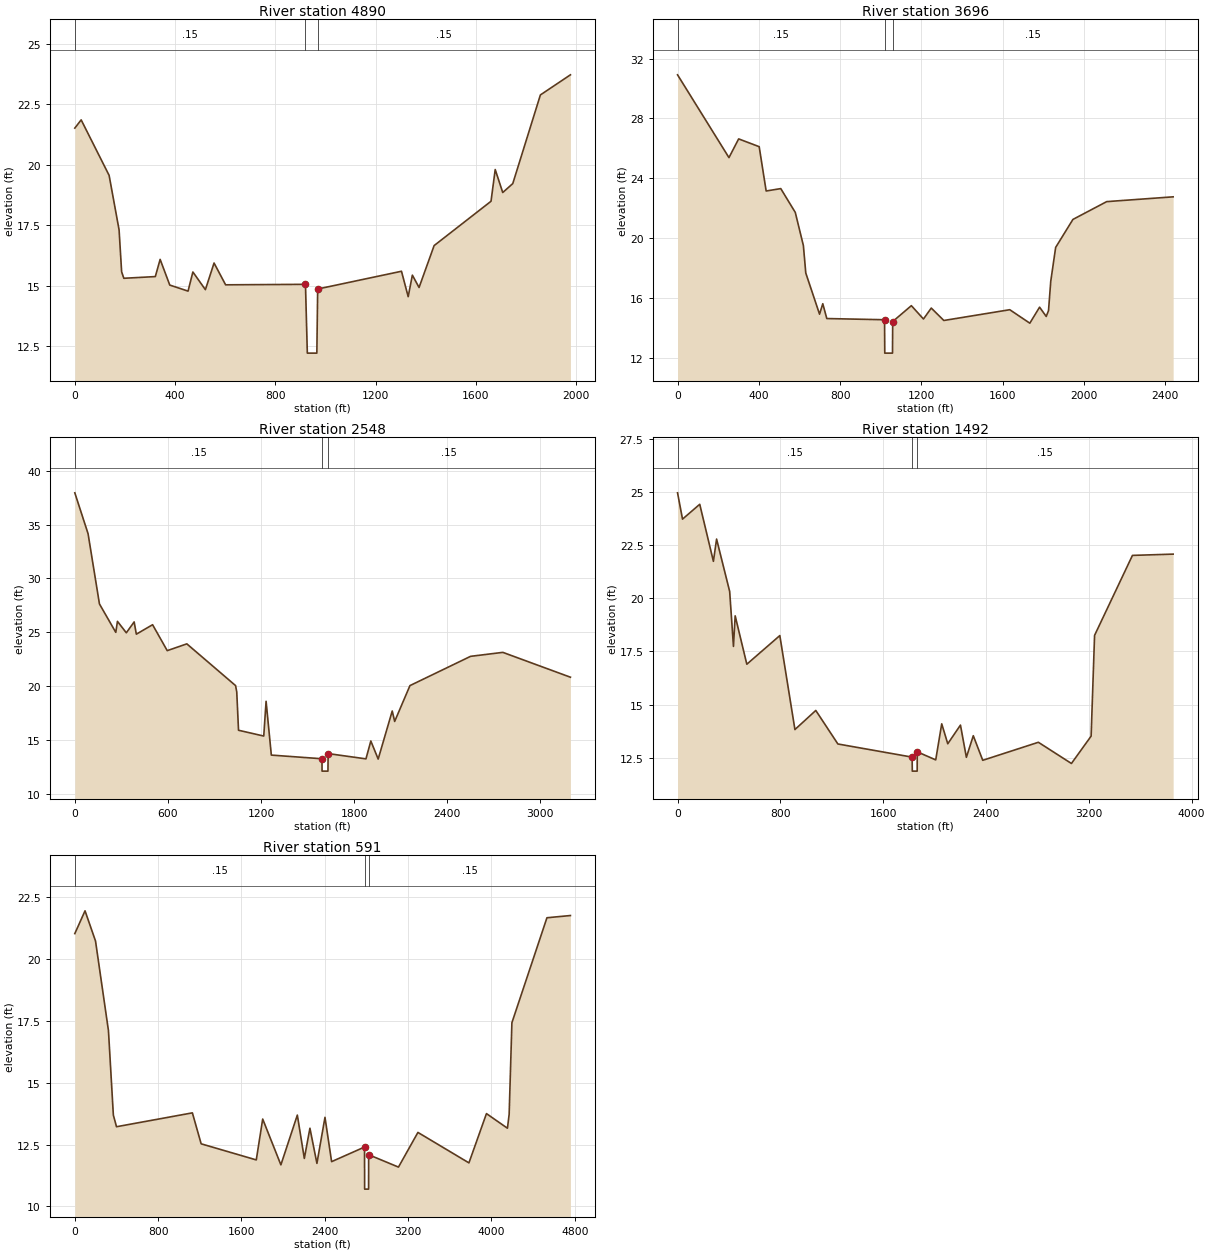
Type RM Length L Ch R = 1 ,4890    ,1193.5,1193.5,1193.5
BEGIN DESCRIPTION:
Maple Swamp 4.0
END DESCRIPTION:
XS GIS Cut Line= 3
      2605978.84       755986.58      2605437.48       755098.47
      2605263.27        754177.2
#Sta/Elev= 30
       0   21.51   25.32   21.85  136.82   19.56  176.61   17.31  186.77   15.58
  195.52   15.31  321.26   15.38  340.47   16.09  378.89   15.03  451.89   14.78
  471.11   15.57  521.06   14.84  555.64   15.94  601.74   15.04  920.41   15.06
   927.8   12.22   965.8   12.22     969   14.78  970.61   14.87 1303.59    15.6
  1330.3   14.55    1347   15.44 1373.71   14.93 1433.81   16.66 1660.86   18.49
 1677.56    19.8 1707.61   18.85 1747.68   19.22 1857.86   22.88  1977.7   23.71
#Mann= 3 ,-1,0
       0     .15       0  920.41     .05       0  970.61     .15       0
Bank Sta=920.41,970.61
XS Rating Curve= 0 ,0
Exp/Cntr=0.3,0.1

Type RM Length L Ch R = 1 ,3696    ,1148.8,1148.8,1148.8
BEGIN DESCRIPTION:
Maple Swamp 3.0
END DESCRIPTION:
XS GIS Cut Line= 3
      2607185.09       755628.79      2606597.15       754772.63
      2605345.06       754146.53
#Sta/Elev= 30
       0   30.91     253   25.38   300.7   26.63   401.7   26.11     436   23.15
   507.9   23.31   579.3   21.72   619.1   19.51     631   17.67   698.7   14.92
   714.6   15.62   734.4   14.63 1018.49   14.55  1019.6   12.32  1057.6   12.32
 1058.64   14.43  1150.4   15.49    1210    14.6  1248.4   15.33  1310.2    14.5
  1634.6   15.22  1733.3   14.32  1781.3   15.39    1814   14.77  1825.3   15.16
  1836.3   17.12  1860.4   19.38  1945.3   21.25  2111.5   22.44  2438.5   22.76
#Mann= 3 ,0,0
       0     .15       0 1018.49     .05       0 1058.64     .15       0
Bank Sta=1018.49,1058.64
XS Rating Curve= 0 ,0
Exp/Cntr=0.3,0.1

Type RM Length L Ch R = 1 ,2548    ,1055.7,1055.7,1055.7
BEGIN DESCRIPTION:
Maple Swamp 2.0
END DESCRIPTION:
XS GIS Cut Line= 3
      2608084.66       755618.55      2607528.73        754104.7
      2606653.54       752786.96
#Sta/Elev= 30
       0   37.95    85.4   34.15   158.8   27.62   264.1   24.98   274.8      26
   331.9   24.94   382.5   25.95   396.5   24.81   501.3   25.69   595.7   23.28
   722.1   23.91  1036.2   20.03  1043.8   19.44  1055.2   15.88  1217.8   15.34
  1232.9   18.57  1266.7   13.57 1593.11   13.23  1593.7   12.08  1631.7   12.08
 1632.71   13.71  1876.6   13.22  1908.1   14.88  1955.4    13.2    2046   17.67
  2061.7    16.7  2160.2   20.03  2550.9   22.75  2758.9   23.12  3194.6   20.81
#Mann= 3 ,0,0
       0     .15       0 1593.11     .05       0 1632.71     .15       0
Bank Sta=1593.11,1632.71
XS Rating Curve= 0 ,0
Exp/Cntr=0.3,0.1

Type RM Length L Ch R = 1 ,1492    ,900.9,900.9,900.9
BEGIN DESCRIPTION:
Maple Swamp 1.0
END DESCRIPTION:
XS GIS Cut Line= 4
      2608319.78       755291.44      2608616.23       754565.64
      2608372.92       753532.42      2606653.49       752490.46
#Sta/Elev= 30
       0   24.98    38.7   23.74   172.7   24.44     279   21.75   303.8    22.8
   405.6   20.33     435   17.74   448.4   19.18     539    16.9   795.8   18.25
   913.3   13.82  1075.6   14.72  1247.5   13.14 1825.03   12.52  1826.5   11.86
  1864.5   11.86 1864.95   12.77  2008.7   12.39  2055.5   14.09  2102.4   13.15
  2201.2   14.03  2247.3   12.51    2301   13.53  2374.6   12.37  2807.4   13.22
  3064.6   12.22  3217.8   13.51  3244.7   18.26  3539.4   22.03    3856   22.09
#Mann= 3 ,0,0
       0     .15       0 1825.03     .05       0 1864.95     .15       0
Bank Sta=1825.03,1864.95
XS Rating Curve= 0 ,0
Exp/Cntr=0.3,0.1

Type RM Length L Ch R = 1 ,591     ,0,0,0
BEGIN DESCRIPTION:
Maple Swamp 0.5
END DESCRIPTION:
XS GIS Cut Line= 4
      2609297.06       755253.57      2608755.97       752778.34
      2608272.43       752502.03      2606614.53       752317.82
#Sta/Elev= 30
       0   21.02      98   21.94   198.8   20.72     323    17.1     370   13.69
   400.3   13.22  1128.8   13.78    1213   12.53  1742.3   11.88    1804   13.53
  1978.7   11.68  2136.5   13.69  2203.7   11.94  2257.4   13.16  2324.6   11.74
    2402    13.6  2465.6   11.81 2781.76    12.4  2782.7    10.7  2820.7    10.7
 2821.36   12.09  3107.6   11.59  3294.5   12.99  3784.2   11.76  3952.5   13.75
  4153.9   13.16  4170.4   13.72  4196.8   17.42  4533.3   21.66  4758.7   21.75
#Mann= 3 ,0,0
       0     .15       0 2781.76     .05       0 2821.36     .15       0
Bank Sta=2781.76,2821.36
XS Rating Curve= 0 ,0
Exp/Cntr=0.3,0.1
LCMann Table=0

Chan Stop Cuts=-1
Use User Specified Reach Order=0
Composite Channel Slope=5

--- MapleSwamp.g01 (geometry) ---

Geom Title=Duplicate Effective
Program Version=6.60

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
River Reach=Maple Swamp     ,Reach-1
Reach XY= 30
      2599537.86       777539.22      2600191.34       777563.86
      2601509.94       777021.38       2603516.3       777838.93
      2604284.17         777797.      2604939.52       777305.48
      2605392.23       777788.37      2606375.26       777827.18
      2607147.02       777474.06      2607845.55       776592.54
      2607789.75       775192.58      2608234.95       774272.83
      2608298.55       773649.78      2608098.52       772654.84
      2607752.86       771946.89      2607911.72       771559.59
      2607753.19       770823.93      2608769.52       770113.49
      2609093.13       768070.89      2608369.51       766441.66
      2605027.77       763868.03      2605364.15       760822.12
      2604191.53       758997.42      2604095.39       758343.69
      2604358.17       757075.95      2604982.63       755432.16
      2605301.02       755144.99      2606487.15       754845.34
      2608232.84       753765.46      2608584.43       752057.63

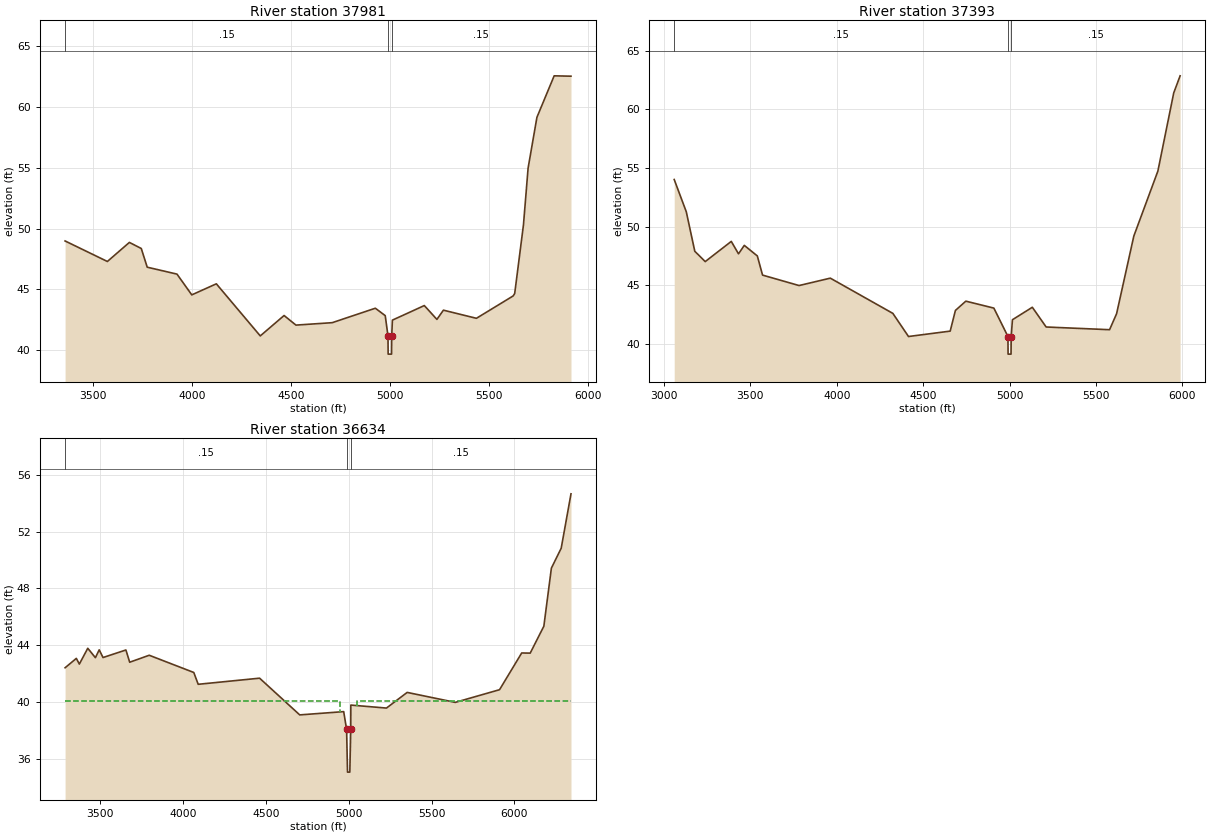
Type RM Length L Ch R = 1 ,37981   ,588,588,588
BEGIN DESCRIPTION:
Maple Swamp 60.0
END DESCRIPTION:
XS GIS Cut Line= 3
      2601231.68        778734.1      2601135.59       777096.71
      2600759.99       776262.47
#Sta/Elev= 30
  3359.8   48.98  3573.4   47.29  3684.5   48.86  3744.6   48.36  3774.6   46.82
  3924.9   46.25  3999.7   44.54  4123.7   45.45  4345.6   41.16  4465.8   42.84
  4525.9   42.05  4708.9   42.25  4926.7   43.44  4976.7   42.83  4990.6   41.16
  4991.4   39.66  5008.6   39.66  5009.4   41.16    5013   42.46  5174.1   43.66
  5237.7   42.52  5270.6   43.28  5437.3   42.61  5622.6   44.45  5630.6   44.65
  5674.8    50.3  5698.3   54.98  5742.8   59.16  5829.9   62.58  5914.9   62.55
#Mann= 3 ,-1,0
  3359.8     .15       0  4990.6     .05       0  5009.4     .15       0
Bank Sta=4990.6,5009.4
XS Rating Curve= 0 ,0
Exp/Cntr=0.3,0.1

Type RM Length L Ch R = 1 ,37393   ,759,759,759
BEGIN DESCRIPTION:
Maple Swamp 59.0
END DESCRIPTION:
XS GIS Cut Line= 3
      2601514.02       778978.47      2601709.72       777048.27
      2601654.32       776063.13
#Sta/Elev= 30
  3059.9   54.02  3129.8   51.27    3179   47.91  3239.3   47.03  3390.1   48.75
  3431.8   47.69  3465.4   48.41  3540.8   47.51    3571   45.88  3782.1   44.99
    3963   45.62  4324.8   42.62  4415.3   40.65  4656.5   41.11  4686.7   42.87
    4747   43.66  4909.2   43.07  4990.6   40.65  4991.4   39.15  5008.6   39.15
  5009.4   40.65  5016.7   42.08  5131.7   43.14  5211.7   41.46  5578.5   41.23
  5619.2   42.59  5718.8    49.2  5858.1   54.74  5949.8    61.4  5986.7   62.85
#Mann= 3 ,-1,0
  3059.9     .15       0  4990.6     .05       0  5009.4     .15       0
Bank Sta=4990.6,5009.4
XS Rating Curve= 0 ,0
Exp/Cntr=0.5,0.3

Type RM Length L Ch R = 1 ,36634   ,129,129,129
BEGIN DESCRIPTION:
Maple Swamp (SCL RR) US
END DESCRIPTION:
XS GIS Cut Line= 3
      2603048.88       778939.54      2602400.43       777356.93
      2601843.97       776137.06
#Sta/Elev= 30
  3289.7   42.43  3357.5   43.09  3375.7   42.69  3426.5    43.8  3472.5   43.14
  3495.5   43.69  3518.5   43.15  3656.5   43.68  3679.4   42.82  3797.1   43.31
  4065.9    42.1  4092.5   41.27  4462.7    41.7  4704.9   39.12    4970   39.35
  4987.5    38.1    4993    35.1    5007    35.1  5012.5    38.1  5013.1   39.81
    5228    39.6  5352.8    40.7  5642.8      40  5909.9   40.89  6043.5   43.47
  6094.8   43.46  6177.1   45.35  6222.6   49.43  6281.8   50.83  6340.8   54.65
#Mann= 3 ,-1,0
  3289.7     .15       0  4987.5     .05       0  5012.5     .15       0
#XS Ineff= 2 , 0
       0    4950    40.1    5050       0    40.1
Permanent Ineff=
       F       F
Bank Sta=4987.5,5012.5
XS Rating Curve= 0 ,0
Exp/Cntr=0.5,0.3