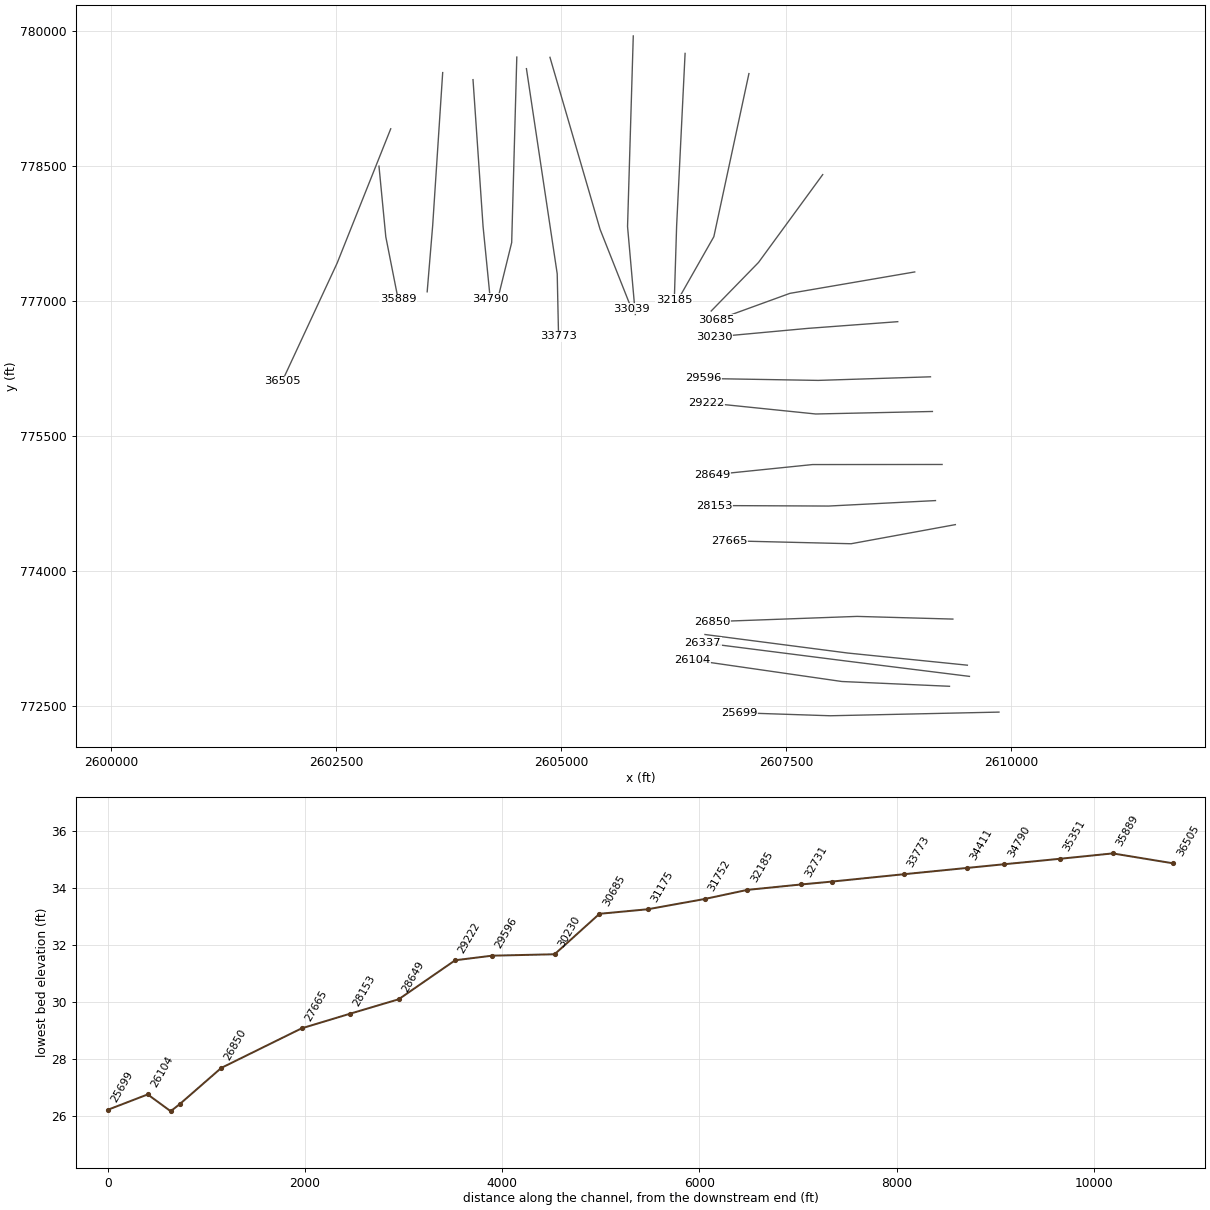
HEC-RAS study MapleSwamp.prj: S-26-65 over Maple Swamp

--- MapleSwamp.g01 (geometry) --- (continued)

Type RM Length L Ch R = 2 ,36571   ,,,
BEGIN DESCRIPTION:
Maple Swamp (SCL RR) TOR
Structure ID: Maple Swamp_RR
Approximate Survey Structure
END DESCRIPTION:
Bridge Culvert--1,0,-1,-1, 0
Deck Dist Width WeirC Skew NumUp NumDn MinLoCord MaxHiCord MaxSubmerge Is_Ogee
38,50,3,0, 60, 60, , , 0.95, 0, 1,1,,
  3339.9  3351.4  3374.5  3397.5  3420.6    3446  3478.3  3510.7    3543  3575.4
  3607.8  3627.9  3668.8  3704.8  3723.1    3742  3845.9  3870.5  3878.6  3912.8
  3970.9  4071.9  4121.4  4141.2  4180.2    4204  4288.3  4331.5  4356.5  4452.6
  4490.6  4513.8  4519.1  4554.6  4631.5  5381.3  5417.3  5452.5  5490.7  5552.9
  5691.1  5784.3  5837.4  5894.1  5965.8  6011.2  6037.4  6072.5  6095.6  6109.1
  6180.7  6195.1  6221.5  6236.3  6279.3  6298.1  6320.6  6356.6  6386.7  6392.7
   42.37   42.35   42.83   42.44   42.58   43.14   43.55    43.3   43.72   43.13
   43.22    43.1   43.76   43.29   42.87   42.71   43.18   42.51   42.43   42.54
   42.16   41.87   41.89   41.24   41.22   41.03   41.35   41.22   41.45   41.85
   41.55   41.18   40.95   40.97    40.5    40.5   40.68   40.26   40.55   40.13
   39.89   40.51   40.46   41.04   41.22   42.01   42.83   43.58   43.78   43.62
   43.65   43.99   45.05    46.8    50.9   51.33      54   53.83   55.79   56.33
   15.03   15.03   15.03   15.03   15.03   15.03   15.03   15.03   15.03   15.03
   15.03   15.03   15.03   15.03   15.03   15.03   15.03   15.03   15.03   15.03
   15.03   15.03   15.03   15.03   15.03   15.03   15.03   15.03   15.03   15.03
   15.03   15.03   15.03   15.03   15.03   15.03   15.03   15.03   15.03   15.03
   15.03   15.03   15.03   15.03   15.03   15.03   15.03   15.03   15.03   15.03
   15.03   15.03   15.03   15.03   15.03   15.03   15.03   15.03   15.03   15.03
  3339.9  3351.4  3374.5  3397.5  3420.6    3446  3478.3  3510.7    3543  3575.4
  3607.8  3627.9  3668.8  3704.8  3723.1    3742  3845.9  3870.5  3878.6  3912.8
  3970.9  4071.9  4121.4  4141.2  4180.2    4204  4288.3  4331.5  4356.5  4452.6
  4490.6  4513.8  4519.1  4554.6  4631.5  5381.3  5417.3  5452.5  5490.7  5552.9
  5691.1  5784.3  5837.4  5894.1  5965.8  6011.2  6037.4  6072.5  6095.6  6109.1
  6180.7  6195.1  6221.5  6236.3  6279.3  6298.1  6320.6  6356.6  6386.7  6392.7
   42.37   42.35   42.83   42.44   42.58   43.14   43.55    43.3   43.72   43.13
   43.22    43.1   43.76   43.29   42.87   42.71   43.18   42.51   42.43   42.54
   42.16   41.87   41.89   41.24   41.22   41.03   41.35   41.22   41.45   41.85
   41.55   41.18   40.95   40.97    40.5    40.5   40.68   40.26   40.55   40.13
   39.89   40.51   40.46   41.04   41.22   42.01   42.83   43.58   43.78   43.62
   43.65   43.99   45.05    46.8    50.9   51.33      54   53.83   55.79   56.33
   14.93   14.93   14.93   14.93   14.93   14.93   14.93   14.93   14.93   14.93
   14.93   14.93   14.93   14.93   14.93   14.93   14.93   14.93   14.93   14.93
   14.93   14.93   14.93   14.93   14.93   14.93   14.93   14.93   14.93   14.93
   14.93   14.93   14.93   14.93   14.93   14.93   14.93   14.93   14.93   14.93
   14.93   14.93   14.93   14.93   14.93   14.93   14.93   14.93   14.93   14.93
   14.93   14.93   14.93   14.93   14.93   14.93   14.93   14.93   14.93   14.93
Culvert=1,5,5,50,0.012,0.2,1,1,3,35.1,4997,34.85,4997,Culvert #1  , 0 ,38
    4997    4997
BC Culvert Barrel=1,,0
Culvert Bottom n=0.012
Culvert=1,5,5,50,0.012,0.2,1,1,3,35.1,5003,34.85,5003,Culvert #2  , 0 ,38
    5003    5003
BC Culvert Barrel=1,,0
Culvert Bottom n=0.012
BC Design=,, 0 ,, 0 ,,,,,,
BC HTab HWMax=54.65
BC Use User HTab Curves=0
BC User HTab FreeFlow(D)= 0

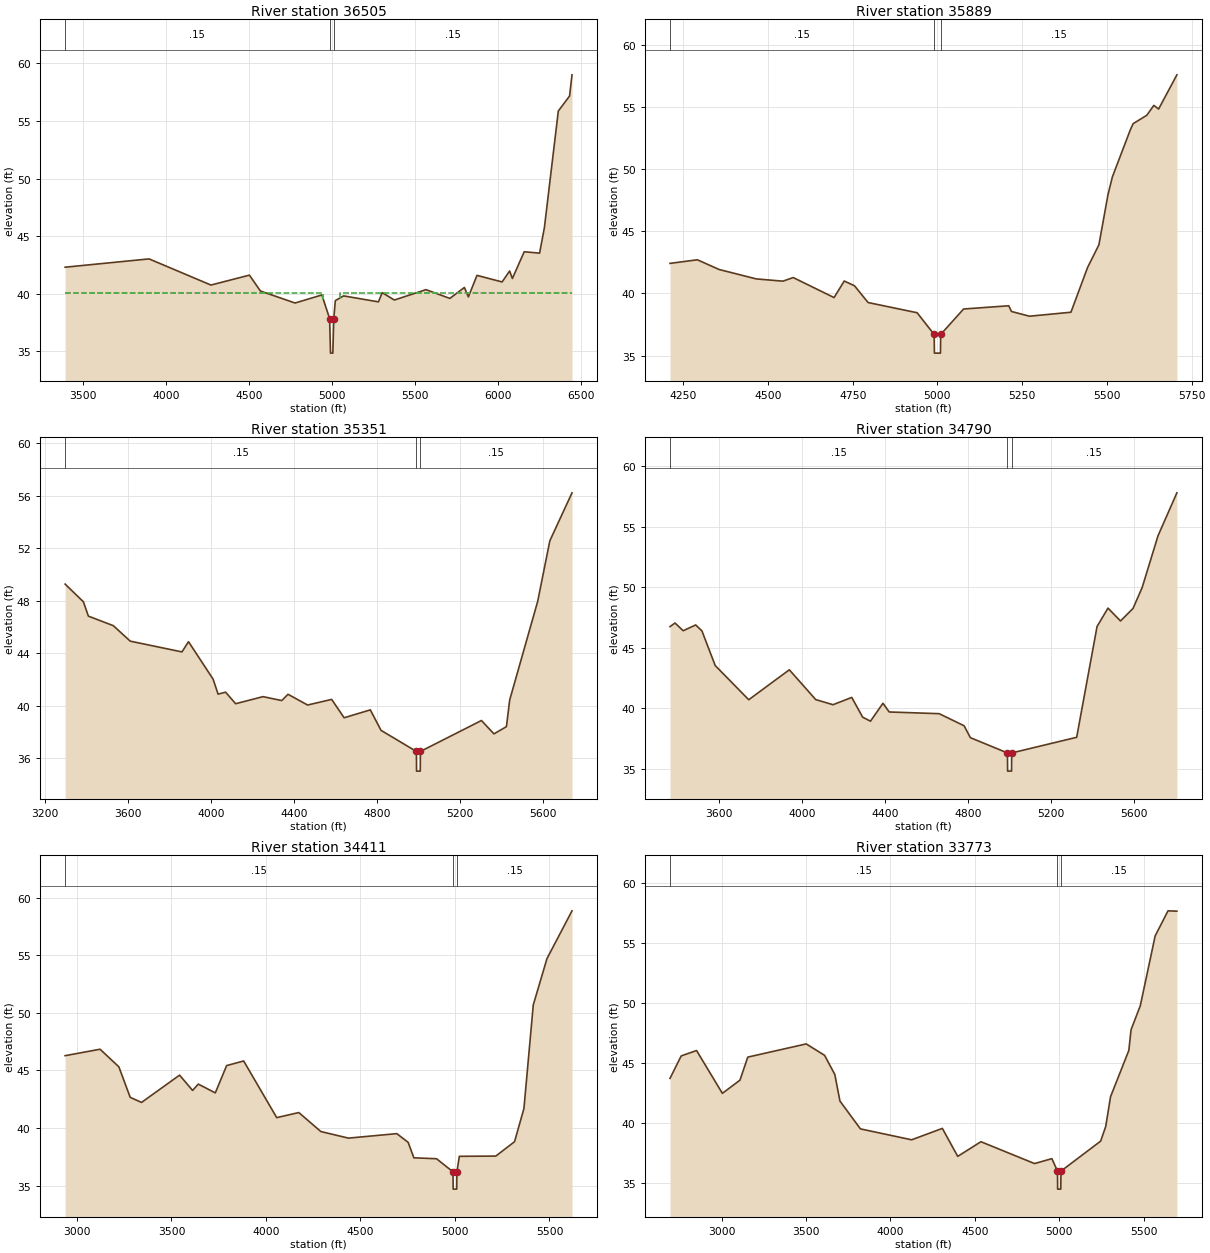
Type RM Length L Ch R = 1 ,36505   ,616,616,616
BEGIN DESCRIPTION:
Maple Swamp (SCL RR) DS
END DESCRIPTION:
XS GIS Cut Line= 3
      2603104.53        778917.1      2602509.29       777425.16
      2601898.47       776111.96
#Sta/Elev= 30
  3393.7   42.31  3899.6   43.03  4272.3   40.76  4504.2   41.62  4570.7   40.24
  4779.5    39.2    4941    39.9  4987.5   37.85    4993   34.85    5007   34.85
  5012.5   37.85    5022   39.41  5071.9   39.82  5281.9    39.3  5304.4    40.1
  5377.7   39.46  5568.2   40.36  5712.1    39.6  5799.8   40.55  5823.8   39.73
  5875.6    41.6  6027.1   41.03  6072.3   41.98    6089   41.33  6160.2   43.65
  6252.9   43.53    6282   45.76  6365.8   55.87  6433.6   57.17  6448.3   59.01
#Mann= 3 ,-1,0
  3393.7     .15       0  4987.5     .05       0  5012.5     .15       0
#XS Ineff= 2 , 0
       0    4950    40.1    5050       0    40.1
Permanent Ineff=
       F       F
Bank Sta=4987.5,5012.5
XS Rating Curve= 0 ,0
Exp/Cntr=0.5,0.3

Type RM Length L Ch R = 1 ,35889   ,538,538,538
BEGIN DESCRIPTION:
Maple Swamp 58.0
END DESCRIPTION:
XS GIS Cut Line= 3
      2602973.88       778501.77       2603049.7       777716.42
      2603186.61       777023.31
#Sta/Elev= 30
    4211   42.42  4291.8   42.71  4355.7   41.93  4465.6   41.17  4544.3   40.99
  4574.5   41.28    4695   39.67  4725.1      41  4755.3   40.62  4795.4   39.27
  4940.1   38.45  4990.4    36.7  4991.1    35.2  5008.9    35.2  5009.6    36.7
  5077.2   38.75  5210.4   39.01  5218.5   38.55  5271.6   38.17  5393.9   38.49
    5443   42.09  5476.5   43.92  5503.2   47.95  5516.2   49.38  5569.2   53.17
  5577.4   53.66  5617.5   54.33  5638.5   55.13  5652.6   54.84  5706.5   57.59
#Mann= 3 ,-1,0
    4211     .15       0  4990.4     .05       0  5009.6     .15       0
Bank Sta=4990.4,5009.6
XS Rating Curve= 0 ,0
Exp/Cntr=0.3,0.1

Type RM Length L Ch R = 1 ,35351   ,561,561,561
BEGIN DESCRIPTION:
Maple Swamp 57.0
END DESCRIPTION:
XS GIS Cut Line= 3
      2603681.94       779541.76      2603570.78        777842.8
      2603509.55       777105.03
#Sta/Elev= 30
  3297.4   49.27  3385.5   47.92  3409.4   46.83  3529.7    46.1  3611.3   44.92
  3860.4    44.1    3892   44.88  4010.7   42.02  4034.5   40.88  4070.8   41.03
  4119.2   40.15  4251.2   40.69  4341.4   40.39  4371.5   40.87    4466   40.05
  4581.9   40.48    4642   39.08  4768.2   39.68  4819.9   38.12  4990.4   36.51
  4991.1   35.01  5008.9   35.01  5009.6   36.51  5303.8   38.87    5364   37.85
  5424.2    38.4  5439.9   40.43  5574.8   47.95  5633.4   52.57  5740.3   56.23
#Mann= 3 ,-1,0
  3297.4     .15       0  4990.4     .05       0  5009.6     .15       0
Bank Sta=4990.4,5009.6
XS Rating Curve= 0 ,0
Exp/Cntr=0.3,0.1

Type RM Length L Ch R = 1 ,34790   ,379,379,379
BEGIN DESCRIPTION:
Maple Swamp 56.0
END DESCRIPTION:
XS GIS Cut Line= 3
      2604019.04       779463.34       2604130.8       777831.67
      2604210.23       777029.69
#Sta/Elev= 30
  3364.5   46.74  3388.6   47.04    3428    46.4  3488.1   46.88  3518.2   46.39
  3582.3   43.53  3743.7   40.71  3939.2   43.18  4066.5   40.72  4149.7    40.3
  4239.9    40.9  4292.5   39.27  4330.1   38.94  4390.2   40.42  4420.3    39.7
  4660.9   39.56  4781.2   38.56  4811.2   37.58  4989.8   36.32  4990.6   34.82
  5009.4   34.82  5010.2   36.32  5323.2   37.61  5421.4   46.75    5474   48.27
  5534.3   47.21  5594.6   48.24  5638.5   49.96  5715.1   54.24  5805.9   57.78
#Mann= 3 ,-1,0
  3364.5     .15       0  4989.8     .05       0  5010.2     .15       0
Bank Sta=4989.8,5010.2
XS Rating Curve= 0 ,0
Exp/Cntr=0.3,0.1

Type RM Length L Ch R = 1 ,34411   ,638,638,638
BEGIN DESCRIPTION:
Maple Swamp 55.0
END DESCRIPTION:
XS GIS Cut Line= 3
      2604505.68       779714.18      2604448.85       777652.66
       2604300.8       777051.32
#Sta/Elev= 30
  2937.7   46.28  3122.5   46.84    3222   45.31    3282   42.66    3342   42.22
  3543.1   44.59  3612.1   43.26  3642.1   43.81  3732.2   43.05  3792.2   45.42
  3882.2   45.82  4057.1    40.9    4174   41.34  4290.8   39.69  4436.8   39.12
  4692.5   39.51  4752.6   38.75  4782.6   37.41  4902.6   37.33  4989.8   36.19
  4990.6   34.69  5009.4   34.69  5010.2   36.19  5023.3   37.54  5216.1   37.56
  5315.3   38.81  5364.9   41.69  5414.4   50.69  5486.8   54.71  5619.3   58.86
#Mann= 3 ,-1,0
  2937.7     .15       0  4989.8     .05       0  5010.2     .15       0
Bank Sta=4989.8,5010.2
XS Rating Curve= 0 ,0
Exp/Cntr=0.3,0.1

Type RM Length L Ch R = 1 ,33773   ,734,734,734
BEGIN DESCRIPTION:
Maple Swamp 54.0
END DESCRIPTION:
XS GIS Cut Line= 3
      2604612.74       779585.56      2604954.87       777305.48
      2604969.96       776608.55
#Sta/Elev= 30
  2694.4    43.7  2760.7   45.57  2851.7   46.02  3004.6   42.45  3108.8   43.55
  3155.1   45.47  3501.4   46.57  3610.1   45.62  3670.8   44.02  3701.1   41.81
  3822.4   39.49  4125.8   38.58  4307.8   39.53  4398.8    37.2  4536.4   38.42
  4853.9    36.6  4956.6   37.01  4989.8   35.97  4990.6   34.47  5009.4   34.47
  5010.2   35.97  5245.5   38.47  5275.5   39.69  5304.1   42.17  5412.5   46.03
  5425.6   47.75  5480.3   49.75  5568.4   55.57  5644.5   57.66  5697.1   57.63
#Mann= 3 ,-1,0
  2694.4     .15       0  4989.8     .05       0  5010.2     .15       0
Bank Sta=4989.8,5010.2
XS Rating Curve= 0 ,0
Exp/Cntr=0.3,0.1

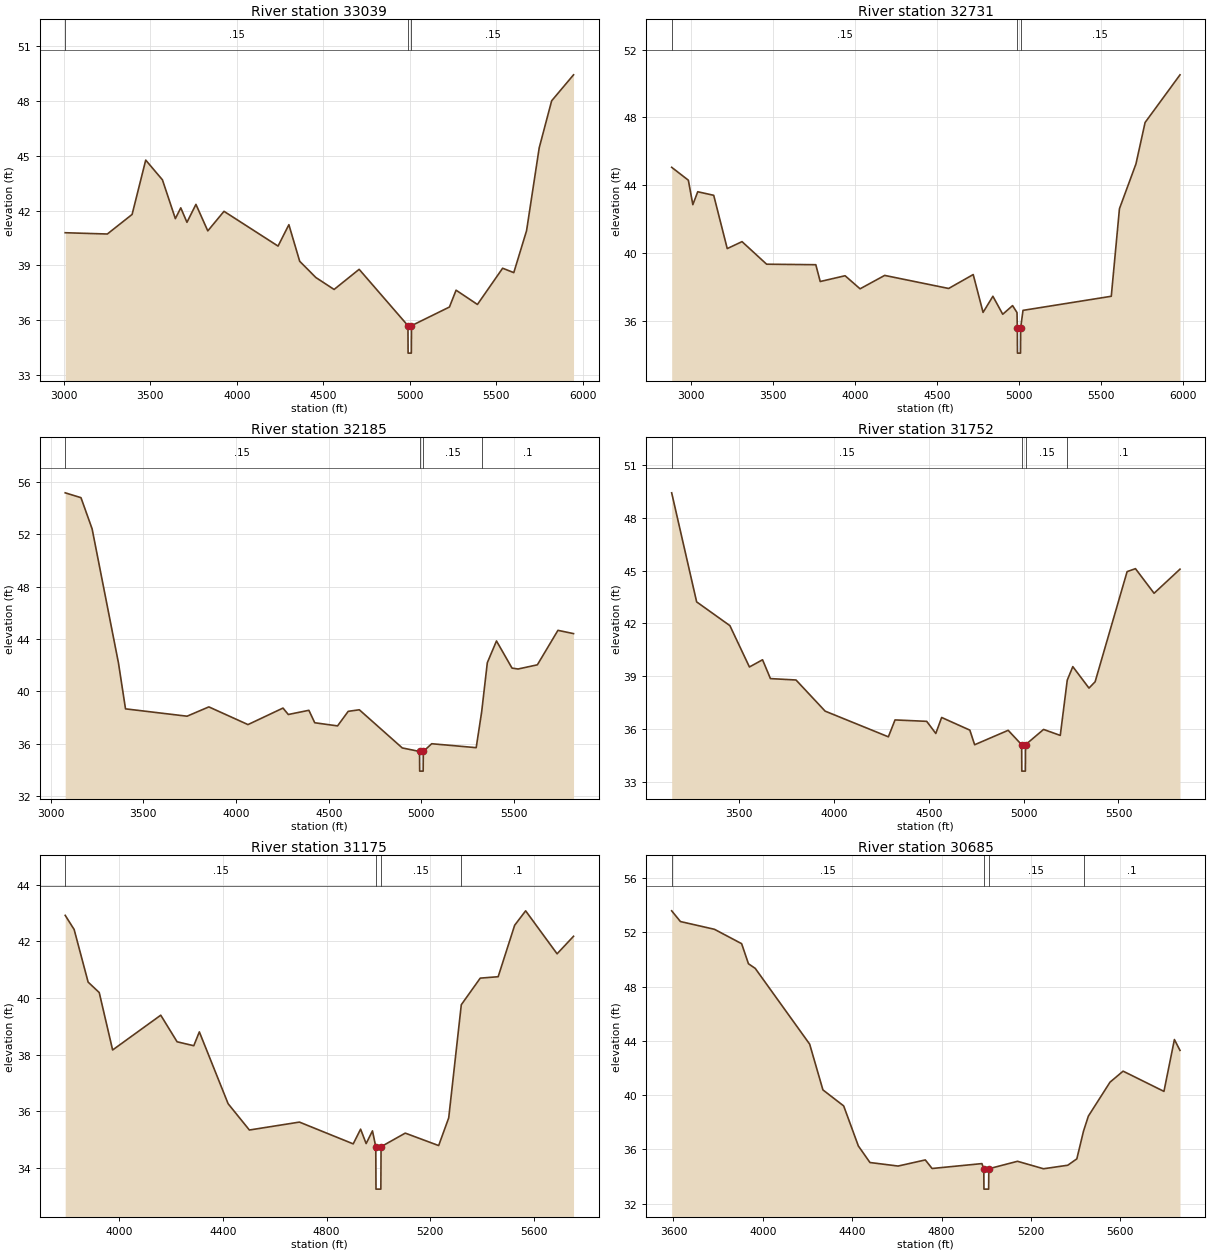
Type RM Length L Ch R = 1 ,33039   ,308,308,308
BEGIN DESCRIPTION:
Maple Swamp 53.0
END DESCRIPTION:
XS GIS Cut Line= 3
      2604874.38        779711.3      2605431.29       777799.36
      2605779.99         776919.
#Sta/Elev= 30
  3008.6   40.79  3252.1   40.72  3395.3   41.79    3474   44.76  3570.7   43.68
  3645.3   41.56  3676.6   42.15  3712.4   41.36  3764.3   42.34  3832.8   40.89
  3926.5   41.96    4239   40.06  4301.5   41.23    4364   39.23  4457.7   38.34
  4562.9   37.69  4707.7   38.79  4989.8   35.71  4990.6   34.21  5009.4   34.21
  5010.2   35.71  5229.6   36.73    5268   37.65  5391.4   36.87  5537.1   38.85
  5601.6   38.61  5675.4    40.9  5748.5   45.43  5820.4      48  5946.9   49.42
#Mann= 3 ,-1,0
  3008.6     .15       0  4989.8     .05       0  5010.2     .15       0
Bank Sta=4989.8,5010.2
XS Rating Curve= 0 ,0
Exp/Cntr=0.3,0.1

Type RM Length L Ch R = 1 ,32731   ,546,546,546
BEGIN DESCRIPTION:
Maple Swamp 52.0
END DESCRIPTION:
XS GIS Cut Line= 3
      2605800.31         779949.      2605736.66       777830.85
      2605823.35       776852.38
#Sta/Elev= 30
  2880.9   45.06  2982.7    44.3    3010   42.86    3040   43.62  3137.4   43.41
    3220   40.27  3310.1   40.68  3460.2   39.35  3760.3   39.32  3787.2   38.33
  3938.9   38.67  4030.4    37.9  4180.5   38.69  4570.7   37.92  4720.7   38.74
  4780.8   36.51  4840.8   37.46  4900.8    36.4  4960.8   36.91  4987.9    36.5
  4989.8   35.61  4990.6   34.11  5009.4   34.11  5010.2   35.61  5024.5   36.63
    5563   37.46  5612.9   42.62  5713.6   45.26  5769.3    47.7  5982.3   50.51
#Mann= 3 ,-1,0
  2880.9     .15       0  4989.8     .05       0  5010.2     .15       0
Bank Sta=4989.8,5010.2
XS Rating Curve= 0 ,0
Exp/Cntr=0.3,0.1

Type RM Length L Ch R = 1 ,32185   ,433,433,433
BEGIN DESCRIPTION:
Maple Swamp 51.0
END DESCRIPTION:
XS GIS Cut Line= 3
      2606376.23       779755.02      2606282.08       777835.33
      2606256.43       777015.03
#Sta/Elev= 30
    3078   55.15  3163.1   54.78  3223.2    52.4  3365.5   42.16  3403.4   38.67
  3735.3   38.11  3853.1   38.82  4064.2   37.47  4253.1   38.73  4281.7   38.24
  4392.8   38.56  4424.4   37.61  4547.5   37.37  4604.9   38.48  4664.9    38.6
  4896.6   35.69  4989.8   35.42  4990.6   33.92  5009.4   33.92  5010.2   35.42
  5055.4   36.01  5295.5   35.71    5325   38.44  5355.5   42.19    5405   43.85
  5488.8   41.78  5521.4   41.71  5625.6   42.03  5736.6   44.66  5820.7   44.41
#Mann= 4 ,-1,0
    3078     .15       0  4989.8     .05       0  5010.2     .15       0
    5325      .1       0
Bank Sta=4989.8,5010.2
XS Rating Curve= 0 ,0
Exp/Cntr=0.3,0.1

Type RM Length L Ch R = 1 ,31752   ,577,577,577
BEGIN DESCRIPTION:
Maple Swamp 50.0
END DESCRIPTION:
XS GIS Cut Line= 3
      2607085.74       779530.58      2606695.88       777717.72
       2606288.7       777001.24
#Sta/Elev= 30
  3145.7   49.42  3277.3   43.22  3452.5   41.87  3555.4   39.52  3624.5   39.93
  3666.1   38.86  3800.9   38.78  3954.3   37.01  4287.5   35.55  4322.6   36.51
  4489.5   36.43  4537.4   35.74  4568.2   36.65  4716.8   35.93  4742.1    35.1
  4918.8   35.92  4989.8    35.1  4990.6    33.6  5009.4    33.6  5010.2    35.1
  5105.3   35.97  5193.3   35.63    5230   38.77  5259.3   39.54  5344.6   38.32
  5376.9   38.68  5545.4   44.94  5589.4   45.11  5687.5   43.71  5824.1   45.08
#Mann= 4 ,-1,0
  3145.7     .15       0  4989.8     .05       0  5010.2     .15       0
    5230      .1       0
Bank Sta=4989.8,5010.2
XS Rating Curve= 0 ,0
Exp/Cntr=0.3,0.1

Type RM Length L Ch R = 1 ,31175   ,490,490,490
BEGIN DESCRIPTION:
Maple Swamp 49.0
END DESCRIPTION:
XS GIS Cut Line= 3
      2607905.85       778407.84      2607192.34       777431.46
      2606666.51       776892.05
#Sta/Elev= 30
  3790.7   42.92  3825.2   42.42  3879.2   40.56  3922.1   40.19  3973.8   38.16
  4159.6   39.39  4222.7   38.45  4287.1   38.31  4308.6    38.8  4419.7   36.26
  4501.8   35.33    4695   35.61  4902.7   34.84  4931.2   35.36  4952.6   34.85
    4977    35.3  4989.8   34.74  4990.6   33.24  5009.4   33.24  5010.2   34.74
  5103.6   35.22  5232.6   34.78  5271.4   35.76    5320   39.76  5393.1    40.7
  5462.3   40.75    5526   42.57  5568.4   43.08  5689.8   41.56  5753.3   42.18
#Mann= 4 ,-1,0
  3790.7     .15       0  4989.8     .05       0  5010.2     .15       0
    5320      .1       0
Bank Sta=4989.8,5010.2
XS Rating Curve= 0 ,0
Exp/Cntr=0.3,0.1

Type RM Length L Ch R = 1 ,30685   ,455,455,455
BEGIN DESCRIPTION:
Maple Swamp 48.0
END DESCRIPTION:
XS GIS Cut Line= 3
      2608928.62       777326.03      2607541.01       777087.89
      2606726.42        776791.6
#Sta/Elev= 30
  3592.1   53.58  3631.3   52.79  3783.5   52.22  3905.2   51.16  3935.7   49.68
  3966.1   49.34  4209.6   43.76  4268.9   40.39  4361.8   39.21  4427.5   36.26
  4479.4   35.04  4605.3   34.78  4727.1   35.23  4757.5    34.6  4980.4   34.96
  4988.8   34.58  4989.5   33.08  5010.5   33.08  5011.2   34.58  5139.6   35.13
  5256.1   34.58  5364.6   34.84  5405.1   35.31    5435   37.35  5456.8   38.46
  5553.7   40.96  5612.2   41.77    5795   40.28  5841.8    44.1  5866.8    43.3
#Mann= 4 ,-1,0
  3592.1     .15       0  4988.8     .05       0  5011.2     .15       0
    5435      .1       0
Bank Sta=4988.8,5011.2
XS Rating Curve= 0 ,0
Exp/Cntr=0.3,0.1

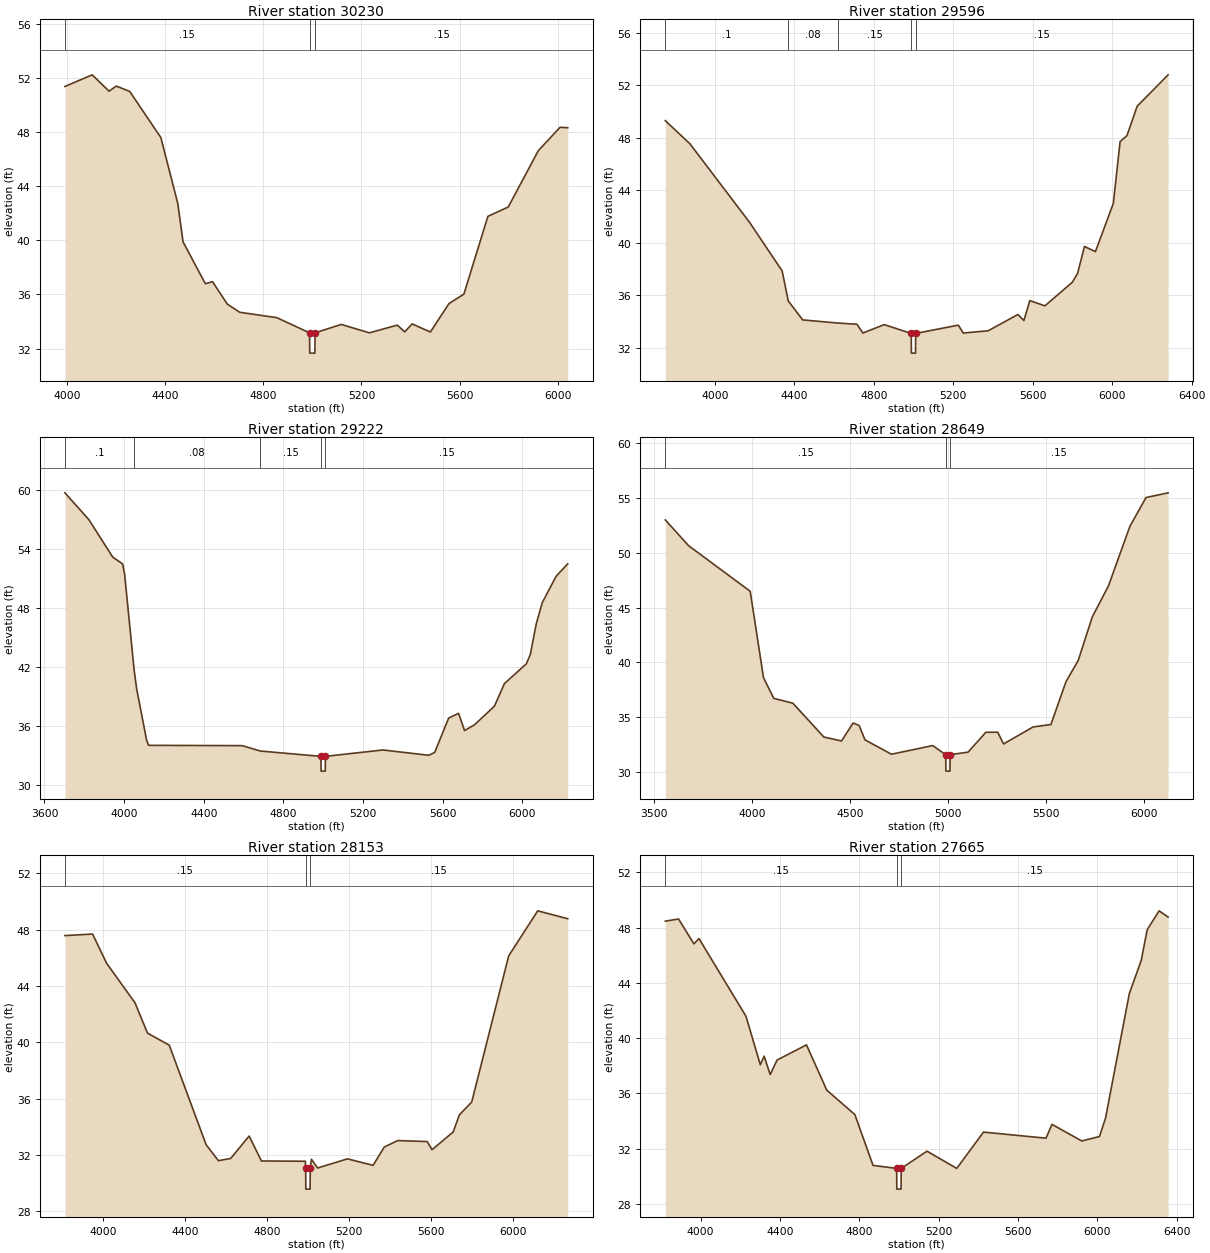
Type RM Length L Ch R = 1 ,30230   ,634,634,634
BEGIN DESCRIPTION:
Maple Swamp 47.0
END DESCRIPTION:
XS GIS Cut Line= 3
      2608739.78       776773.16      2607734.87       776698.22
      2606698.76       776602.69
#Sta/Elev= 30
  3992.3   51.37  4103.5   52.23  4172.1   51.02  4201.5    51.4  4256.3      51
  4383.2   47.59  4452.3    42.7  4473.4   39.89  4564.3   36.79  4593.7   36.94
  4653.9   35.28  4704.3   34.68  4855.5   34.28  4988.8   33.16  4989.5   31.66
  5010.5   31.66  5011.2   33.16    5118   33.78  5232.7   33.16  5346.3   33.73
  5376.5   33.23  5406.6   33.82    5481   33.22  5557.2   35.33  5617.5   36.02
  5715.3   41.77  5798.2   42.46  5920.6   46.62  6009.1   48.35  6040.5   48.32
#Mann= 3 ,-1,0
  3992.3     .15       0  4988.8     .05       0  5011.2     .15       0
Bank Sta=4988.8,5011.2
XS Rating Curve= 0 ,0
Exp/Cntr=0.3,0.1

Type RM Length L Ch R = 1 ,29596   ,374,374,374
BEGIN DESCRIPTION:
Maple Swamp 46.0
END DESCRIPTION:
XS GIS Cut Line= 3
      2609103.73       776160.39      2607855.66       776120.48
      2606574.34       776141.96
#Sta/Elev= 30
  3751.3   49.31  3875.1   47.55  4175.2   41.57  4339.2   37.87    4370   35.58
  4442.6   34.14    4620    33.9  4715.5   33.81  4745.5   33.14    4853   33.78
  4988.8   33.11  4989.5   31.61  5010.5   31.61  5011.2   33.11  5225.7   33.74
  5250.4   33.14  5375.6   33.31  5525.7   34.55  5555.7   34.09  5585.7   35.61
  5661.5   35.21  5799.7   37.01  5825.8   37.68  5860.7   39.73  5915.8   39.34
  6005.8   43.01  6039.8   47.71  6074.3   48.17  6125.8   50.41  6281.5    52.8
#Mann= 5 ,-1,0
  3751.3      .1       0    4370     .08       0    4620     .15       0
  4988.8     .05       0  5011.2     .15       0
Bank Sta=4988.8,5011.2
XS Rating Curve= 0 ,0
Exp/Cntr=0.3,0.1

Type RM Length L Ch R = 1 ,29222   ,573,573,573
BEGIN DESCRIPTION:
Maple Swamp 45.0
END DESCRIPTION:
XS GIS Cut Line= 3
      2609125.02         775775.      2607828.32       775747.12
      2606606.63       775872.43
#Sta/Elev= 30
    3703   59.73    3823   57.01    3943    53.2    3993    52.5    4003   51.42
    4050   41.83    4063   39.84    4113   34.61    4123   34.07    4593   34.04
    4685   33.49  4988.8   32.95  4989.5   31.45  5010.5   31.45  5011.2   32.95
    5300    33.6    5530   33.06    5560   33.35    5630   36.84    5680   37.32
    5710   35.57    5760   36.16    5860   38.05    5910   40.34    6020   42.35
    6040   43.28    6070   46.41    6100   48.56    6170   51.26  6228.1   52.51
#Mann= 5 ,-1,0
    3703      .1       0    4050     .08       0    4685     .15       0
  4988.8     .05       0  5011.2     .15       0
Bank Sta=4988.8,5011.2
XS Rating Curve= 0 ,0
Exp/Cntr=0.3,0.1

Type RM Length L Ch R = 1 ,28649   ,496,496,496
BEGIN DESCRIPTION:
Maple Swamp 44.0
END DESCRIPTION:
XS GIS Cut Line= 3
      2609232.69       775185.95      2607792.19       775184.97
      2606675.71       775070.77
#Sta/Elev= 30
  3559.5   52.99  3678.1   50.64  3992.2   46.48    4060    38.6  4112.2   36.72
  4209.9   36.27  4367.6   33.19  4457.5   32.83  4516.9   34.47  4547.5   34.24
  4577.4   32.93  4712.2   31.62  4922.2   32.41  4988.8   31.58  4989.5   30.08
  5010.5   30.08  5011.2   31.58  5102.7   31.81  5193.2   33.62  5253.5   33.63
  5283.7   32.56  5434.4   34.11  5524.9   34.33  5601.6   38.23  5664.3   40.18
    5736   44.15  5818.2   46.97  5927.6   52.41  6009.7   55.03  6122.3   55.46
#Mann= 3 ,-1,0
  3559.5     .15       0  4988.8     .05       0  5011.2     .15       0
Bank Sta=4988.8,5011.2
XS Rating Curve= 0 ,0
Exp/Cntr=0.3,0.1

Type RM Length L Ch R = 1 ,28153   ,488,488,488
BEGIN DESCRIPTION:
Maple Swamp 43.0
END DESCRIPTION:
XS GIS Cut Line= 3
        2609159.       774784.66      2607972.86       774723.93
      2606703.37       774729.37
#Sta/Elev= 30
  3812.3   47.58  3947.6   47.69  4015.8   45.62  4154.6   42.81  4215.9   40.65
    4322    39.8  4502.2   32.73  4562.3   31.59  4622.4   31.75  4712.5   33.34
  4772.6   31.57  4987.4   31.55  4988.8   31.07  4989.5   29.57  5010.5   29.57
  5011.2   31.07  5016.9   31.69    5047   31.07  5192.9   31.72  5318.2   31.26
  5372.9   32.56  5438.7   33.02  5582.9   32.95  5606.3   32.37  5709.8   33.63
    5740   34.85  5800.2   35.75    5981   46.14  6122.9   49.34  6269.5   48.78
#Mann= 3 ,-1,0
  3812.3     .15       0  4988.8     .05       0  5011.2     .15       0
Bank Sta=4988.8,5011.2
XS Rating Curve= 0 ,0
Exp/Cntr=0.3,0.1

Type RM Length L Ch R = 1 ,27665   ,815,815,815
BEGIN DESCRIPTION:
Maple Swamp 42.0
END DESCRIPTION:
XS GIS Cut Line= 3
      2609380.15       774517.43      2608221.47       774304.99
      2606864.56       774337.75
#Sta/Elev= 30
    3822   48.47  3888.7   48.63    3966   46.83  3991.8   47.21  4228.8   41.58
    4301   38.07  4320.3   38.69  4350.8   37.36  4385.6   38.41  4533.8   39.51
  4636.1   36.23  4777.8   34.46  4869.3   30.78  4988.6   30.56  4989.3   29.06
  5010.7   29.06  5011.4   30.56  5141.5   31.81  5291.5   30.56  5426.3   33.19
  5741.7   32.75  5771.7   33.75  5921.7   32.55  6011.2   32.87  6041.8   34.21
  6161.8   43.23  6221.8   45.63  6251.8   47.85  6311.8   49.22  6357.3   48.77
#Mann= 3 ,-1,0
    3822     .15       0  4988.6     .05       0  5011.4     .15       0
Bank Sta=4988.6,5011.4
XS Rating Curve= 0 ,0
Exp/Cntr=0.3,0.1

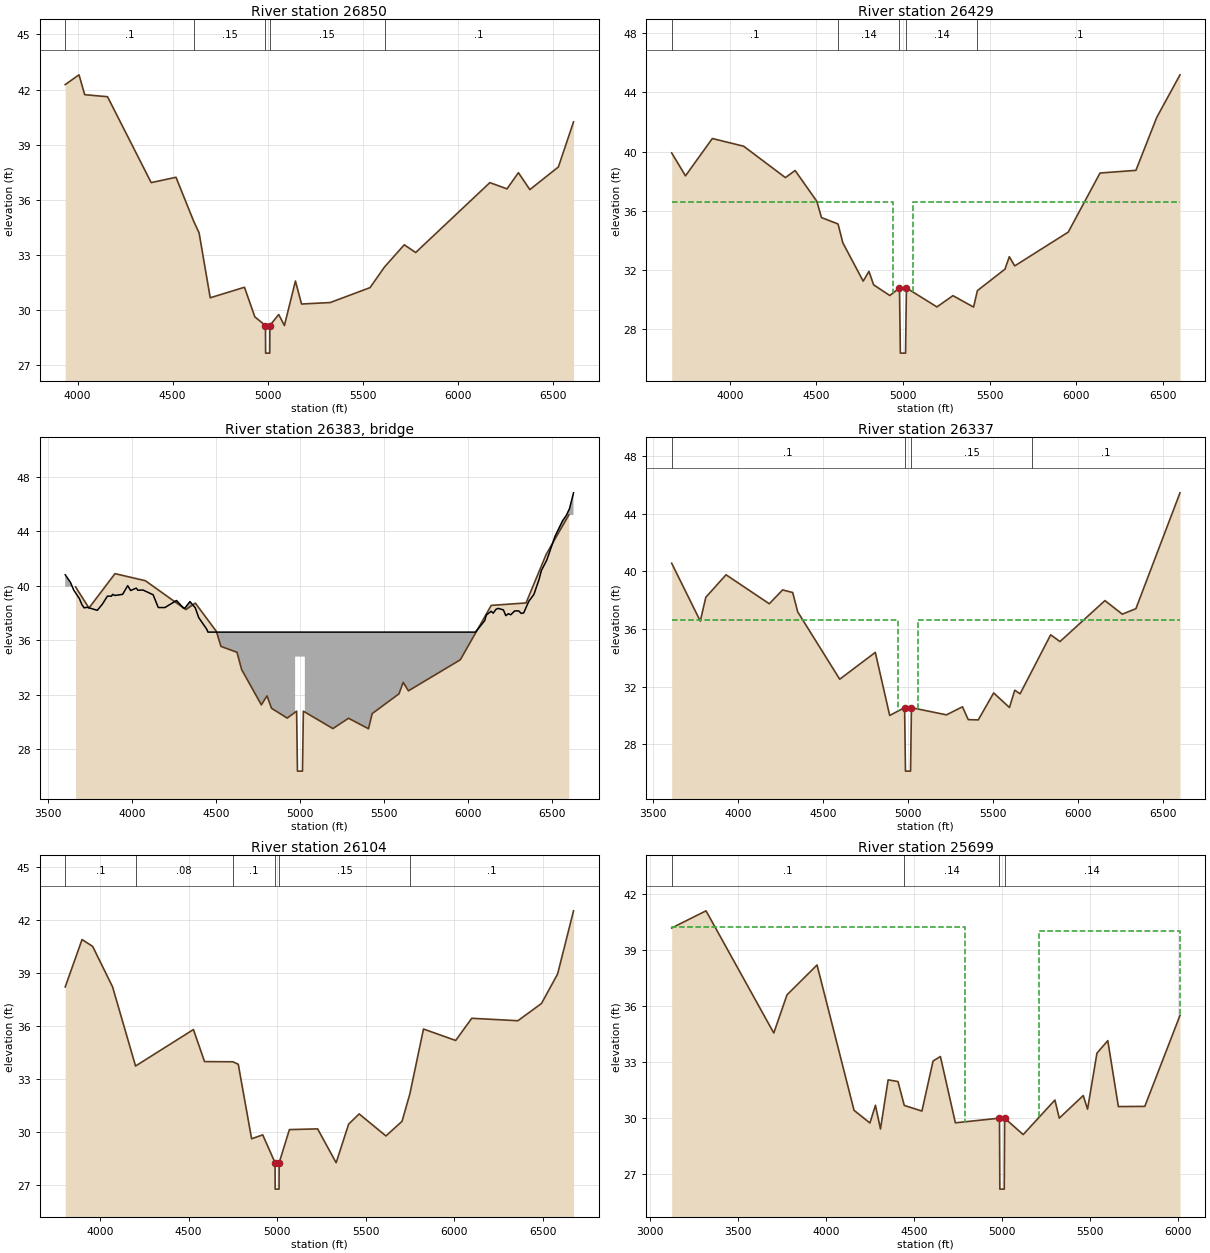
Type RM Length L Ch R = 1 ,26850   ,421,421,421
BEGIN DESCRIPTION:
Maple Swamp 41.0
END DESCRIPTION:
XS GIS Cut Line= 3
      2609352.54       773467.51      2608287.96       773497.37
      2606680.32       773438.87
#Sta/Elev= 30
    3935   42.27  4007.6    42.8  4037.6   41.72  4157.6   41.61  4387.3   36.94
  4517.8   37.23    4610   34.86  4639.2   34.21  4697.8   30.68  4877.9   31.25
  4932.5   29.64  4988.4   29.17  4989.1   27.67  5010.9   27.67  5011.6   29.17
    5058   29.77    5088   29.17    5146   31.59  5178.1   30.34  5328.9   30.42
  5538.3   31.23    5615   32.36  5718.4   33.56  5778.5   33.14  6168.7   36.94
  6258.8    36.6  6318.8   37.48  6378.9   36.56    6529   37.79  6608.7   40.24
#Mann= 5 ,-1,0
    3935      .1       0    4610     .15       0  4988.4     .05       0
  5011.6     .15       0    5615      .1       0
Bank Sta=4988.4,5011.6
XS Rating Curve= 0 ,0
Exp/Cntr=0.5,0.3

Type RM Length L Ch R = 1 ,26429   ,92,92,92
BEGIN DESCRIPTION:
Maple Swamp (Adrian HWY) US
END DESCRIPTION:
XS GIS Cut Line= 3
      2609513.78       772955.11      2608184.51       773090.06
      2606597.42       773296.04
#Sta/Elev= 30
  3663.9   39.92  3743.7   38.37  3898.9   40.89  4079.8   40.37    4321   38.25
    4377   38.73  4501.9   36.66  4529.6   35.55    4625   35.12  4652.7   33.85
  4770.2   31.26  4803.5   31.92  4830.7   31.01  4924.1   30.29    4980    30.8
    4985    26.4    5015    26.4    5020    30.8  5196.2   29.52  5288.8   30.28
  5407.9   29.51    5430   30.62  5589.4   32.07  5614.4   32.91  5645.7   32.29
  5954.8   34.57  6138.4   38.56  6345.7   38.74  6466.3   42.32  6600.4   45.19
#Mann= 5 ,-1,0
  3663.9      .1       0    4625     .14       0    4980     .05       0
    5020     .14       0    5430      .1       0
#XS Ineff= 2 , 0
       0    4940    36.6    5060       0    36.6
Permanent Ineff=
       F       F
Bank Sta=4980,5020
XS Rating Curve= 0 ,0
Exp/Cntr=0.5,0.3

Type RM Length L Ch R = 3 ,26383   ,,,
BEGIN DESCRIPTION:
Maple Swamp (Adrian HWY) TOR
Structure ID: LDS_MPS_03
Approximate Survey Structure
END DESCRIPTION:
Bridge Culvert--1,0,-1,-1, 0
Deck Dist Width WeirC Skew NumUp NumDn MinLoCord MaxHiCord MaxSubmerge Is_Ogee
28.5,35,3,0, 60, 60, , , 0.95, 0, 1,1,,
  3602.4  3633.8  3653.2  3687.1  3702.8  3715.4    3733  3793.3  3823.5  3853.7
  3878.7  3883.9  3898.5  3944.2  3974.4  3991.9  4025.8  4034.8  4064.9  4125.9
  4155.5  4159.2  4195.6  4264.8  4306.4  4313.8  4345.1  4376.4  4396.9    4445
  4452.1    4971    4971    5029    5029  6044.4  6099.7  6109.5  6138.4  6150.3
  6167.4  6180.5  6210.8  6225.4  6241.1  6254.4  6277.9  6301.6  6317.4  6331.8
  6362.1  6392.4  6422.6  6437.5  6469.1  6518.6  6563.6  6585.2  6604.2  6628.5
   40.81   40.25   39.68   39.05   38.59   38.38   38.42    38.2   38.65   39.24
   39.24   39.37   39.29   39.37   40.01   39.65   39.83   39.67   39.69   39.34
   38.43    38.4    38.4   38.92   38.37   38.35   38.84   38.39   37.67   36.81
    36.6    36.6    36.6    36.6    36.6    36.6   37.44   37.86   38.13   37.99
   38.28   38.34   38.23   37.81   37.95   37.87   38.15   38.16   37.97   38.01
   38.86   39.36   40.44   41.13   41.88   43.64   44.78   45.16   45.65   46.82
     6.4     6.4     6.4     6.4     6.4     6.4     6.4     6.4     6.4     6.4
     6.4     6.4     6.4     6.4     6.4     6.4     6.4     6.4     6.4     6.4
     6.4     6.4     6.4     6.4     6.4     6.4     6.4     6.4     6.4     6.4
     6.4     6.4    34.8    34.8     6.4     6.4     6.4     6.4     6.4     6.4
     6.4     6.4     6.4     6.4     6.4     6.4     6.4     6.4     6.4     6.4
     6.4     6.4     6.4     6.4     6.4     6.4     6.4     6.4     6.4     6.4
  3602.4  3633.8  3653.2  3687.1  3702.8  3715.4    3733  3793.3  3823.5  3853.7
  3878.7  3883.9  3898.5  3944.2  3974.4  3991.9  4025.8  4034.8  4064.9  4125.9
  4155.5  4159.2  4195.6  4264.8  4306.4  4313.8  4345.1  4376.4  4396.9    4445
  4452.1    4971    4971    5029    5029  6044.4  6099.7  6109.5  6138.4  6150.3
  6167.4  6180.5  6210.8  6225.4  6241.1  6254.4  6277.9  6301.6  6317.4  6331.8
  6362.1  6392.4  6422.6  6437.5  6469.1  6518.6  6563.6  6585.2  6604.2  6628.5
   40.81   40.25   39.68   39.05   38.59   38.38   38.42    38.2   38.65   39.24
   39.24   39.37   39.29   39.37   40.01   39.65   39.83   39.67   39.69   39.34
   38.43    38.4    38.4   38.92   38.37   38.35   38.84   38.39   37.67   36.81
    36.6    36.6    36.6    36.6    36.6    36.6   37.44   37.86   38.13   37.99
   38.28   38.34   38.23   37.81   37.95   37.87   38.15   38.16   37.97   38.01
   38.86   39.36   40.44   41.13   41.88   43.64   44.78   45.16   45.65   46.82
     6.4     6.4     6.4     6.4     6.4     6.4     6.4     6.4     6.4     6.4
     6.4     6.4     6.4     6.4     6.4     6.4     6.4     6.4     6.4     6.4
     6.4     6.4     6.4     6.4     6.4     6.4     6.4     6.4     6.4     6.4
     6.4     6.4    34.8    34.8     6.4     6.4     6.4     6.4     6.4     6.4
     6.4     6.4     6.4     6.4     6.4     6.4     6.4     6.4     6.4     6.4
     6.4     6.4     6.4     6.4     6.4     6.4     6.4     6.4     6.4     6.4
Abutment Skew #Up #Dn= , 2 , 2
    4971    4986
    34.8    26.4
    4971    4986
    34.8   26.15
Abutment Skew #Up #Dn= , 2 , 2
    5014    5029
    26.4    34.8
    5014    5029
   26.15    34.8
BR Coef= 1 , 1 , 0 ,1.25, 0 ,,,0.8,0,2,0,
WSPro=,,,, 1 ,,,, 0 ,,,, 0 ,,,,-1 ,-1 ,-1 , 0 , 0 , 0 , 0 , 0
BC Design=,, 0 ,, 0 ,,,,,,
BC HTab HWMax=45.19
BC Use User HTab Curves=0
BC User HTab FreeFlow(D)= 0

Type RM Length L Ch R = 1 ,26337   ,233,233,233
BEGIN DESCRIPTION:
Maple Swamp (Adrian HWY) DS
END DESCRIPTION:
XS GIS Cut Line= 3
      2609536.82       772830.71      2608159.17       773002.33
      2606574.34        773203.9
#Sta/Elev= 30
  3611.7   40.56  3779.8   36.55  3812.3    38.2    3931   39.76  4185.2   37.75
  4263.5   38.71  4322.6   38.53    4352   37.19  4598.8   32.52  4807.9   34.38
  4892.3   30.01    4980   30.55    4985   26.15    5015   26.15    5020   30.55
  5225.8   30.05  5319.9   30.61  5353.7   29.72  5412.5    29.7  5503.2   31.57
  5595.8   30.56    5627   31.76  5658.3   31.51    5730   33.14  5837.9    35.6
  5892.6   35.13  6156.7   37.97  6258.8   37.03  6338.6   37.41  6597.6   45.44
#Mann= 4 ,-1,0
  3611.7      .1       0    4980     .05       0    5020     .15       0
    5730      .1       0
#XS Ineff= 2 , 0
       0    4940    36.6    5060       0    36.6
Permanent Ineff=
       F       F
Bank Sta=4980,5020
XS Rating Curve= 0 ,0
Exp/Cntr=0.5,0.3

Type RM Length L Ch R = 1 ,26104   ,405,405,405
BEGIN DESCRIPTION:
Maple Swamp 40.0
END DESCRIPTION:
XS GIS Cut Line= 3
      2609315.06       772720.56      2608118.74       772773.71
       2606460.8        773012.9
#Sta/Elev= 30
  3802.5   38.22  3897.7   40.91  3957.7   40.52  4070.3   38.22    4200   33.73
  4527.1    35.8    4590   33.98    4750   33.97  4780.5   33.83  4855.9    29.6
  4918.7   29.82  4988.4   28.24  4989.1   26.74  5010.9   26.74  5011.6   28.24
  5069.5   30.12  5228.9   30.16  5333.5   28.24  5404.3   30.43  5463.5   31.01
    5615   29.76    5706   30.59    5750   32.14  5827.2   35.83  6009.1   35.18
    6100   36.44  6360.7    36.3    6494   37.28    6585   38.95  6675.1   42.54
#Mann= 6 ,-1,0
  3802.5      .1       0    4200     .08       0    4750      .1       0
  4988.4     .05       0  5011.6     .15       0    5750      .1       0
Bank Sta=4988.4,5011.6
XS Rating Curve= 0 ,0
Exp/Cntr=0.5,0.3

Type RM Length L Ch R = 1 ,25699   ,201,201,201
BEGIN DESCRIPTION:
Maple Swamp (HWY-22) US
END DESCRIPTION:
XS GIS Cut Line= 3
      2609865.09       772433.63      2607989.93       772392.94
      2606980.28       772426.34
#Sta/Elev= 30
  3124.4   40.18  3319.5    41.1  3704.1   34.56  3779.1    36.6  3949.7    38.2
  4159.7   30.42  4249.9   29.74  4281.2   30.69  4309.8   29.42  4353.3   32.05
  4409.2   31.96    4445   30.68  4545.1   30.38  4608.4   33.06  4650.1    33.3
    4735   29.75  4985.3      30  4987.5    26.2  5012.5    26.2  5014.7      30
    5120   29.12  5300.1   30.97  5324.9      30  5460.8   31.21  5485.4   30.48
  5538.7   33.48  5600.3   34.15  5660.3   30.62  5810.4   30.63  6010.2    35.5
#Mann= 4 ,-1,0
  3124.4      .1       0    4445     .14       0  4985.3     .05       0
  5014.7     .14       0
#XS Ineff= 2 , 0
       0    4790   40.22    5210       0      40
Permanent Ineff=
       F       F
Bank Sta=4985.3,5014.7
XS Rating Curve= 0 ,0
Exp/Cntr=0.5,0.3