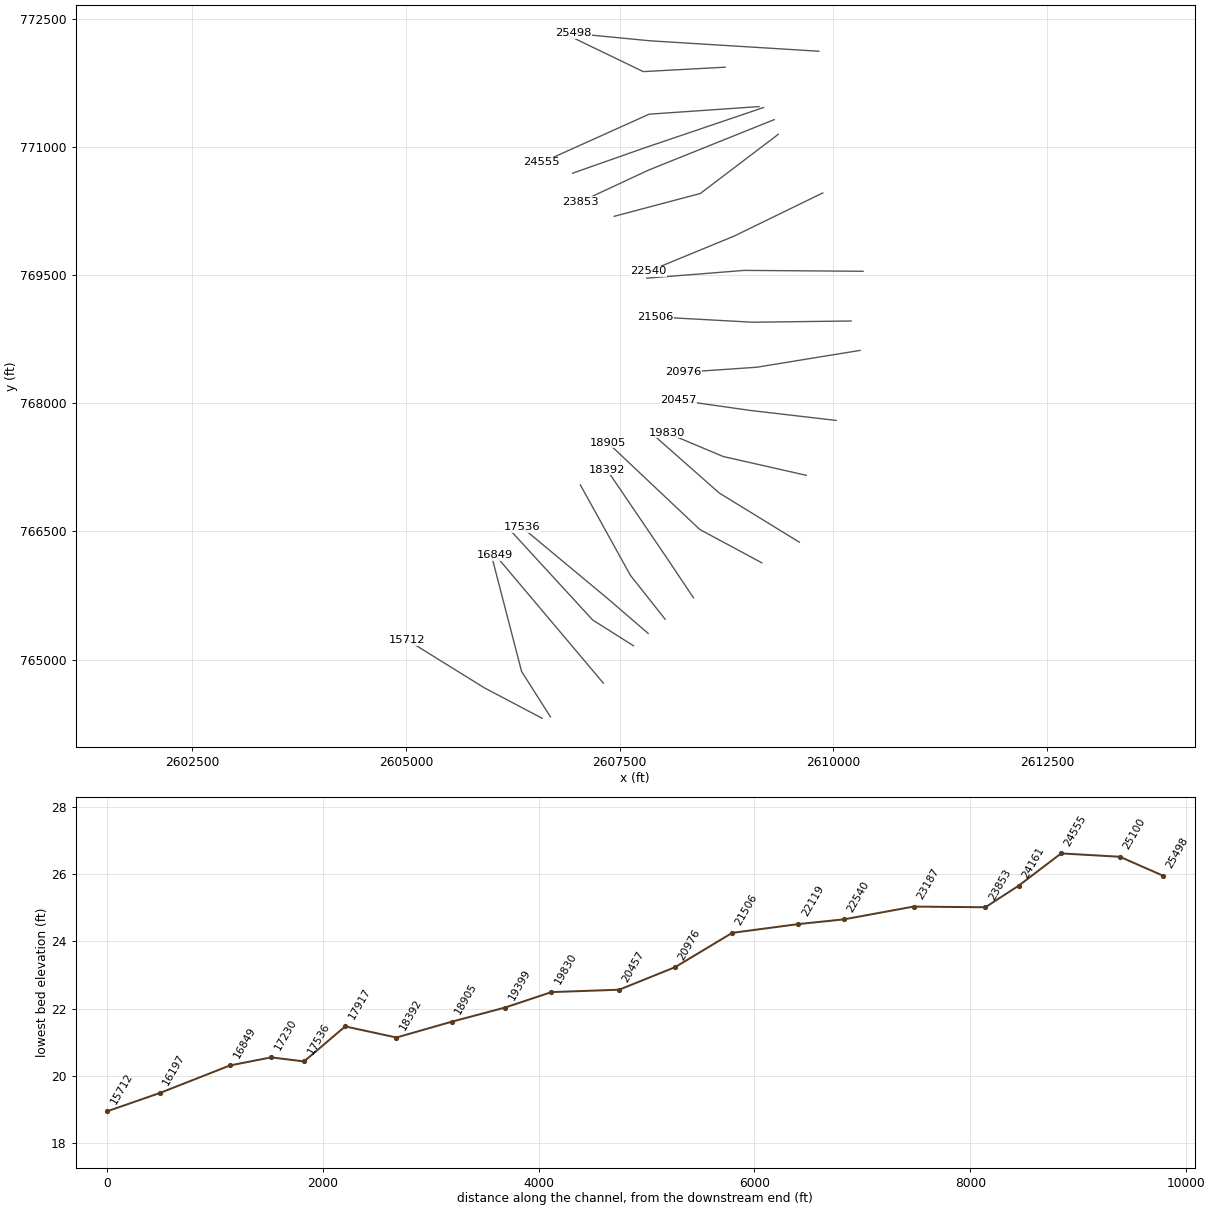
HEC-RAS study MapleSwamp.prj: S-26-65 over Maple Swamp

--- MapleSwamp.g01 (geometry) --- (continued)

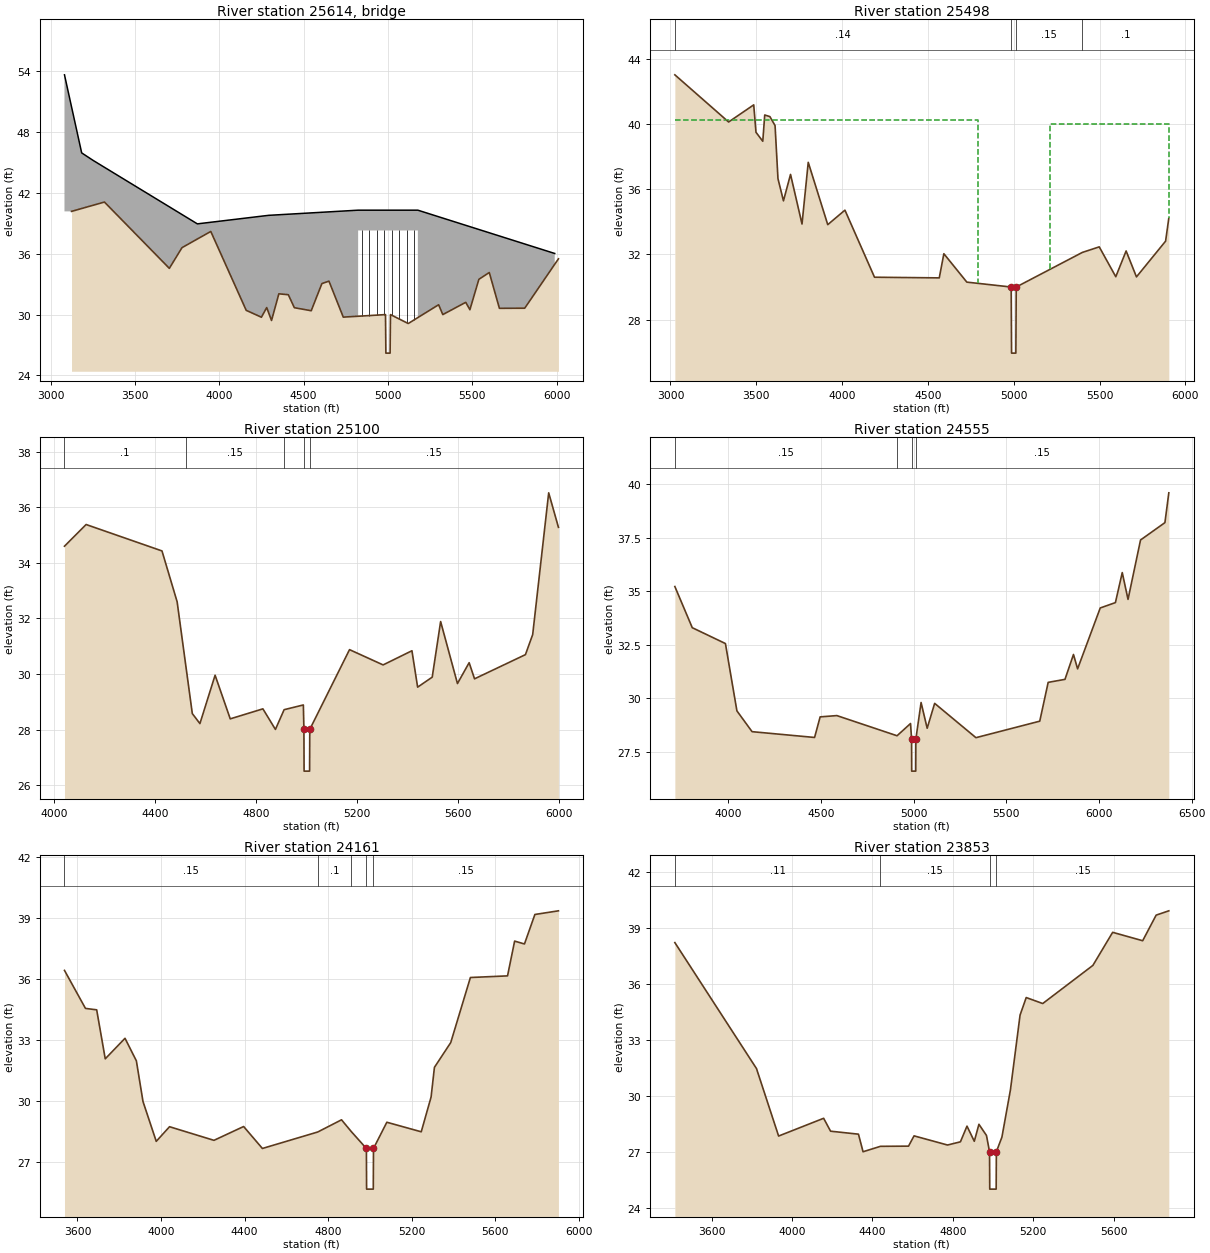
Type RM Length L Ch R = 3 ,25614   ,,,
BEGIN DESCRIPTION:
Maple Swamp (HWY-22) TOR
Structure ID: LDS_MPS_02A
Approximate Survey Structure
END DESCRIPTION:
Bridge Culvert--1,0,-1,-1, 0
Deck Dist Width WeirC Skew NumUp NumDn MinLoCord MaxHiCord MaxSubmerge Is_Ogee
29.5,111,3,0, 10, 10, , , 0.95, 0, 1,1,,
  3082.7  3184.6  3252.3  3870.1  4291.6    4823    4823    5177    5177  5988.2
   53.65   45.95   45.21   38.95   39.79    40.3    40.3    40.3    40.3   36.03
    6.16    6.16    6.16    6.16    6.16    6.16    38.3    38.3    6.16    6.16
  3082.7  3184.6  3252.3  3870.1  4291.6    4823    4823    5177    5177  5988.2
   53.65   45.95   45.21   38.95   39.79    40.3    40.3    40.3    40.3   36.03
    6.16    6.16    6.16    6.16    6.16    6.16    38.3    38.3    6.16    6.16
Pier Skew, UpSta & Num, DnSta & Num=  ,4845.1, 2 ,4845.1, 2 , 0 , 0 , 0 ,0,0
     1.5     1.5
   29.61    38.3
     1.5     1.5
   29.81    38.3
Pier Skew, UpSta & Num, DnSta & Num=  ,4889.4, 2 ,4889.4, 2 , 0 , 0 , 0 ,0,0
     1.5     1.5
   29.93    38.3
     1.5     1.5
   29.91    38.3
Pier Skew, UpSta & Num, DnSta & Num=  ,4933.6, 2 ,4933.6, 2 , 0 , 0 , 0 ,0,0
     1.5     1.5
   29.41    38.3
     1.5     1.5
   28.98    38.3
Pier Skew, UpSta & Num, DnSta & Num=  ,4977.9, 2 ,4977.9, 2 , 0 , 0 , 0 ,0,0
     1.5     1.5
   30.73    38.3
     1.5     1.5
   30.39    38.3
Pier Skew, UpSta & Num, DnSta & Num=  ,5022.1, 2 ,5022.1, 2 , 0 , 0 , 0 ,0,0
     1.5     1.5
   30.29    38.3
     1.5     1.5
   30.64    38.3
Pier Skew, UpSta & Num, DnSta & Num=  ,5066.4, 2 ,5066.4, 2 , 0 , 0 , 0 ,0,0
     1.5     1.5
   29.56    38.3
     1.5     1.5
   29.14    38.3
Pier Skew, UpSta & Num, DnSta & Num=  ,5110.6, 2 ,5110.6, 2 , 0 , 0 , 0 ,0,0
     1.5     1.5
   29.33    38.3
     1.5     1.5
   29.92    38.3
Pier Skew, UpSta & Num, DnSta & Num=  ,5154.9, 2 ,5154.9, 2 , 0 , 0 , 0 ,0,0
     1.5     1.5
   29.21    38.3
     1.5     1.5
   30.32    38.3
Abutment Skew #Up #Dn= , 2 , 2
    4823    4836
    38.3   29.41
    4823    4836
    38.3   30.11
Abutment Skew #Up #Dn= , 2 , 2
    5164    5177
    29.3    38.3
    5164    5177
   30.41    38.3
BR Coef= 1 , 1 , 0 ,1.25, 0 ,,,0.8,0,2,0,
WSPro=,,,, 1 ,,,, 0 ,,,, 0 ,,,,-1 ,-1 ,-1 , 0 , 0 , 0 , 0 , 0
BC Design=,, 0 ,, 0 ,,,,,,
BC HTab HWMax=41.21
BC Use User HTab Curves=0
BC User HTab FreeFlow(D)= 0

Type RM Length L Ch R = 1 ,25498   ,398,398,398
BEGIN DESCRIPTION:
Maple Swamp (HWY-22) DS
END DESCRIPTION:
XS GIS Cut Line= 3
      2609832.75       772119.89        2607862.       772241.55
       2606962.4       772328.56
#Sta/Elev= 30
  3025.5      43  3338.8   40.11    3485   41.16  3498.2   39.48  3537.8   38.93
  3549.2   40.54  3579.3   40.44  3609.4   39.89  3626.3   36.64  3658.3   35.28
  3699.5    36.9  3766.4   33.86  3802.7   37.64  3916.4   33.82  4016.5   34.71
  4188.9    30.6  4566.2   30.56    4593   32.04  4726.8    30.3  4985.3      30
  4987.5   25.95  5012.5   25.95  5014.7      30    5400   32.12  5498.4   32.46
  5594.8   30.63    5655   32.21  5715.3   30.62    5885   32.81  5903.8   34.22
#Mann= 4 ,-1,0
  3025.5     .14       0  4985.3     .05       0  5014.7     .15       0
    5400      .1       0
#XS Ineff= 2 , 0
       0    4790   40.22    5210       0      40
Permanent Ineff=
       F       F
Bank Sta=4985.3,5014.7
XS Rating Curve= 0 ,0
Exp/Cntr=0.5,0.3

Type RM Length L Ch R = 1 ,25100   ,545,545,545
BEGIN DESCRIPTION:
Maple Swamp 39.0
END DESCRIPTION:
XS GIS Cut Line= 3
      2608735.49       771933.27      2607777.19       771881.52
      2606879.79       772314.29
#Sta/Elev= 30
  4040.3    34.6  4125.9   35.38  4426.4   34.43  4486.4    32.6    4520   30.35
  4546.5   28.58  4576.6   28.22  4636.7   29.96  4696.7   28.39    4826   28.75
  4875.6   28.01    4910   28.72  4986.2   28.89  4988.4   28.01  4989.1   26.51
  5010.9   26.51  5011.6   28.01    5169   30.88    5302   30.33  5416.2   30.84
  5438.7   29.53  5496.5   29.89  5529.8   31.89  5596.4   29.66  5642.7   30.41
  5664.1   29.83  5865.6    30.7  5894.3   31.42  5957.7   36.52  5996.3   35.28
#Mann= 5 ,-1,0
  4040.3      .1       0    4520     .15       0    4910      .1       0
  4988.4     .05       0  5011.6     .15       0
Bank Sta=4988.4,5011.6
XS Rating Curve= 0 ,0
Exp/Cntr=0.3,0.1

Type RM Length L Ch R = 1 ,24555   ,394,394,394
BEGIN DESCRIPTION:
Maple Swamp 38.0
END DESCRIPTION:
XS GIS Cut Line= 3
      2609132.24       771472.17      2607846.22       771383.23
      2606590.87       770818.07
#Sta/Elev= 30
  3710.9   35.22  3804.8    33.3  3983.8   32.56  4045.8   29.42  4127.6   28.45
  4464.9   28.18    4495   29.14  4585.2    29.2    4910   28.26  4982.8   28.83
  4988.4   28.11  4989.1   26.61  5010.9   26.61  5011.6   28.11  5039.7   29.81
  5072.6   28.61    5113   29.77  5335.8   28.17  5680.2   28.94  5725.6   30.75
  5816.3   30.89  5862.2   32.05  5884.4   31.38  6006.6   34.22  6088.5   34.47
  6125.4   35.87  6156.6   34.62  6224.1   37.39  6355.7    38.2  6376.7   39.59
#Mann= 4 ,-1,0
  3710.9     .15       0    4910      .1       0  4988.4     .05       0
  5011.6     .15       0
Bank Sta=4988.4,5011.6
XS Rating Curve= 0 ,0
Exp/Cntr=0.3,0.1

Type RM Length L Ch R = 1 ,24161   ,308,308,308
BEGIN DESCRIPTION:
Maple Swamp 37.0
END DESCRIPTION:
XS GIS Cut Line= 3
      2609185.92       771461.47      2607801.24       770991.98
      2606950.06       770692.59
#Sta/Elev= 30
  3537.9   36.41  3638.3   34.54    3692   34.47    3733   32.06  3827.6   33.07
    3882   31.96  3913.7   29.96  3977.1      28  4040.7   28.72  4253.4   28.05
  4395.4   28.73  4485.3   27.65    4750   28.46    4864   29.06    4910   28.49
    4983   27.65    4984   25.65    5016   25.65    5017   27.65  5080.9   28.94
  5245.6   28.47  5292.7   30.18  5308.7   31.64  5386.8   32.86  5480.9   36.06
  5658.6   36.14  5692.6   37.85  5739.7   37.71  5789.5   39.16  5902.3   39.34
#Mann= 5 ,-1,0
  3537.9     .15       0    4750      .1       0    4910     .12       0
    4983     .05       0    5017     .15       0
Bank Sta=4983,5017
XS Rating Curve= 0 ,0
Exp/Cntr=0.3,0.1

Type RM Length L Ch R = 1 ,23853   ,666,666,666
BEGIN DESCRIPTION:
Maple Swamp 36.0
END DESCRIPTION:
XS GIS Cut Line= 3
      2609309.18       771319.36       2607840.1       770729.17
      2607046.62       770359.65
#Sta/Elev= 30
  3416.8    38.2  3823.1   31.46  3933.2   27.85  4157.3    28.8  4191.8   28.11
  4330.6   27.95  4353.5   27.01    4440    27.3  4579.8   27.31  4607.3   27.86
  4773.8   27.37    4838   27.54  4870.8   28.38  4907.2   27.57  4930.2   28.48
  4967.8   27.88    4983   27.01    4984   25.01    5016   25.01    5017   27.01
  5044.6   27.79    5087   30.32  5134.9   34.32  5165.6   35.26  5247.8   34.94
  5497.4   36.98  5595.8   38.75  5745.2    38.3  5812.3   39.67  5875.3    39.9
#Mann= 4 ,-1,0
  3416.8     .11       0    4440     .15       0    4983     .05       0
    5017     .15       0
Bank Sta=4983,5017
XS Rating Curve= 0 ,0
Exp/Cntr=0.3,0.1

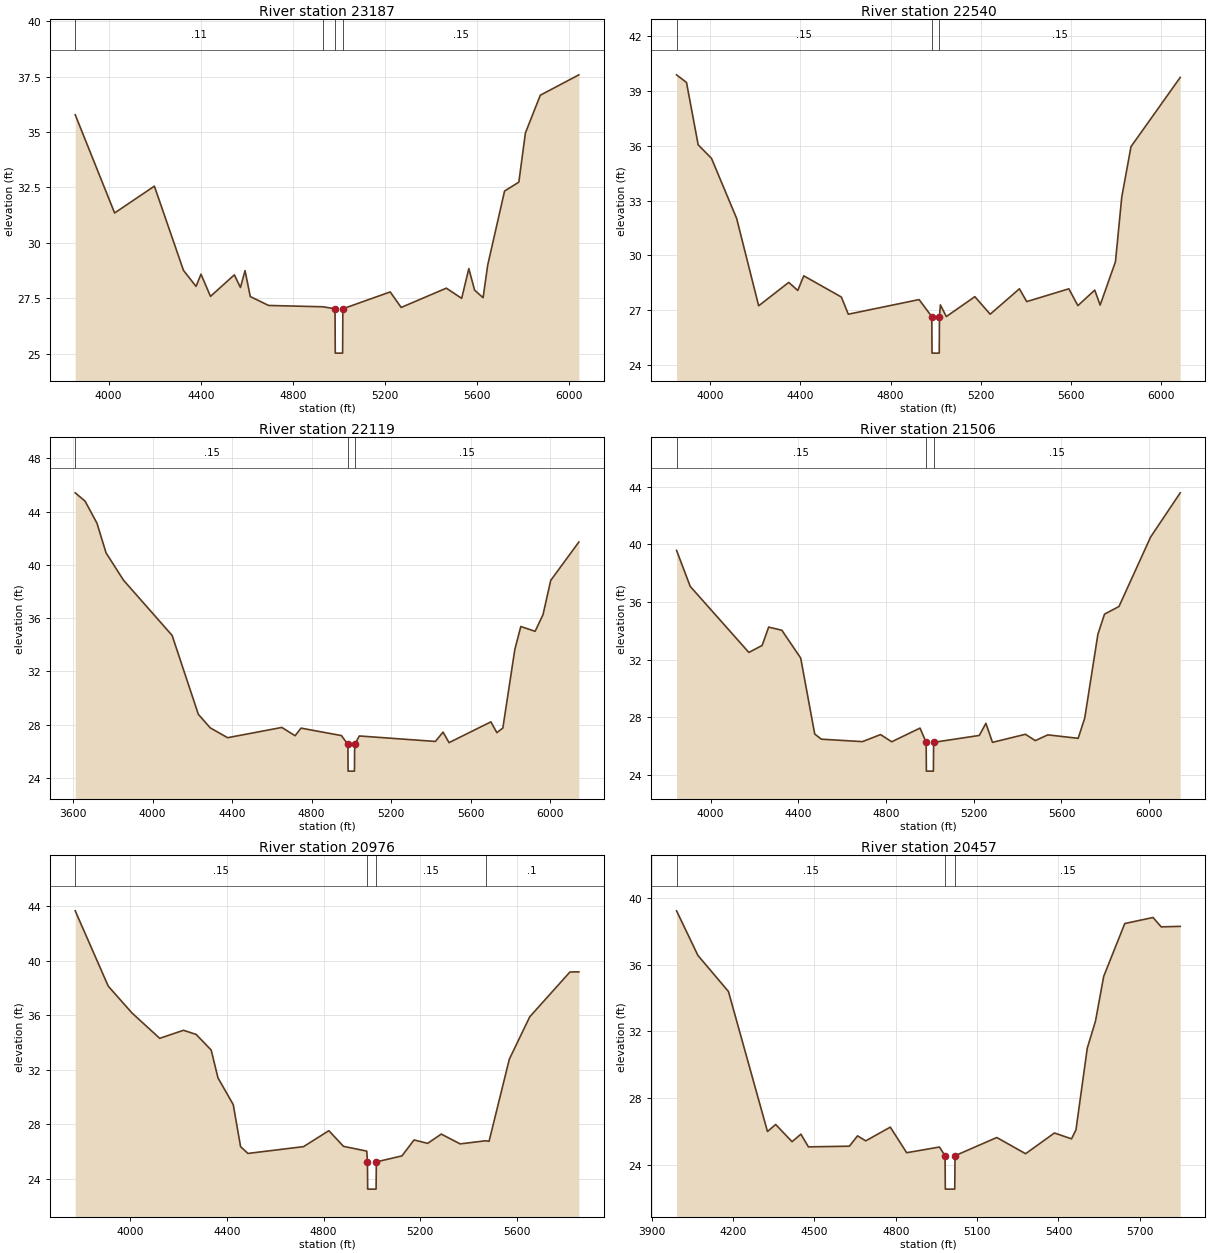
Type RM Length L Ch R = 1 ,23187   ,647,647,647
BEGIN DESCRIPTION:
Maple Swamp 35.0
END DESCRIPTION:
XS GIS Cut Line= 3
      2609357.48       771147.82       2608445.2       770455.39
      2607437.97       770188.06
#Sta/Elev= 30
  3854.7   35.78  4025.8   31.35  4198.5   32.56  4324.9   28.76  4379.5   28.04
  4400.9   28.59  4442.2   27.59  4545.8   28.56  4572.2   27.99  4592.2   28.75
    4615   27.58  4694.6   27.18    4930   27.12    4983   27.03    4984   25.03
    5016   25.03    5017   27.03  5222.7   27.79  5270.3   27.09  5466.5   27.96
    5533    27.5  5564.1   28.84  5589.2   27.87  5626.1   27.53  5646.1      29
  5719.3   32.34  5781.3   32.74  5809.9   34.96  5874.5   36.66  6042.1   37.58
#Mann= 4 ,-1,0
  3854.7     .11       0    4930     .15       0    4983     .05       0
    5017     .15       0
Bank Sta=4983,5017
XS Rating Curve= 0 ,0
Exp/Cntr=0.3,0.1

Type RM Length L Ch R = 1 ,22540   ,421,421,421
BEGIN DESCRIPTION:
Maple Swamp 34.0
END DESCRIPTION:
XS GIS Cut Line= 3
      2609877.57       770461.53      2608843.86       769958.05
      2607840.06       769544.65
#Sta/Elev= 30
  3850.2   39.88  3894.4   39.46  3946.1   36.05  4005.2   35.31  4116.9   32.02
  4214.6   27.24    4348   28.52  4388.1   28.08  4414.8   28.88  4581.6   27.72
  4612.5   26.78  4926.6   27.58    4983   26.65    4984   24.65    5016   24.65
    5017   26.65  5021.1   27.29  5047.4   26.65  5174.1   27.74  5242.1   26.78
  5371.9   28.17  5404.3   27.47  5591.3   28.17  5631.4   27.25  5706.2    28.1
  5730.2   27.28  5798.1   29.65  5826.1   33.19  5867.1   35.95  6085.6   39.74
#Mann= 3 ,-1,0
  3850.2     .15       0    4983     .05       0    5017     .15       0
Bank Sta=4983,5017
XS Rating Curve= 0 ,0
Exp/Cntr=0.3,0.1

Type RM Length L Ch R = 1 ,22119   ,613,613,613
BEGIN DESCRIPTION:
Maple Swamp 33.0
END DESCRIPTION:
XS GIS Cut Line= 3
      2610349.39       769544.66      2608960.33        769555.1
      2607818.64       769464.24
#Sta/Elev= 30
  3610.9   45.41  3660.3   44.79  3720.3   43.13  3766.1    40.9  3853.8   38.85
  4098.6    34.7  4230.3   28.78  4290.3   27.76  4377.6   27.02  4650.3   27.79
  4717.3   27.17  4747.1   27.74  4950.3   27.18    4983   26.51    4984   24.51
    5016   24.51    5017   26.51  5040.5   27.15  5423.2   26.74  5461.8   27.44
  5491.9   26.65  5702.5   28.21  5732.6    27.4  5762.7   27.75  5822.9   33.64
    5853   35.37    5925   35.01  5964.8   36.26  6003.5   38.83  6145.3   41.72
#Mann= 3 ,-1,0
  3610.9     .15       0    4983     .05       0    5017     .15       0
Bank Sta=4983,5017
XS Rating Curve= 0 ,0
Exp/Cntr=0.3,0.1

Type RM Length L Ch R = 1 ,21506   ,530,530,530
BEGIN DESCRIPTION:
Maple Swamp 32.0
END DESCRIPTION:
XS GIS Cut Line= 3
      2610209.99       768962.93      2609054.98       768948.78
      2607915.18       769011.18
#Sta/Elev= 30
  3844.9   39.59  3907.1   37.09  4174.4    32.5  4234.9   32.98  4264.9   34.26
  4324.9   34.04  4410.9   32.11  4474.9   26.83  4504.9   26.47  4692.4    26.3
    4775   26.79  4825.9   26.29    4955   27.24    4983   26.25    4984   24.25
    5016   24.25    5017   26.25  5225.3   26.73  5255.4   27.57  5285.4   26.25
  5435.6   26.81  5480.8   26.37  5537.6   26.77    5676   26.53    5706   27.93
  5766.1   33.76  5796.2   35.16  5862.2   35.69  6006.5   40.52  6141.5   43.59
#Mann= 3 ,-1,0
  3844.9     .15       0    4983     .05       0    5017     .15       0
Bank Sta=4983,5017
XS Rating Curve= 0 ,0
Exp/Cntr=0.3,0.1

Type RM Length L Ch R = 1 ,20976   ,519,519,519
BEGIN DESCRIPTION:
Maple Swamp 31.0
END DESCRIPTION:
XS GIS Cut Line= 3
      2610314.77       768618.94      2609104.15       768421.65
      2608250.25       768363.13
#Sta/Elev= 30
  3773.4   43.66    3910   38.13  4008.2   36.16  4122.7    34.3    4221   34.89
  4273.2   34.59  4335.5   33.44  4363.8   31.39  4426.7   29.44  4457.1   26.35
  4487.5   25.85  4717.5   26.35  4822.1   27.52  4882.6   26.37  4978.9   26.02
  4981.6   25.23  4982.6   23.23  5017.4   23.23  5018.4   25.23  5124.4   25.67
  5174.3   26.84  5230.6   26.59  5286.9   27.27    5365   26.55    5470   26.78
  5484.5   26.74  5568.3   32.77  5652.7   35.88  5818.9   39.17  5855.9   39.18
#Mann= 4 ,-1,0
  3773.4     .15       0  4981.6     .05       0  5018.4     .15       0
    5470      .1       0
Bank Sta=4981.6,5018.4
XS Rating Curve= 0 ,0
Exp/Cntr=0.3,0.1

Type RM Length L Ch R = 1 ,20457   ,627,627,627
BEGIN DESCRIPTION:
Maple Swamp 30.0
END DESCRIPTION:
XS GIS Cut Line= 3
      2610033.01       767799.45      2609031.18       767916.14
      2608190.56       768035.16
#Sta/Elev= 30
  3991.4   39.22  4070.2   36.55  4182.8   34.39  4326.7   26.01  4356.9   26.43
  4417.3    25.4    4450   25.85  4477.7   25.09  4628.7   25.13  4658.9   25.75
  4689.1   25.45  4779.7   26.27  4840.1   24.74  4960.9   25.08  4981.6   24.56
  4982.6   22.56  5017.4   22.56  5018.4   24.56  5172.5   25.65  5278.7   24.68
    5385   25.92  5448.1   25.57  5464.5   26.11  5506.2      31  5536.5   32.62
  5566.8    35.3  5644.5   38.46  5748.6   38.82  5778.9   38.26    5849   38.29
#Mann= 3 ,-1,0
  3991.4     .15       0  4981.6     .05       0  5018.4     .15       0
Bank Sta=4981.6,5018.4
XS Rating Curve= 0 ,0
Exp/Cntr=0.3,0.1

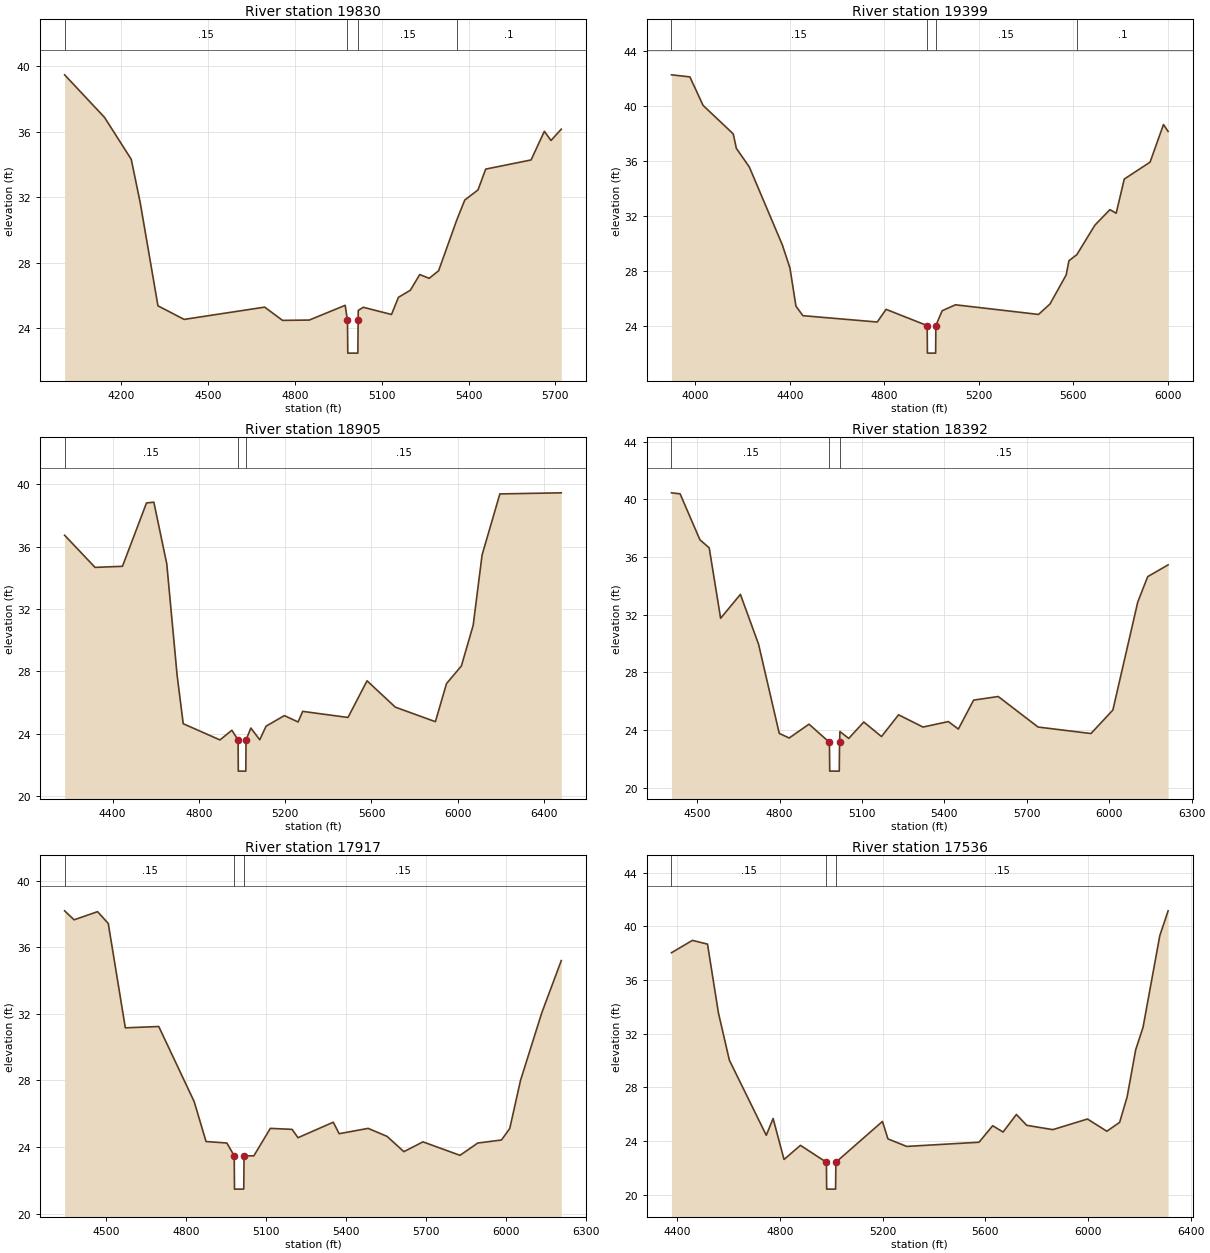
Type RM Length L Ch R = 1 ,19830   ,431,431,431
BEGIN DESCRIPTION:
Maple Swamp 29.0
END DESCRIPTION:
XS GIS Cut Line= 3
      2609684.52       767157.12      2608713.26       767376.83
      2608049.17       767655.77
#Sta/Elev= 30
  4004.2   39.49  4142.1   36.89  4234.4   34.33  4265.2    31.7  4326.7   25.38
  4417.1   24.55  4695.4    25.3  4757.3   24.49  4849.6   24.51  4973.6   25.41
  4981.6   24.49  4982.6   22.49  5017.4   22.49  5018.4   24.49  5018.9    25.1
  5036.1   25.29  5133.7   24.85  5157.7    25.9  5198.8   26.33  5231.3   27.29
  5263.8   27.06  5296.4   27.52    5360   30.66  5386.8   31.84  5432.6   32.46
  5459.1   33.73    5616   34.29  5661.8   36.04  5684.7   35.48  5720.3   36.17
#Mann= 4 ,-1,0
  4004.2     .15       0  4981.6     .05       0  5018.4     .15       0
    5360      .1       0
Bank Sta=4981.6,5018.4
XS Rating Curve= 0 ,0
Exp/Cntr=0.3,0.1

Type RM Length L Ch R = 1 ,19399   ,494,494,494
BEGIN DESCRIPTION:
Maple Swamp 28.0
END DESCRIPTION:
XS GIS Cut Line= 3
      2609604.06       766374.34      2608666.04       766950.23
       2607915.2       767612.83
#Sta/Elev= 30
  3899.3   42.24  3977.3   42.09  4033.1   40.02  4160.8   37.95    4174    36.9
  4228.8   35.55  4368.8   29.88  4400.8   28.21  4426.2   25.44  4455.6   24.75
  4770.2   24.29  4807.6   25.21  4981.6   24.03  4982.6   22.03  5017.4   22.03
  5018.4   24.03    5045   25.11  5101.4   25.54    5453   24.84  5501.5    25.6
    5570   27.71  5581.6   28.74    5615   29.18  5691.3   31.32  5755.1   32.45
  5781.6   32.19  5815.8   34.67  5925.1    35.9  5981.7   38.63  6001.4   38.13
#Mann= 4 ,-1,0
  3899.3     .15       0  4981.6     .05       0  5018.4     .15       0
    5615      .1       0
Bank Sta=4981.6,5018.4
XS Rating Curve= 0 ,0
Exp/Cntr=0.3,0.1

Type RM Length L Ch R = 1 ,18905   ,513,513,513
BEGIN DESCRIPTION:
Maple Swamp 27.0
END DESCRIPTION:
XS GIS Cut Line= 3
      2609164.39       766133.07      2608439.67       766522.45
       2607362.9       767537.82
#Sta/Elev= 30
  4177.3   36.73  4318.5   34.67  4445.5   34.74  4556.9    38.8    4591   38.85
  4650.9    34.9    4699   27.74  4727.2   24.65  4897.5   23.61  4952.6   24.23
  4981.6   23.61  4982.6   21.61  5017.4   21.61  5018.4   23.61  5040.8   24.37
    5082   23.62  5111.2   24.49  5196.1   25.17  5259.8   24.76    5281   25.44
  5491.1   25.05  5579.5    27.4  5710.7   25.71  5896.4   24.78  5947.9   27.22
  6016.8   28.35  6071.6   30.96  6112.9   35.47  6195.3   39.38    6480   39.45
#Mann= 3 ,-1,0
  4177.3     .15       0  4981.6     .05       0  5018.4     .15       0
Bank Sta=4981.6,5018.4
XS Rating Curve= 0 ,0
Exp/Cntr=0.3,0.1

Type RM Length L Ch R = 1 ,18392   ,475,475,475
BEGIN DESCRIPTION:
Maple Swamp 26.0
END DESCRIPTION:
XS GIS Cut Line= 3
      2608364.58       765723.91      2608034.62       766217.12
      2607352.17        767221.5
#Sta/Elev= 30
  4406.6   40.46    4438   40.39  4510.2    37.2    4544   36.64  4585.5   31.75
  4657.5   33.41  4723.6   29.95  4798.9   23.76    4835   23.44  4907.2    24.4
  4981.6   23.14  4982.6   21.14  5017.4   21.14  5018.4   23.14  5019.8   23.89
  5051.8   23.41  5106.6   24.55    5171   23.54  5233.2   25.05  5322.1    24.2
  5414.5   24.58  5450.8   24.06  5506.4   26.07  5595.9   26.32    5741    24.2
  5933.5   23.75  6013.2   25.38  6103.7   32.87  6139.9   34.64  6214.3   35.46
#Mann= 3 ,-1,0
  4406.6     .15       0  4981.6     .05       0  5018.4     .15       0
Bank Sta=4981.6,5018.4
XS Rating Curve= 0 ,0
Exp/Cntr=0.3,0.1

Type RM Length L Ch R = 1 ,17917   ,381,381,381
BEGIN DESCRIPTION:
Maple Swamp 25.0
END DESCRIPTION:
XS GIS Cut Line= 3
       2608033.1       765473.06      2607626.74       765986.51
       2607041.2       767044.03
#Sta/Elev= 30
  4345.2   38.19  4380.8   37.65  4468.8   38.14    4509   37.43    4573   31.16
  4698.4   31.24  4831.3   26.73  4875.9   24.33  4954.1   24.24  4981.6   23.47
  4982.6   21.47  5017.4   21.47  5018.4   23.47  5055.2   23.47  5117.1   25.12
  5198.8   25.06  5220.9   24.56  5353.3   25.49  5375.4    24.8  5484.1   25.12
  5555.1   24.64  5618.2   23.72  5689.8   24.31  5828.8    23.5  5895.6   24.24
  5984.2   24.42  6015.4   25.11    6056   28.01  6135.6   32.06  6208.8    35.2
#Mann= 3 ,-1,0
  4345.2     .15       0  4981.6     .05       0  5018.4     .15       0
Bank Sta=4981.6,5018.4
XS Rating Curve= 0 ,0
Exp/Cntr=0.3,0.1

Type RM Length L Ch R = 1 ,17536   ,306,306,306
BEGIN DESCRIPTION:
Maple Swamp 24.0
END DESCRIPTION:
XS GIS Cut Line= 3
      2607834.74       765306.82      2607363.54       765712.08
      2606354.95        766550.7
#Sta/Elev= 30
  4378.5   38.03  4460.1   38.95  4518.8   38.67  4561.4   33.54  4603.9   30.03
  4747.6   24.44  4774.1   25.69  4816.7   22.64  4880.5   23.69  4981.6   22.43
  4982.6   20.43  5017.4   20.43  5018.4   22.43  5199.7   25.47  5221.2   24.17
  5293.9   23.61  5575.5   23.92  5628.9   25.15  5669.3   24.68  5721.1   25.99
  5761.3   25.18    5863   24.86  5997.8   25.65  6073.3   24.74    6123    25.4
  6152.3   27.31  6185.5   30.81  6214.1   32.48  6279.3    39.3  6311.7   41.15
#Mann= 3 ,-1,0
  4378.5     .15       0  4981.6     .05       0  5018.4     .15       0
Bank Sta=4981.6,5018.4
XS Rating Curve= 0 ,0
Exp/Cntr=0.3,0.1

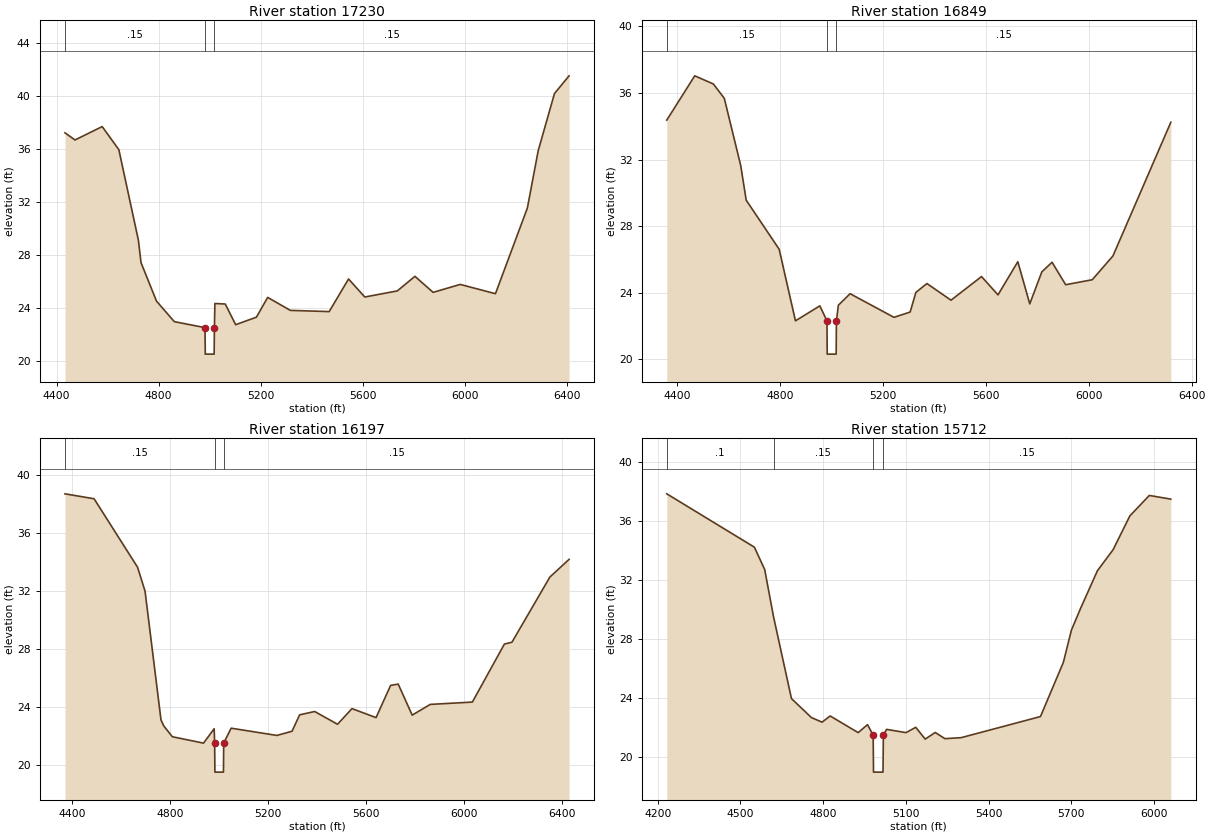
Type RM Length L Ch R = 1 ,17230   ,381,381,381
BEGIN DESCRIPTION:
Maple Swamp 23.0
END DESCRIPTION:
XS GIS Cut Line= 3
      2607663.14       765162.08      2607183.76       765465.07
      2606231.62       766502.46
#Sta/Elev= 30
  4432.9   37.25  4472.1   36.71  4578.6   37.72  4643.9   35.98  4720.5   29.15
  4730.9   27.45  4791.5   24.55  4861.3      23  4981.6   22.55  4982.6   20.55
  5017.4   20.55  5018.4   22.55  5020.3   24.37    5061   24.33  5101.7   22.77
  5183.1   23.34  5227.1   24.83  5316.1   23.85  5468.2   23.76    5544   26.22
  5607.7   24.86  5735.1   25.32  5804.2   26.42  5875.4   25.21  5981.6   25.81
  6119.7   25.11  6244.7   31.57  6287.2    35.9  6350.9   40.21  6408.1   41.55
#Mann= 3 ,-1,0
  4432.9     .15       0  4981.6     .05       0  5018.4     .15       0
Bank Sta=4981.6,5018.4
XS Rating Curve= 0 ,0
Exp/Cntr=0.3,0.1

Type RM Length L Ch R = 1 ,16849   ,652,652,652
BEGIN DESCRIPTION:
Maple Swamp 22.0
END DESCRIPTION:
XS GIS Cut Line= 3
      2607310.11       764724.83      2606896.75       765215.26
      2606046.31       766223.49
#Sta/Elev= 30
  4358.6   34.37  4467.4   37.03  4539.8   36.54  4582.3   35.68  4646.2   31.64
  4667.5   29.56  4795.8   26.61  4859.1   22.31  4953.9   23.21  4981.6   22.31
  4982.6   20.31  5017.4   20.31  5018.4   22.31    5026   23.25  5071.6   23.94
  5242.3   22.52  5305.2   22.84  5327.5   24.02  5370.5   24.55  5464.1   23.55
  5582.7   24.97  5646.8   23.87  5723.9   25.86  5770.4   23.33  5817.2   25.25
    5857   25.83    5910   24.48  6013.5   24.78  6093.9   26.21    6319   34.24
#Mann= 3 ,-1,0
  4358.6     .15       0  4981.6     .05       0  5018.4     .15       0
Bank Sta=4981.6,5018.4
XS Rating Curve= 0 ,0
Exp/Cntr=0.3,0.1

Type RM Length L Ch R = 1 ,16197   ,485,485,485
BEGIN DESCRIPTION:
Maple Swamp 21.0
END DESCRIPTION:
XS GIS Cut Line= 3
      2606691.25       764329.67      2606353.35       764861.62
      2605994.11       766245.87
#Sta/Elev= 30
  4369.8   38.68  4488.7   38.34  4666.4   33.62    4697   31.97  4762.2   23.09
    4773   22.69  4808.5   21.93    4936   21.49  4979.5   22.48  4981.5   21.49
  4982.5   19.49  5017.5   19.49  5018.5   21.49  5048.9   22.52  5235.9   22.02
  5297.9   22.31  5328.9   23.44  5390.3   23.67  5483.9   22.79  5542.8   23.87
  5641.2   23.25  5700.8   25.47  5731.8   25.56  5788.9   23.42  5862.7   24.16
  6034.9   24.32  6165.8   28.32  6196.8   28.45  6351.7   32.94  6430.1   34.16
#Mann= 3 ,-1,0
  4369.8     .15       0  4981.5     .05       0  5018.5     .15       0
Bank Sta=4981.5,5018.5
XS Rating Curve= 0 ,0
Exp/Cntr=0.3,0.1

Type RM Length L Ch R = 1 ,15712   ,307,307,307
BEGIN DESCRIPTION:
Maple Swamp 20.0
END DESCRIPTION:
XS GIS Cut Line= 3
      2606594.28        764313.3       2605915.6       764671.07
      2605013.64       765230.37
#Sta/Elev= 30
  4232.8   37.83  4550.7   34.21  4588.1   32.69    4620    29.5  4685.1   23.94
  4757.6   22.65  4796.1   22.34  4825.5   22.76  4927.2   21.63  4961.1   22.17
  4981.5   21.45  4982.8   18.95  5017.2   18.95  5018.5   21.45  5030.1   21.85
  5100.7   21.63    5136   21.99  5170.3   21.19  5206.6   21.64  5241.9   21.22
  5301.1   21.29  5588.4   22.72  5671.5    26.4  5700.8   28.59    5733   30.02
  5794.9   32.61  5851.9   34.04  5912.6   36.33  5983.2   37.72  6061.3   37.47
#Mann= 4 ,-1,0
  4232.8      .1       0    4620     .15       0  4981.5     .05       0
  5018.5     .15       0
Bank Sta=4981.5,5018.5
XS Rating Curve= 0 ,0
Exp/Cntr=0.5,0.3