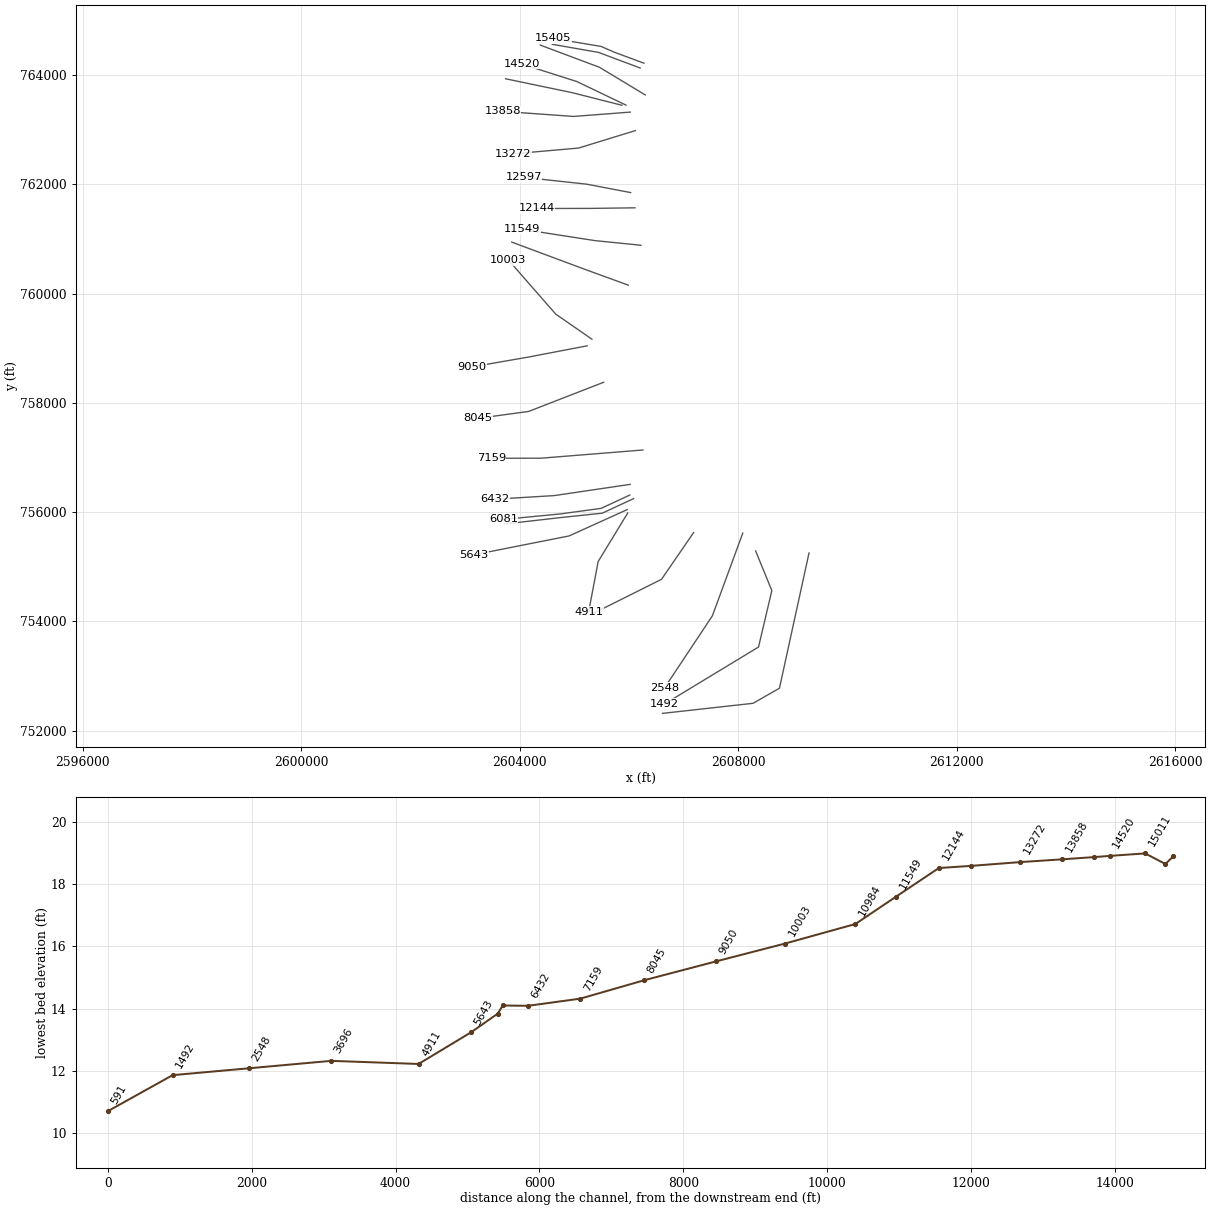
HEC-RAS study MapleSwamp.prj: S-26-65 over Maple Swamp

--- MapleSwamp.g01 (geometry) --- (continued)

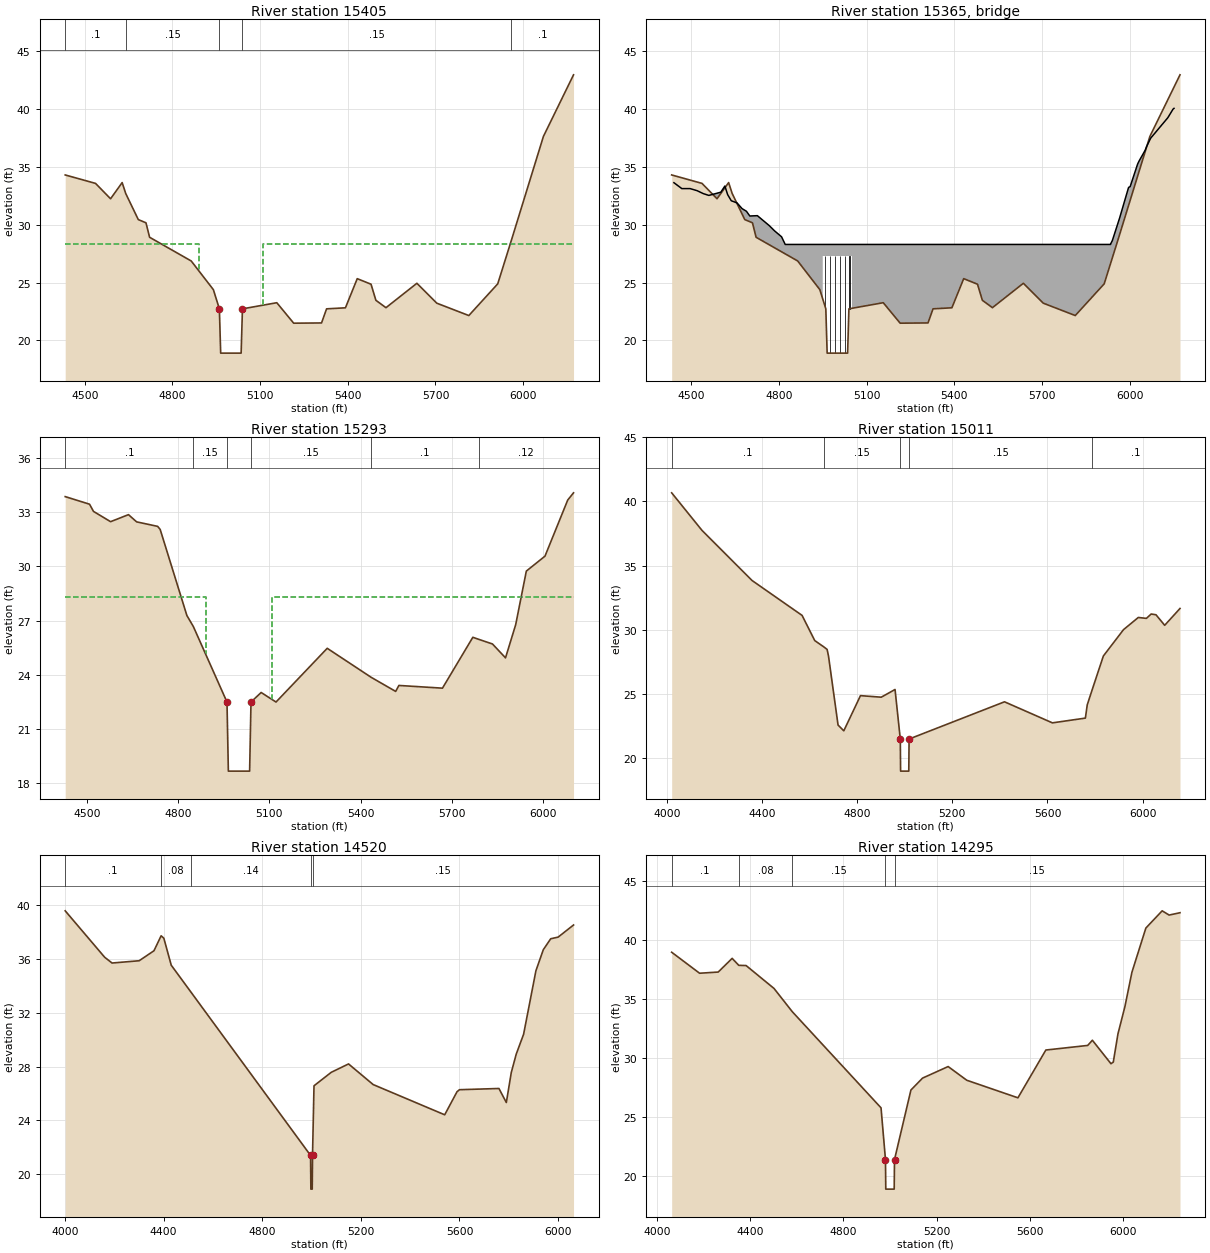
Type RM Length L Ch R = 1 ,15405   ,112,112,112
BEGIN DESCRIPTION:
Maple Swamp (HWY-65) US
END DESCRIPTION:
XS GIS Cut Line= 4
      2606275.54       764220.47      2605743.72       764417.08
      2605492.18         764527.      2604606.64        764675.4
#Sta/Elev= 30
    4433   34.31  4536.8   33.58  4588.2   32.25  4627.9   33.65    4640   32.71
  4683.1   30.45  4709.4   30.17  4721.8   28.92  4864.2   26.87    4940   24.39
  4960.5   22.73    4965    18.9    5035    18.9  5039.5   22.73    5157   23.26
  5214.8   21.49  5310.1   21.51  5327.4   22.73  5391.9   22.82  5432.3   25.34
  5479.5   24.86  5496.1   23.47  5530.6   22.83  5636.4   24.94  5704.5   23.22
  5814.1   22.15    5913   24.89    5960   28.68  6069.3   37.64  6172.4   42.97
#Mann= 5 ,-1,0
    4433      .1       0    4640     .15       0  4960.5     .05       0
  5039.5     .15       0    5960      .1       0
#XS Ineff= 2 , 0
       0    4890    28.3    5110       0    28.3
Permanent Ineff=
       F       F
Bank Sta=4960.5,5039.5
XS Rating Curve= 0 ,0
Exp/Cntr=0.5,0.3

Type RM Length L Ch R = 3 ,15365   ,,,
BEGIN DESCRIPTION:
Maple Swamp (HWY-65) TOR
Structure ID: LDS_MPS_02
Approximate Survey Structure
END DESCRIPTION:
Bridge Culvert--1,0,-1,-1, 0
Deck Dist Width WeirC Skew NumUp NumDn MinLoCord MaxHiCord MaxSubmerge Is_Ogee
26,28,3,0, 38, 38, , , 0.95, 0, 1,1,,
  4440.7  4467.7  4495.9  4520.1  4540.7  4560.2  4601.2    4615  4624.5  4636.9
  4656.7  4673.8  4688.8  4700.4  4726.2  4766.9  4785.3  4809.1  4821.5    4950
    4950    5050    5050  5934.9  5935.3  5940.8  5965.8  5996.3  5998.3  6001.8
  6027.2  6031.8  6053.3  6057.3    6072  6130.7  6148.8  6151.9
   33.64   33.13   33.13   32.95    32.7   32.54   32.82   33.35   32.61   32.08
   31.89    31.4   31.17   30.76   30.79   29.93   29.47   28.96    28.3    28.3
    28.3    28.3    28.3    28.3   28.36   28.63   30.59   33.22   33.26    33.3
   35.24   35.49   36.45   36.72   37.49   39.26   40.01   40.07
   -1.16   -1.16   -1.16   -1.16   -1.16   -1.16   -1.16   -1.16   -1.16   -1.16
   -1.16   -1.16   -1.16   -1.16   -1.16   -1.16   -1.16   -1.16   -1.16   -1.16
    27.3    27.3   -1.16   -1.16   -1.16   -1.16   -1.16   -1.16   -1.16   -1.16
   -1.16   -1.16   -1.16   -1.16   -1.16   -1.16   -1.16   -1.16
  4440.7  4467.7  4495.9  4520.1  4540.7  4560.2  4601.2    4615  4624.5  4636.9
  4656.7  4673.8  4688.8  4700.4  4726.2  4766.9  4785.3  4809.1  4821.5    4950
    4950    5050    5050  5934.9  5935.3  5940.8  5965.8  5996.3  5998.3  6001.8
  6027.2  6031.8  6053.3  6057.3    6072  6130.7  6148.8  6151.9
   33.64   33.13   33.13   32.95    32.7   32.54   32.82   33.35   32.61   32.08
   31.89    31.4   31.17   30.76   30.79   29.93   29.47   28.96    28.3    28.3
    28.3    28.3    28.3    28.3   28.36   28.63   30.59   33.22   33.26    33.3
   35.24   35.49   36.45   36.72   37.49   39.26   40.01   40.07
   -1.16   -1.16   -1.16   -1.16   -1.16   -1.16   -1.16   -1.16   -1.16   -1.16
   -1.16   -1.16   -1.16   -1.16   -1.16   -1.16   -1.16   -1.16   -1.16   -1.16
    27.3    27.3   -1.16   -1.16   -1.16   -1.16   -1.16   -1.16   -1.16   -1.16
   -1.16   -1.16   -1.16   -1.16   -1.16   -1.16   -1.16   -1.16
Pier Skew, UpSta & Num, DnSta & Num=  ,4958.3, 2 ,4958.3, 2 , 0 , 0 , 0 ,0,0
       1       1
   21.59    27.3
       1       1
   21.34    27.3
Pier Skew, UpSta & Num, DnSta & Num=  ,4975, 2 ,4975, 2 , 0 , 0 , 0 ,0,0
       1       1
    15.9    27.3
       1       1
   15.65    27.3
Pier Skew, UpSta & Num, DnSta & Num=  ,4991.7, 2 ,4991.7, 2 , 0 , 0 , 0 ,0,0
       1       1
    15.9    27.3
       1       1
   15.65    27.3
Pier Skew, UpSta & Num, DnSta & Num=  ,5008.3, 2 ,5008.3, 2 , 0 , 0 , 0 ,0,0
       1       1
    15.9    27.3
       1       1
   15.65    27.3
Pier Skew, UpSta & Num, DnSta & Num=  ,5025, 2 ,5025, 2 , 0 , 0 , 0 ,0,0
       1       1
    15.9    27.3
       1       1
   15.65    27.3
Pier Skew, UpSta & Num, DnSta & Num=  ,5041.7, 2 ,5041.7, 2 , 0 , 0 , 0 ,0,0
       1       1
   21.59    27.3
       1       1
   21.34    27.3
Abutment Skew #Up #Dn= , 2 , 2
    4950    4965
    27.3    15.9
    4950    4965
    27.3   15.65
Abutment Skew #Up #Dn= , 2 , 2
    5035    5050
    15.9    27.3
    5035    5050
   15.65    27.3
BR Coef= 1 , 1 , 0 ,1.25, 0 ,,,0.8,0,2,0,
WSPro=,,,, 1 ,,,, 0 ,,,, 0 ,,,,-1 ,-1 ,-1 , 0 , 0 , 0 , 0 , 0
BC Design=,, 0 ,, 0 ,,,,,,
BC HTab HWMax=42.97
BC Use User HTab Curves=0
BC User HTab FreeFlow(D)= 0

Type RM Length L Ch R = 1 ,15293   ,282,282,282
BEGIN DESCRIPTION:
Maple Swamp (HWY-65) DS
END DESCRIPTION:
XS GIS Cut Line= 4
      2606204.98       764132.89      2605669.35       764333.03
      2605445.96       764417.53      2604596.97       764565.92
#Sta/Elev= 30
  4428.2   33.87  4508.2   33.45  4521.3   33.05  4577.5   32.48  4636.4   32.87
  4663.2   32.47  4732.4   32.22  4740.7   32.05  4828.5   27.28    4850   26.66
  4960.5   22.48    4965   18.65    5035   18.65  5039.5   22.48  5072.9   23.01
  5121.8   22.48  5290.3   25.46    5435   23.85  5515.5   23.07  5526.1    23.4
  5669.5   23.25  5769.4   26.07    5790   25.95    5834    25.7  5876.9   24.93
  5910.4   26.77  5945.4   29.74  6006.8   30.57  6081.6   33.68  6100.7   34.08
#Mann= 6 ,-1,0
  4428.2      .1       0    4850     .15       0  4960.5     .05       0
  5039.5     .15       0    5435      .1       0    5790     .12       0
#XS Ineff= 2 , 0
       0    4890    28.3    5110       0    28.3
Permanent Ineff=
       F       F
Bank Sta=4960.5,5039.5
XS Rating Curve= 0 ,0
Exp/Cntr=0.5,0.3

Type RM Length L Ch R = 1 ,15011   ,491,491,491
BEGIN DESCRIPTION:
Maple Swamp 19.0
END DESCRIPTION:
XS GIS Cut Line= 3
       2606299.2       763639.26      2605460.96       764145.41
      2604377.67       764551.49
#Sta/Elev= 30
  4020.8   40.67  4148.4   37.74  4358.6   33.84  4568.9   31.12    4622   29.16
    4660   28.67    4674   28.47    4680   27.94    4720   22.58  4744.1   22.13
  4814.2   24.87  4901.6   24.75  4959.5   25.35  4981.5   21.49  4982.8   18.99
  5017.2   18.99  5018.5   21.49  5419.4   24.39  5620.7   22.75  5759.3   23.12
  5767.1   24.15    5787   25.28  5834.9   27.96  5919.5   30.01  5981.7   30.96
  6015.6   30.89  6035.9   31.23    6056   31.17  6092.6   30.35  6156.9   31.66
#Mann= 5 ,-1,0
  4020.8      .1       0    4660     .15       0  4981.5    .052       0
  5018.5     .15       0    5787      .1       0
Bank Sta=4981.5,5018.5
XS Rating Curve= 0 ,0
Exp/Cntr=0.3,0.1

Type RM Length L Ch R = 1 ,14520   ,225,225,225
BEGIN DESCRIPTION:
Maple Swamp 18.0
END DESCRIPTION:
XS GIS Cut Line= 3
      2605946.63       763453.24      2605045.68       763884.86
      2604033.18       764206.97
#Sta/Elev= 30
    4001   39.54    4161    36.1    4191   35.67    4301   35.84    4361   36.58
    4390   37.69    4401   37.51    4431   35.51    4510   33.54    4996   21.41
  4997.3   18.91  5002.8   18.91    5004   21.41    5010   26.57    5080   27.57
    5150   28.19    5250   26.66    5540   24.42    5590   26.13    5600   26.28
    5760   26.37    5790   25.33    5810   27.55    5830   28.91    5860   30.39
    5910    35.1    5940   36.66    5970   37.47    6000   37.59  6062.5   38.49
#Mann= 5 ,-1,0
    4001      .1       0    4390     .08       0    4510     .14       0
    4996    .052       0    5004     .15       0
Bank Sta=4996,5004
XS Rating Curve= 0 ,0
Exp/Cntr=0.3,0.1

Type RM Length L Ch R = 1 ,14295   ,437,437,437
BEGIN DESCRIPTION:
Maple Swamp 17.0
END DESCRIPTION:
XS GIS Cut Line= 3
      2605872.17       763450.02      2604962.43        763680.6
      2603742.02       763935.25
#Sta/Elev= 30
  4061.5   38.95  4181.5   37.17  4261.5   37.27  4321.5   38.43    4350   37.84
  4381.5   37.82  4501.5   35.88    4580   33.91  4961.5   25.76  4980.6   21.37
  4981.9   18.87  5018.1   18.87  5019.4   21.37    5090   27.27    5140   28.28
    5250   29.26    5330    28.1    5550   26.61    5670   30.66    5850   31.05
    5870   31.49    5950    29.5    5960   29.64    5980   32.03    6010   34.35
    6040   37.25    6100      41    6170   42.46    6200    42.1  6246.7    42.3
#Mann= 5 ,-1,0
  4061.5      .1       0    4350     .08       0    4580     .15       0
  4980.6    .052       0  5019.4     .15       0
Bank Sta=4980.6,5019.4
XS Rating Curve= 0 ,0
Exp/Cntr=0.3,0.1

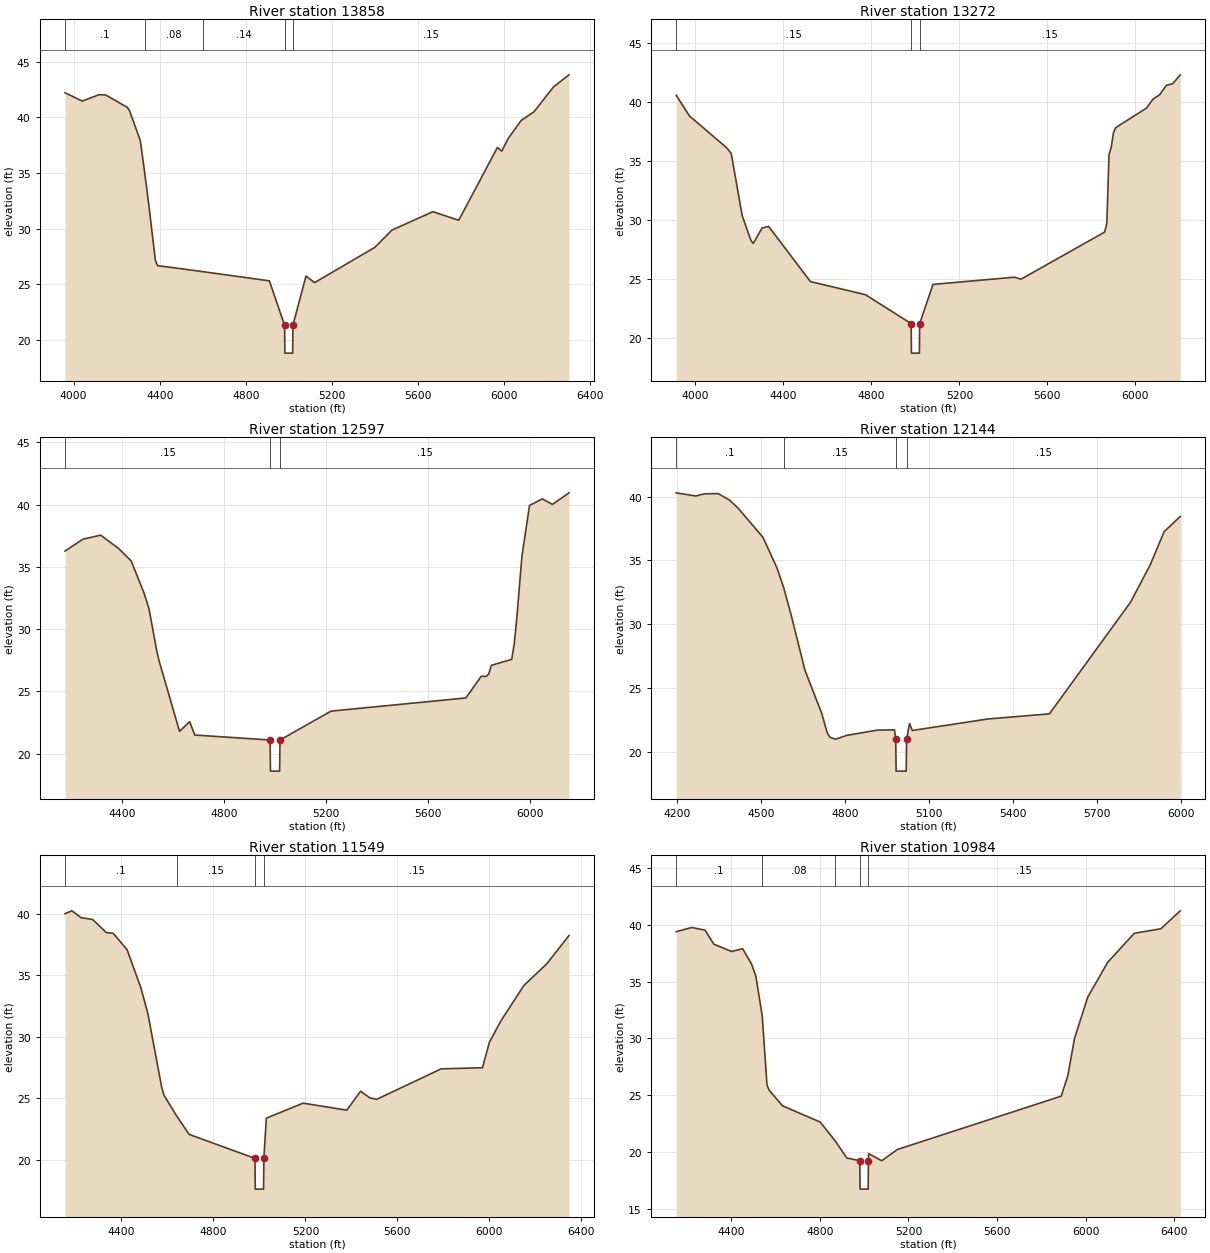
Type RM Length L Ch R = 1 ,13858   ,586,586,586
BEGIN DESCRIPTION:
Maple Swamp 16.0
END DESCRIPTION:
XS GIS Cut Line= 3
      2606024.98         763325.      2604987.82       763245.56
      2603688.63       763338.41
#Sta/Elev= 30
  3959.8   42.22  4039.8   41.47  4119.8   42.05  4149.8   42.01  4249.8    40.9
  4259.8    40.6  4309.8   37.93    4330   35.07  4349.8   32.09  4379.8   27.15
  4389.8   26.67    4600   26.13  4909.8    25.3  4980.6    21.3  4981.9    18.8
  5018.1    18.8  5019.4    21.3    5080   25.73    5120   25.14    5400   28.31
    5480   29.87    5670   31.52    5790   30.75    5970    37.3    5990   36.96
    6020    38.1    6080   39.72    6140   40.51    6230   42.73  6302.5   43.83
#Mann= 5 ,-1,0
  3959.8      .1       0    4330     .08       0    4600     .14       0
  4980.6    .052       0  5019.4     .15       0
Bank Sta=4980.6,5019.4
XS Rating Curve= 0 ,0
Exp/Cntr=0.3,0.1

Type RM Length L Ch R = 1 ,13272   ,675,675,675
BEGIN DESCRIPTION:
Maple Swamp 15.0
END DESCRIPTION:
XS GIS Cut Line= 3
      2606117.24       762986.01      2605078.07       762666.77
      2603879.09       762561.43
#Sta/Elev= 30
  3912.9   40.55  3972.9    38.8  4142.9   36.09  4162.9   35.62  4212.9   30.34
  4252.9   28.24  4262.9      28  4302.9    29.3  4332.9   29.44  4522.9   24.77
  4772.9   23.66  4980.6   21.21  4981.9   18.71  5018.1   18.71  5019.4   21.21
    5080   24.53    5450   25.14    5480   24.97    5860   28.96    5870   29.68
    5880   35.51    5890   36.14    5900   37.36    5910    37.8    6050   39.46
    6080   40.22    6110   40.59    6140   41.38    6170   41.54  6203.6   42.28
#Mann= 3 ,-1,0
  3912.9     .15       0  4980.6    .052       0  5019.4     .15       0
Bank Sta=4980.6,5019.4
XS Rating Curve= 0 ,0
Exp/Cntr=0.3,0.1

Type RM Length L Ch R = 1 ,12597   ,453,453,453
BEGIN DESCRIPTION:
Maple Swamp 14.0
END DESCRIPTION:
XS GIS Cut Line= 3
       2606032.3       761851.79      2605221.51       762006.37
      2604073.23       762130.79
#Sta/Elev= 30
  4174.6   36.27  4244.6   37.22  4314.6   37.55  4384.6   36.49  4434.6   35.48
  4484.6   32.93  4504.6   31.64  4534.6   28.32  4544.6   27.43  4624.6   21.79
  4664.6   22.56  4684.6   21.49  4980.6   21.09  4981.9   18.59  5018.1   18.59
  5019.4   21.09    5220   23.41    5750   24.47    5810   26.21    5830    26.2
    5840   26.41    5850   27.09    5930   27.57    5940   28.82    5950   30.91
    5970   35.83    6000   39.94    6050   40.46    6090   40.02    6155   40.95
#Mann= 3 ,-1,0
  4174.6     .15       0  4980.6    .052       0  5019.4     .15       0
Bank Sta=4980.6,5019.4
XS Rating Curve= 0 ,0
Exp/Cntr=0.3,0.1

Type RM Length L Ch R = 1 ,12144   ,595,595,595
BEGIN DESCRIPTION:
Maple Swamp 13.0
END DESCRIPTION:
XS GIS Cut Line= 3
      2606111.14       761572.78      2605307.21       761562.06
      2604309.81       761560.65
#Sta/Elev= 30
    4196   40.29    4266   40.04    4296   40.21    4346   40.23    4386   39.73
    4416   39.12    4506   36.81    4556   34.42    4580   32.88    4606    30.8
    4656   26.42    4716   23.04    4736   21.49    4746   21.16    4766   21.02
    4806   21.32    4916   21.73    4976   21.75  4980.6   21.02  4981.9   18.52
  5018.1   18.52  5019.4   21.02    5030   22.24    5040    21.7    5310    22.6
    5530      23    5820   31.74    5890   34.65    5940   37.25  5997.4   38.44
#Mann= 4 ,-1,0
    4196      .1       0    4580     .15       0  4980.6    .052       0
  5019.4     .15       0
Bank Sta=4980.6,5019.4
XS Rating Curve= 0 ,0
Exp/Cntr=0.3,0.1

Type RM Length L Ch R = 1 ,11549   ,565,565,565
BEGIN DESCRIPTION:
Maple Swamp 12.0
END DESCRIPTION:
XS GIS Cut Line= 3
      2606220.38       760887.39      2605379.14       760972.13
      2604048.95       761178.53
#Sta/Elev= 30
  4154.5      40  4184.5   40.23  4224.5   39.67  4274.5   39.53  4334.5   38.46
  4364.5    38.4  4424.5   37.07  4484.5   33.97  4514.5   31.91  4574.5   25.93
  4584.5   25.25    4640   23.55  4694.5   22.05  4980.6    20.1  4981.9    17.6
  5018.1    17.6  5019.4    20.1    5030   23.37    5190   24.59    5380   24.02
    5440   25.56    5480   25.02    5510    24.9    5790   27.38    5970   27.47
    6000   29.54    6050   31.28    6150   34.16    6250   35.93  6346.1   38.22
#Mann= 4 ,-1,0
  4154.5      .1       0    4640     .15       0  4980.6    .052       0
  5019.4     .15       0
Bank Sta=4980.6,5019.4
XS Rating Curve= 0 ,0
Exp/Cntr=0.3,0.1

Type RM Length L Ch R = 1 ,10984   ,981,981,981
BEGIN DESCRIPTION:
Maple Swamp 11.0
END DESCRIPTION:
XS GIS Cut Line= 3
      2605989.85       760156.52      2605192.76        760447.1
      2603854.91       760944.99
#Sta/Elev= 30
  4151.6    39.4  4221.6   39.77  4281.6   39.54  4321.6    38.3  4401.6   37.66
  4451.6    37.9  4491.6   36.56  4511.6   35.45    4540   31.97  4561.6   25.89
  4571.6   25.43  4631.6   24.06  4801.6   22.63    4870   20.96  4921.6   19.47
  4980.4   19.22  4981.7   16.72  5018.3   16.72  5019.6   19.22    5020   19.85
    5080   19.22    5150   20.21    5890   24.91    5920   26.71    5950   29.99
    6010   33.64    6100    36.7    6220   39.26    6340   39.66  6427.5   41.24
#Mann= 5 ,-1,0
  4151.6      .1       0    4540     .08       0    4870     .13       0
  4980.4    .052       0  5019.6     .15       0
Bank Sta=4980.4,5019.6
XS Rating Curve= 0 ,0
Exp/Cntr=0.3,0.1

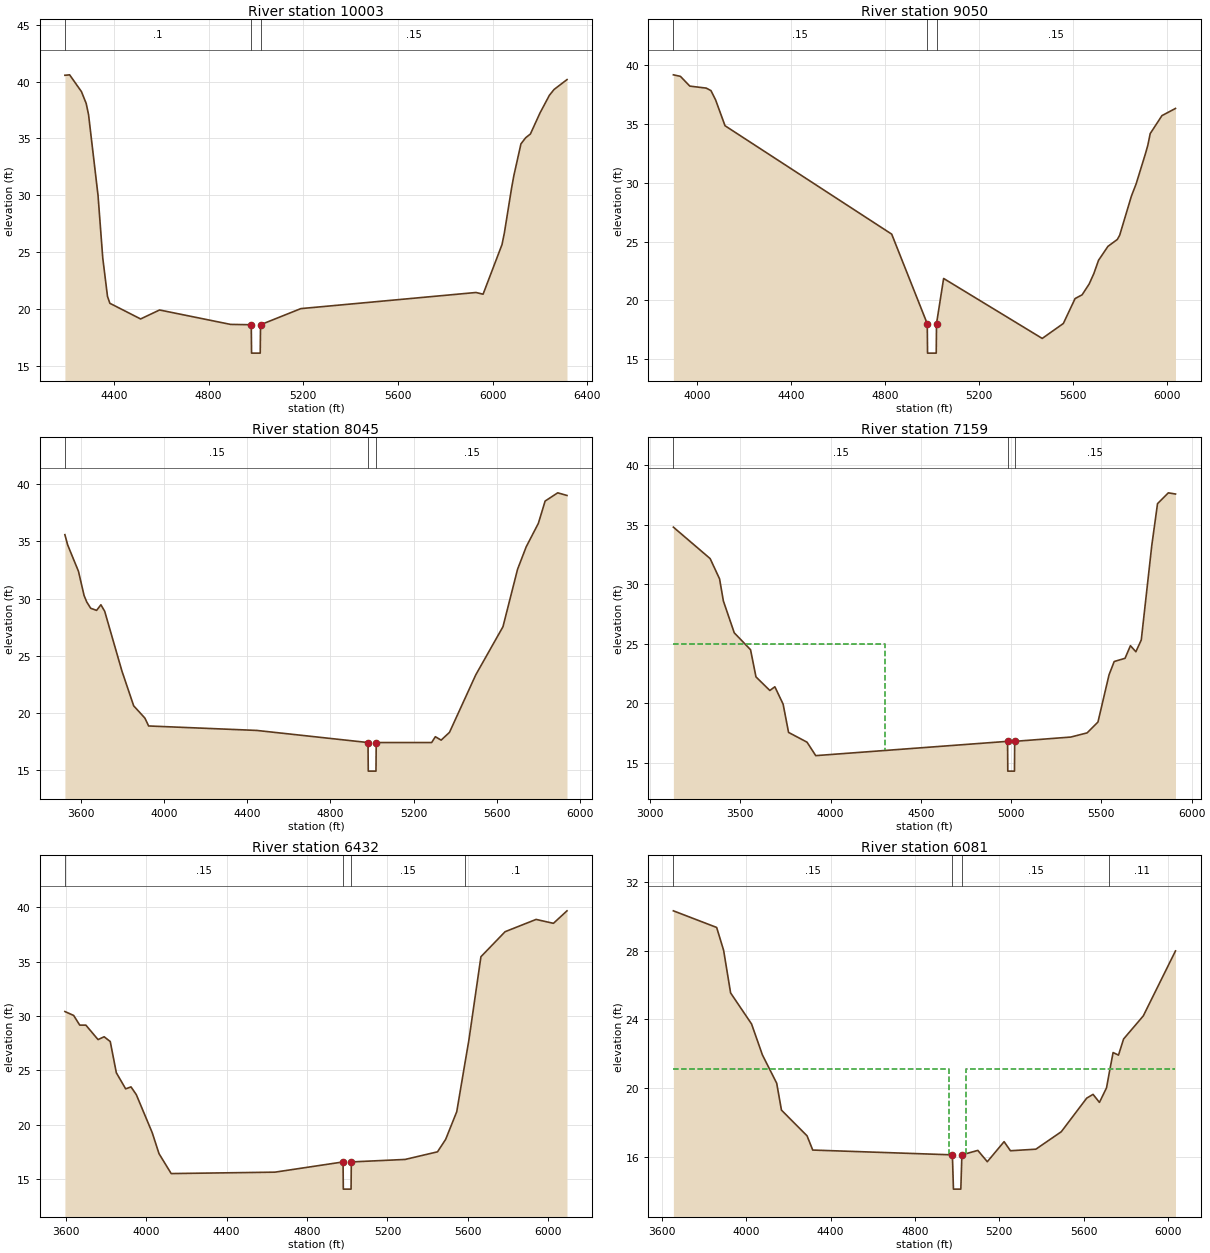
Type RM Length L Ch R = 1 ,10003   ,953,953,953
BEGIN DESCRIPTION:
Maple Swamp 10.0
END DESCRIPTION:
XS GIS Cut Line= 3
      2605322.69       759167.85      2604659.46       759627.79
       2603794.2       760617.49
#Sta/Elev= 30
  4192.9   40.56  4212.9    40.6  4262.9   39.12  4282.9   38.08  4292.9   37.09
  4332.9   29.99  4352.9   24.47  4372.9   21.09  4382.9   20.48  4512.9    19.1
  4592.9   19.89  4892.9   18.62  4980.4   18.59  4981.7   16.09  5018.3   16.09
  5019.6   18.59    5190   20.01    5930   21.43    5960   21.28    6040   25.65
    6050   26.68    6080   30.57    6090   31.72    6120   34.52    6140   35.06
    6160   35.39    6200   37.22    6240   38.79    6260   39.31  6314.6   40.18
#Mann= 3 ,-1,0
  4192.9      .1       0  4980.4    .052       0  5019.6     .15       0
Bank Sta=4980.4,5019.6
XS Rating Curve= 0 ,0
Exp/Cntr=0.3,0.1

Type RM Length L Ch R = 1 ,9050    ,1005,1005,1005
BEGIN DESCRIPTION:
Maple Swamp 9.0
END DESCRIPTION:
XS GIS Cut Line= 3
      2605235.11       759046.19      2604153.55       758839.16
       2603131.1       758661.87
#Sta/Elev= 30
  3898.8   39.19  3928.8   39.06  3968.8   38.23  4038.8   38.06  4058.8   37.85
  4078.8   37.05  4118.8   34.86  4828.8   25.64  4980.3   18.02  4981.5   15.52
  5018.5   15.52  5019.7   18.02    5050   21.87    5470   16.77    5560   18.04
    5610   20.16    5640   20.48    5670    21.4    5690   22.29    5710   23.42
    5750    24.6    5790   25.19    5800   25.55    5850   28.88    5870   29.91
    5910    32.5    5920   33.21    5930   34.19    5980   35.72  6037.7   36.33
#Mann= 3 ,-1,0
  3898.8     .15       0  4980.3    .052       0  5019.7     .15       0
Bank Sta=4980.3,5019.7
XS Rating Curve= 0 ,0
Exp/Cntr=0.3,0.1

Type RM Length L Ch R = 1 ,8045    ,886,886,886
BEGIN DESCRIPTION:
Maple Swamp 8.0
END DESCRIPTION:
XS GIS Cut Line= 3
      2605537.84       758379.27       2604163.1       757844.74
      2603235.94       757719.37
#Sta/Elev= 30
    3525   35.59  3538.2    34.7  3590.1   32.39  3617.1   30.27    3630    29.7
  3649.1   29.15  3677.3   28.97  3697.9   29.46  3716.1   28.89  3798.9   23.66
  3855.3   20.62    3909   19.55    3927   18.86  4445.4   18.47  4980.3   17.41
  4981.5   14.91  5018.5   14.91  5019.7   17.41  5285.7   17.41  5303.6   17.92
  5331.3   17.62  5371.4    18.3  5497.6   23.33  5628.2   27.54  5698.2   32.56
  5739.8   34.53  5798.1   36.58  5830.6   38.53  5891.1   39.25  5935.6   39.02
#Mann= 3 ,-1,0
    3525     .15       0  4980.3    .052       0  5019.7     .15       0
Bank Sta=4980.3,5019.7
XS Rating Curve= 0 ,0
Exp/Cntr=0.3,0.1

Type RM Length L Ch R = 1 ,7159    ,727,727,727
BEGIN DESCRIPTION:
Maple Swamp 7.0
END DESCRIPTION:
XS GIS Cut Line= 3
      2606256.07       757139.43      2604391.01       756989.26
      2603480.51       756988.03
#Sta/Elev= 30
  3128.9    34.8  3332.5   32.16  3384.7   30.46  3405.9    28.6  3466.1   25.93
  3556.4   24.51  3586.5   22.23  3663.2   21.09  3691.1    21.4  3736.9   19.94
    3767   17.57  3869.4   16.75  3917.5   15.62  4980.3   16.82  4981.5   14.32
  5018.5   14.32  5019.7   16.82  5330.4   17.18    5421   17.53    5481   18.44
  5542.5   22.41    5571   23.52    5631   23.79    5661   24.85    5691   24.34
    5721   25.33  5779.2   33.26    5811   36.77    5871   37.68  5910.5   37.58
#Mann= 3 ,-1,0
  3128.9     .15       0  4980.3    .052       0  5019.7     .15       0
#XS Ineff= 2 , 0
       0    4300      25               0
Permanent Ineff=
       F       F
Bank Sta=4980.3,5019.7
XS Rating Curve= 0 ,0
Exp/Cntr=0.3,0.1

Type RM Length L Ch R = 1 ,6432    ,351,351,351
BEGIN DESCRIPTION:
Maple Swamp 6.0
END DESCRIPTION:
XS GIS Cut Line= 3
      2606023.14       756510.18      2604634.05       756304.75
      2603542.66       756238.45
#Sta/Elev= 30
  3595.8   30.42  3639.4   30.06  3669.7   29.17  3700.1   29.17  3760.7   27.84
    3791    28.1  3821.4   27.66  3851.7   24.79  3898.1   23.31  3924.6   23.49
    3951   22.78  4030.2   19.28    4064   17.35  4124.6   15.52  4640.5   15.65
  4979.5   16.59  4980.7   14.09  5019.3   14.09  5020.5   16.59  5288.4   16.82
  5449.2   17.52    5490   18.67    5545   21.21    5585   25.59  5605.2   27.77
  5665.3   35.46  5785.5   37.76  5939.7   38.89  6025.9   38.53  6093.4   39.68
#Mann= 4 ,-1,0
  3595.8     .15       0  4979.5    .052       0  5020.5     .15       0
    5585      .1       0
Bank Sta=4979.5,5020.5
XS Rating Curve= 0 ,0
Exp/Cntr=0.5,0.3

Type RM Length L Ch R = 1 ,6081    ,68,68,68
BEGIN DESCRIPTION:
Maple Swamp (Co Jo Rd) US
END DESCRIPTION:
XS GIS Cut Line= 4
      2606016.01       756314.89      2605491.09       756070.64
      2604731.63       755967.52      2603701.08       755868.37
#Sta/Elev= 30
  3654.6   30.34  3859.8   29.37  3892.9   28.03  3925.9   25.55  4025.2   23.74
  4076.8   21.93  4144.5   20.28  4167.1   18.71  4288.4   17.21  4315.3   16.38
  4977.5    16.1  4982.5    14.1  5017.5    14.1  5022.5    16.1  5098.1   16.36
  5143.1    15.7  5222.6   16.87  5252.8   16.34  5373.3   16.43  5493.9   17.45
  5614.4   19.41  5644.6   19.63  5674.7   19.16  5708.3   20.01    5720    20.8
  5739.5   22.07  5765.1   21.92  5789.2   22.86  5882.7   24.21  6035.3      28
#Mann= 4 ,-1,0
  3654.6     .15       0  4977.5    .052       0  5022.5     .15       0
    5720     .11       0
#XS Ineff= 2 , 0
       0    4960    21.1    5040       0    21.1
Permanent Ineff=
       F       F
Bank Sta=4977.5,5022.5
XS Rating Curve= 0 ,0
Exp/Cntr=0.5,0.3

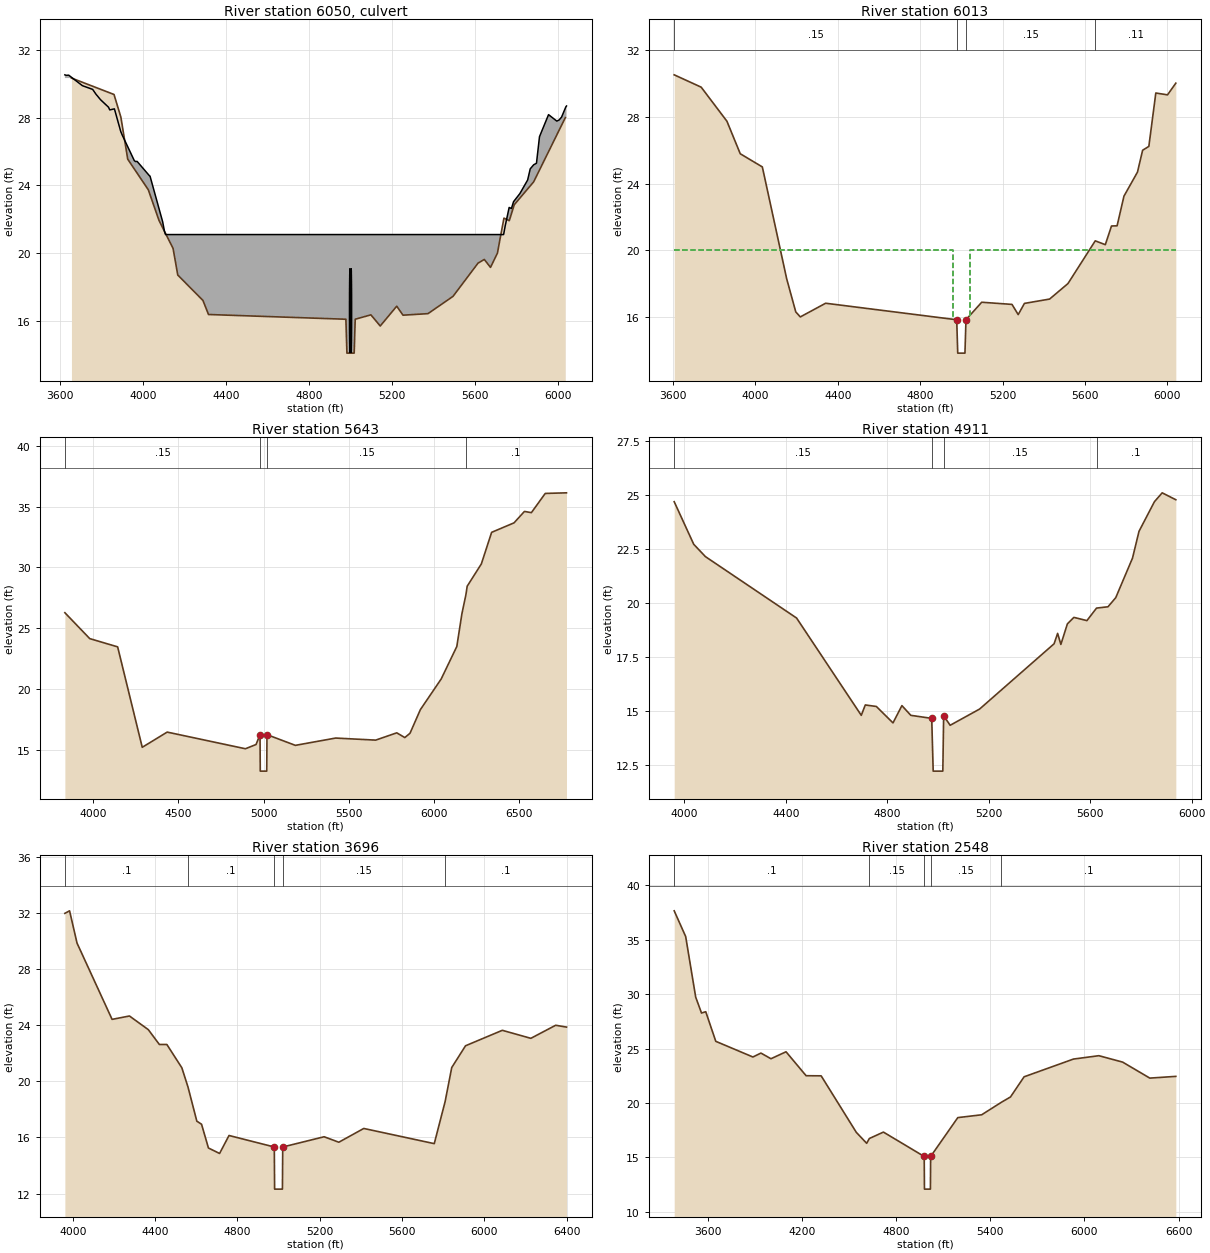
Type RM Length L Ch R = 2 ,6050    ,,,
BEGIN DESCRIPTION:
Maple Swamp (Co Jo Rd) TOR
Structure ID: Maple Swamp_CJR
Approximate Survey Structure
END DESCRIPTION:
Bridge Culvert--1,0,-1,-1, 0
Deck Dist Width WeirC Skew NumUp NumDn MinLoCord MaxHiCord MaxSubmerge Is_Ogee
5,52,3,0, 37, 37, , , 0.95, 0, 1,1,,
  3622.9  3629.2  3641.3  3707.3  3756.8  3773.2  3794.9  3833.1  3839.2  3861.7
  3892.6  3899.9  3957.4  3963.2  3971.1  4030.7  4033.4  4094.4    4103  4108.2
  5737.8  5745.3  5764.5  5775.5  5785.7  5816.2  5853.6  5866.1  5882.7  5896.2
  5910.8  5954.4  5994.1  6004.9    6017  6037.9  6040.9
   30.53    30.5   30.51   29.89   29.67   29.38   29.06   28.62   28.46   28.52
   27.17   26.96   25.47   25.41   25.42   24.57   24.55   21.85   21.29    21.1
    21.1    21.6    22.7   22.64   23.04   23.52   24.32   24.98   25.22   25.31
   26.88   28.18    27.8   27.86   28.03   28.64   28.69
   -5.92   -5.92   -5.92   -5.92   -5.92   -5.92   -5.92   -5.92   -5.92   -5.92
   -5.92   -5.92   -5.92   -5.92   -5.92   -5.92   -5.92   -5.92   -5.92   -5.92
   -5.92   -5.92   -5.92   -5.92   -5.92   -5.92   -5.92   -5.92   -5.92   -5.92
   -5.92   -5.92   -5.92   -5.92   -5.92   -5.92   -5.92
  3622.9  3629.2  3641.3  3707.3  3756.8  3773.2  3794.9  3833.1  3839.2  3861.7
  3892.6  3899.9  3957.4  3963.2  3971.1  4030.7  4033.4  4094.4    4103  4108.2
  5737.8  5745.3  5764.5  5775.5  5785.7  5816.2  5853.6  5866.1  5882.7  5896.2
  5910.8  5954.4  5994.1  6004.9    6017  6037.9  6040.9
   30.53    30.5   30.51   29.89   29.67   29.38   29.06   28.62   28.46   28.52
   27.17   26.96   25.47   25.41   25.42   24.57   24.55   21.85   21.29    21.1
    21.1    21.6    22.7   22.64   23.04   23.52   24.32   24.98   25.22   25.31
   26.88   28.18    27.8   27.86   28.03   28.64   28.69
   -6.12   -6.12   -6.12   -6.12   -6.12   -6.12   -6.12   -6.12   -6.12   -6.12
   -6.12   -6.12   -6.12   -6.12   -6.12   -6.12   -6.12   -6.12   -6.12   -6.12
   -6.12   -6.12   -6.12   -6.12   -6.12   -6.12   -6.12   -6.12   -6.12   -6.12
   -6.12   -6.12   -6.12   -6.12   -6.12   -6.12   -6.12
Culvert=1,5,5,52,0.012,0.2,1,1,3,14.1,4997,13.84,4997,Culvert #1  , 0 ,5
    4997    4997
BC Culvert Barrel=1,,0
Culvert Bottom n=0.012
Culvert=1,5,5,52,0.012,0.2,1,1,3,14.1,5003,13.84,5003,Culvert #2  , 0 ,5
    5003    5003
BC Culvert Barrel=1,,0
Culvert Bottom n=0.012
BC Design=,, 0 ,, 0 ,,,,,,
BC HTab HWMax=30.34
BC Use User HTab Curves=0
BC User HTab FreeFlow(D)= 0

Type RM Length L Ch R = 1 ,6013    ,370,370,370
BEGIN DESCRIPTION:
Maple Swamp (Co Jo Rd) DS
END DESCRIPTION:
XS GIS Cut Line= 4
      2606085.05       756248.92      2605512.52       755982.79
      2604754.29        755902.8      2603719.94       755784.38
#Sta/Elev= 30
  3606.2   30.52  3737.2   29.78  3862.1   27.74  3926.8   25.79    4034      25
  4152.1    18.3  4196.3   16.31  4218.3   16.01  4341.3   16.83  4977.5   15.84
  4982.5   13.84  5017.5   13.84  5022.5   15.84  5098.8   16.89  5245.9   16.76
  5276.1   16.15  5306.3   16.82  5428.4   17.08  5517.6   18.01    5650   20.57
  5698.8   20.34  5728.9   21.46    5756   21.47  5789.4   23.25    5855   24.69
    5880      26  5910.2   26.23    5944   29.43  6000.8   29.32  6041.1   30.02
#Mann= 4 ,-1,0
  3606.2     .15       0  4977.5     .05       0  5022.5     .15       0
    5650     .11       0
#XS Ineff= 2 , 0
       0    4960      20    5040       0      20
Permanent Ineff=
       F       F
Bank Sta=4977.5,5022.5
XS Rating Curve= 0 ,0
Exp/Cntr=0.5,0.3

Type RM Length L Ch R = 1 ,5643    ,732,732,732
BEGIN DESCRIPTION:
Maple Swamp 5.0
END DESCRIPTION:
XS GIS Cut Line= 3
      2605968.59       756047.89      2604904.81       755566.09
      2603157.48       755219.89
#Sta/Elev= 30
  3832.2   26.27  3978.3   24.14  4142.5   23.46  4287.1    15.2  4433.7   16.45
  4893.6   15.08  4956.2   15.43  4979.5   16.24    4981   13.24    5019   13.24
  5020.5   16.24  5187.4   15.36  5424.3   15.96  5659.4   15.79  5783.6   16.39
  5830.7      16  5861.2   16.35  5922.4    18.3  6044.7   20.82  6136.5   23.49
  6166.4   26.18    6190   27.75  6197.6   28.45  6280.7   30.28  6341.2   32.88
  6472.9   33.66  6534.1    34.6  6574.9    34.5  6656.4   36.08  6781.3   36.13
#Mann= 4 ,-1,0
  3832.2     .15       0  4979.5     .05       0  5020.5     .15       0
    6190      .1       0
Bank Sta=4979.5,5020.5
XS Rating Curve= 0 ,0
Exp/Cntr=0.3,0.1

Type RM Length L Ch R = 1 ,4911    ,1215,1215,1215
BEGIN DESCRIPTION:
Maple Swamp 4.0
END DESCRIPTION:
XS GIS Cut Line= 3
      2605978.84       755986.58      2605437.48       755098.47
      2605263.27        754177.2
#Sta/Elev= 30
  3959.9   24.68  4036.9   22.71    4083   22.14  4442.4    19.3  4697.5    14.8
  4713.3   15.28  4756.9   15.21  4822.5   14.45  4857.7   15.25  4892.8    14.8
  4975.2   14.66    4981   12.22    5019   12.22  5022.2   14.78  5047.9   14.34
  5163.9   15.09  5457.7   18.11  5471.6   18.59  5484.4   18.08  5510.1   19.03
  5535.7   19.33  5587.1   19.18    5625   19.76  5670.1   19.82  5700.7   20.24
  5766.8   22.07  5792.5   23.31  5853.3   24.68  5883.9   25.09  5937.6   24.77
#Mann= 4 ,-1,0
  3959.9     .15       0  4975.2     .05       0  5022.2     .15       0
    5625      .1       0
Bank Sta=4975.2,5022.2
XS Rating Curve= 0 ,0
Exp/Cntr=0.3,0.1

Type RM Length L Ch R = 1 ,3696    ,1148,1148,1148
BEGIN DESCRIPTION:
Maple Swamp 3.0
END DESCRIPTION:
XS GIS Cut Line= 3
      2607185.09       755628.79      2606597.15       754772.63
      2605345.06       754146.53
#Sta/Elev= 30
  3961.4   31.96  3984.2   32.14  4020.6   29.84  4190.9   24.41  4275.3   24.65
  4366.9   23.68  4420.9   22.62  4457.3   22.62  4530.1   20.96    4560   19.59
  4602.9   17.16  4625.9   16.94  4659.3   15.25  4713.5   14.86  4759.4   16.14
  4979.5   15.32    4981   12.32    5019   12.32  5020.5   15.32  5221.8   16.05
  5293.2   15.66  5414.5   16.64  5757.1   15.56    5810   18.56  5842.1   20.98
  5909.2   22.53    6088   23.63  6226.7   23.06  6347.4   23.99  6399.9   23.86
#Mann= 5 ,-1,0
  3961.4      .1       0    4560      .1       0  4979.5     .05       0
  5020.5     .15       0    5810      .1       0
Bank Sta=4979.5,5020.5
XS Rating Curve= 0 ,0
Exp/Cntr=0.3,0.1

Type RM Length L Ch R = 1 ,2548    ,1056,1056,1056
BEGIN DESCRIPTION:
Maple Swamp 2.0
END DESCRIPTION:
XS GIS Cut Line= 3
      2608084.66       755618.55      2607528.73        754104.7
      2606653.54       752786.96
#Sta/Elev= 30
  3387.3   37.65  3460.3   35.29  3524.2   29.72  3561.2   28.26  3588.2   28.38
  3652.1   25.66  3888.5   24.22  3939.7   24.58  4003.6   24.06  4099.5    24.7
  4227.3    22.5  4323.2   22.49  4546.9    17.3  4613.1   16.29    4630   16.73
  4719.7   17.32  4979.5   15.08    4981   12.08    5019   12.08  5020.5   15.08
  5193.4   18.65  5345.4   18.91    5470   20.05  5529.1   20.55  5615.6    22.4
    5930   24.03  6091.7   24.34  6243.2   23.75  6416.3   22.28  6581.9   22.44
#Mann= 5 ,-1,0
  3387.3      .1       0    4630     .15       0  4979.5     .05       0
  5020.5     .15       0    5470      .1       0
Bank Sta=4979.5,5020.5
XS Rating Curve= 0 ,0
Exp/Cntr=0.3,0.1

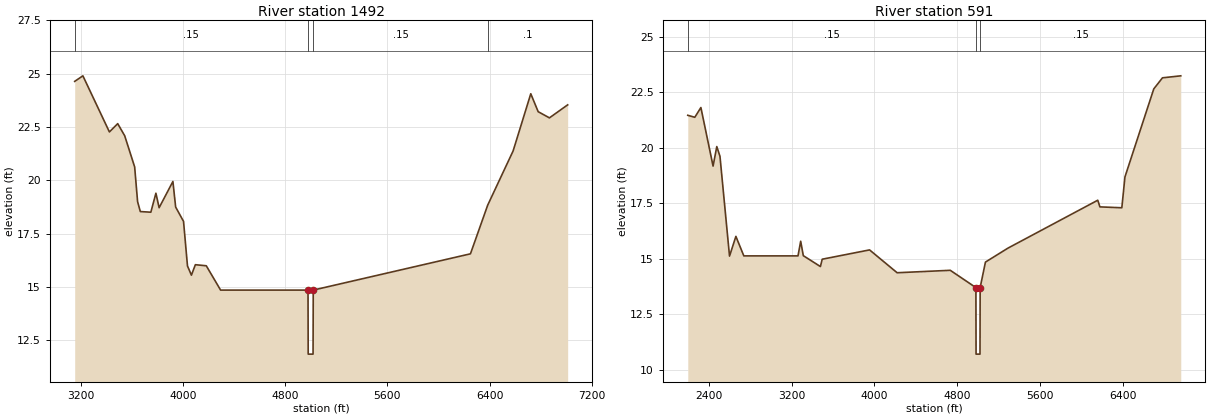
Type RM Length L Ch R = 1 ,1492    ,901,901,901
BEGIN DESCRIPTION:
Maple Swamp 1.0
END DESCRIPTION:
XS GIS Cut Line= 4
      2608319.78       755291.44      2608616.23       754565.64
      2608372.92       753532.42      2606653.49       752490.46
#Sta/Elev= 30
  3154.5   24.64  3218.7    24.9  3426.1   22.27  3490.9   22.66  3545.8   22.09
  3623.6   20.63  3646.6      19    3668   18.54  3750.2   18.51  3789.8    19.4
    3815   18.72  3922.7   19.95  3944.3   18.75  4005.9   18.08  4036.8   15.99
  4067.6   15.56  4098.4   16.05  4183.8      16  4295.9   14.86  4979.5   14.86
    4981   11.86    5019   11.86  5020.5   14.86  6250.1   16.56    6385   18.84
  6583.8   21.38    6722   24.06  6779.8   23.22  6867.8   22.93  7010.5   23.54
#Mann= 4 ,-1,0
  3154.5     .15       0  4979.5     .05       0  5020.5     .15       0
    6385      .1       0
Bank Sta=4979.5,5020.5
XS Rating Curve= 0 ,0
Exp/Cntr=0.3,0.1

Type RM Length L Ch R = 1 ,591     ,0,0,0
BEGIN DESCRIPTION:
Maple Swamp 0.5
END DESCRIPTION:
XS GIS Cut Line= 4
      2609297.06       755253.57      2608755.97       752778.34
      2608272.43       752502.03      2606614.53       752317.82
#Sta/Elev= 30
  2198.3   21.47    2266   21.38  2324.8   21.82  2442.4   19.18  2478.3   20.06
    2509   19.62  2601.2   15.12  2662.6   16.01  2739.3   15.13  3262.1   15.13
  3288.2   15.79  3313.4   15.14  3478.5   14.65  3495.9   14.98    3953    15.4
  4219.1   14.37    4732   14.48  4979.5    13.7    4981    10.7    5019    10.7
  5020.5    13.7  5071.5   14.85  5288.9   15.48  6155.7   17.64  6176.8   17.34
  6388.1    17.3  6418.2   18.69  6696.5   22.66  6780.5   23.16    6957   23.25
#Mann= 3 ,-1,0
  2198.3     .15       0  4979.5     .05       0  5020.5     .15       0
Bank Sta=4979.5,5020.5
XS Rating Curve= 0 ,0
Exp/Cntr=0.3,0.1
LCMann Table=0

--- MapleSwamp.g02 (geometry) ---

Geom Title=Proposed Conditions
Program Version=6.60

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
River Reach=Maple Swamp     ,Reach-1

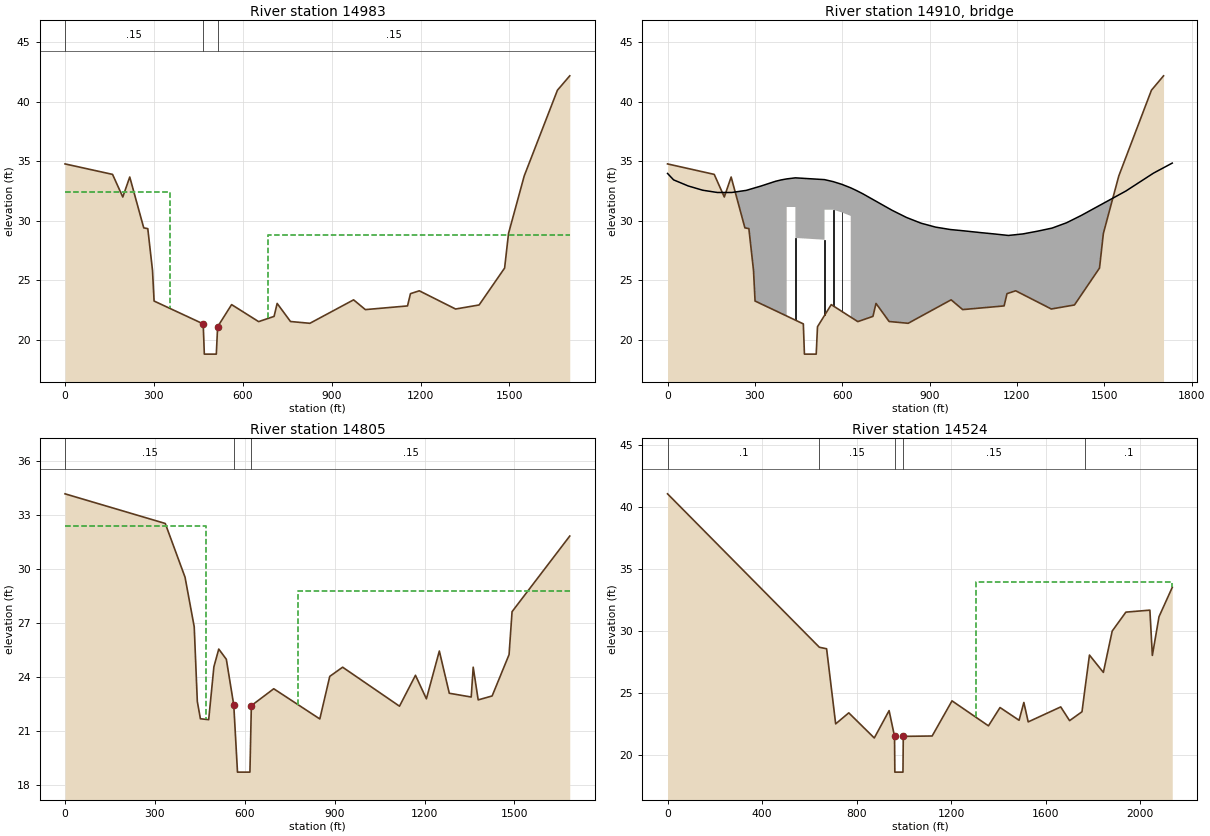
Type RM Length L Ch R = 1 ,14983   ,178.4,178.4,178.4
BEGIN DESCRIPTION:
Maple Swamp (HWY-65) US
END DESCRIPTION:
XS GIS Cut Line= 6
2606270.99543383 764294.697914162606020.25670458764349.151248127
2605826.05042104764407.279025191      2605492.18         764527.
2605378.51949651764553.548940603 2604612.5311043 764655.20192812
#Sta/Elev= 30
       0   34.78  160.37    33.9  194.95      32  218.45   33.68  265.63   29.41
  279.33   29.34  295.24   25.84  300.58   23.26  466.37   21.34  470.14    18.8
  510.62    18.8     515    21.1  562.23   22.96  653.45   21.53  705.54   21.97
  715.93   23.06  760.97   21.54  826.44   21.39  973.91   23.36 1013.62   22.54
 1155.94   22.85 1165.86   23.88 1195.65   24.12 1318.11   22.59 1397.54   22.93
 1483.59   26.03 1496.83   28.94 1549.78   33.77 1661.85   40.97 1703.46   42.18
#Mann= 3 ,0,0
       0     .15       0  466.37     .05       0     515     .15       0
#XS Ineff= 2 , 0
       0  352.87   32.38   685.5       0   28.77
Permanent Ineff=
       F       F
Bank Sta=466.37,515
XS Rating Curve= 0 ,0
Exp/Cntr=0.5,0.3

Type RM Length L Ch R = 3 ,14910   ,,,
BEGIN DESCRIPTION:
Maple Swamp (HWY-65) TOR
Structure ID: LDS_MPS_02
Approximate Survey Structure
END DESCRIPTION:
Bridge Culvert--1,0,-1,-1, 0
Deck Dist Width WeirC Skew NumUp NumDn MinLoCord MaxHiCord MaxSubmerge Is_Ogee
56.315,36.25,3,0, 41, 40, , , 0.95, 0, 2,2,,
       0  20.735  70.735 120.735 170.735 220.735 270.735 320.735 370.735 389.185
 409.184 409.185 439.184 439.185 539.185 539.186 569.185 599.185 629.185 629.186
 649.185 670.735 720.735 770.735 820.735 870.735 920.735 970.7351020.7351070.735
1120.7351170.7351220.7351270.7351320.7351370.7351420.7351470.7351573.9851668.585
1733.385
   33.98   33.44   32.93   32.57   32.38   32.38   32.56   32.92   33.32   33.43
   33.52   33.52   33.61   33.61   33.46   33.46   33.29   33.06   32.77   32.77
   32.54   32.27   31.58   30.89   30.28    29.8   29.47   29.27   29.15   29.02
    28.9   28.77    28.9   29.13   29.39   29.84   30.45   31.12    32.5      34
   34.85
                                                                                
           31.16   31.16   28.56   28.41   30.93   30.93    30.7   30.41
                                                                                
                                                                                
        
   76.55  126.55  176.55  226.55  276.55  326.55  376.55  426.55  476.55     495
 514.999     515 544.999     545     645 645.001     675     705     735 735.001
     755  776.55  826.55  876.55  926.55  976.55 1026.55 1076.55 1126.55 1176.55
 1226.55 1276.55 1326.55 1376.55 1426.55 1476.55 1526.55 1576.55  1649.8  1719.2
   33.98   33.44   32.93   32.57   32.38   32.38   32.56   32.92   33.32   33.43
   33.52   33.52   33.61   33.61   33.46   33.46   33.29   33.06   32.77   32.77
   32.54   32.27   31.58   30.89   30.28    29.8   29.47   29.27   29.15   29.02
    28.9   28.77    28.9   29.13   29.39   29.84   30.45   31.12    32.5      34
                                                                                
           31.16   31.16   28.56   28.41   30.93   30.93    30.7   30.41
                                                                                
                                                                                
Pier Skew, UpSta & Num, DnSta & Num=  ,439.185, 2 ,545, 2 , 0 , 0 , 0 ,,
       4       4
       0      32
       4       4
       0      32
Pier Skew, UpSta & Num, DnSta & Num=  ,539.185, 2 ,645, 2 , 0 , 0 , 0 ,,
       4       4
       0      32
       4       4
       0      32
Pier Skew, UpSta & Num, DnSta & Num=  ,569.185, 2 ,675, 2 , 0 , 0 , 0 ,,
       2       2
       0      32
       2       2
       0      32
Pier Skew, UpSta & Num, DnSta & Num=  ,599.185, 2 ,705, 2 , 0 , 0 , 0 ,,
       2       2
       0      32
       2       2
       0      32
Abutment Skew #Up #Dn= , 3 , 3
 409.185 411.185 451.185
      27      27       7
     515     517     557
      27      27       7
Abutment Skew #Up #Dn= , 3 , 3
 587.185 627.185 629.185
       7      27      27
     693     733     735
       7      27      27
BR Coef=-1 , 1 , 1 ,0.9, 0 ,,,0.8,0,1.2,0,
WSPro=,,,, 1 ,,,, 0 ,,,, 0 ,,,,-1 ,-1 ,-1 , 0 , 0 , 0 , 0 , 0
BC Design=,, 0 ,, 0 ,,,,,,
BC HTab HWMax=42.97
BC Use User HTab Curves=0
BC User HTab FreeFlow(D)= 0

Type RM Length L Ch R = 1 ,14805   ,280.5,280.5,280.5
BEGIN DESCRIPTION:
Maple Swamp (HWY-65) DS
END DESCRIPTION:
XS GIS Cut Line= 6
2606230.15242302764153.3335826612605956.41891485764221.747375249
2605717.76125913764299.580046683 2605609.6181506764338.869154525
2605425.12236869  764389.45403362604591.13352491764525.198147551
#Sta/Elev= 30
       0   34.19  334.55   32.54  400.54   29.55  431.18   26.79  441.53   22.63
  451.88   21.67  479.49   21.62  496.83   24.56  513.07   25.55  538.37   24.98
  563.19   22.43  575.61    18.7  617.11    18.7  621.84    22.4  696.63   23.34
  850.33   21.66  883.58   24.03  926.51   24.54 1116.29   22.37 1169.63   24.09
 1206.05   22.78 1249.26   25.44 1282.51   23.09 1355.65   22.88 1362.29   24.54
 1378.92   22.72 1425.46   22.94 1481.97   25.24 1491.95   27.63 1684.52   31.84
#Mann= 3 ,0,0
       0     .15       0  563.19     .05       0  621.84     .15       0
#XS Ineff= 2 , 0
       0   472.1   32.38   777.9       0   28.77
Permanent Ineff=
       F       F
Bank Sta=563.19,621.84
XS Rating Curve= 0 ,0
Exp/Cntr=0.5,0.3

Type RM Length L Ch R = 1 ,14524   ,509.7,509.7,509.7
BEGIN DESCRIPTION:
Maple Swamp 19.0
END DESCRIPTION:
XS GIS Cut Line= 3
       2606299.2       763639.26      2605460.96       764145.41
      2604377.67       764551.49
#Sta/Elev= 30
       0   41.09   642.6   28.69   673.2   28.57   711.6    22.5   767.1   23.39
     875   21.36   937.7   23.57   960.7   21.49961.9998    18.6996.4001    18.6
   997.7   21.49  1119.9   21.52    1204   24.36  1358.2   22.34  1407.2   23.82
  1487.8   22.79    1508   24.23  1526.4   22.66  1664.1   23.87  1701.6   22.76
  1754.1   23.48  1768.1   25.54  1785.7   28.06  1844.5   26.66  1881.9      30
  1939.8   31.53  2041.4   31.69  2051.9   28.03    2080   31.16  2136.1   33.53
#Mann= 5 ,-1,0
       0      .1       0   642.6     .15       0   960.7    .052       0
   997.7     .15       0  1768.1      .1       0
#XS Ineff= 2 , 0
       0                 1305.71       0      34
Permanent Ineff=
       F       F
Bank Sta=960.7,997.7
XS Rating Curve= 0 ,0
Exp/Cntr=0.5,0.3

--- MapleSwamp.g06 (geometry) ---

Geom Title=Natural Conditions
Program Version=6.60

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
River Reach=Maple Swamp     ,Reach-1