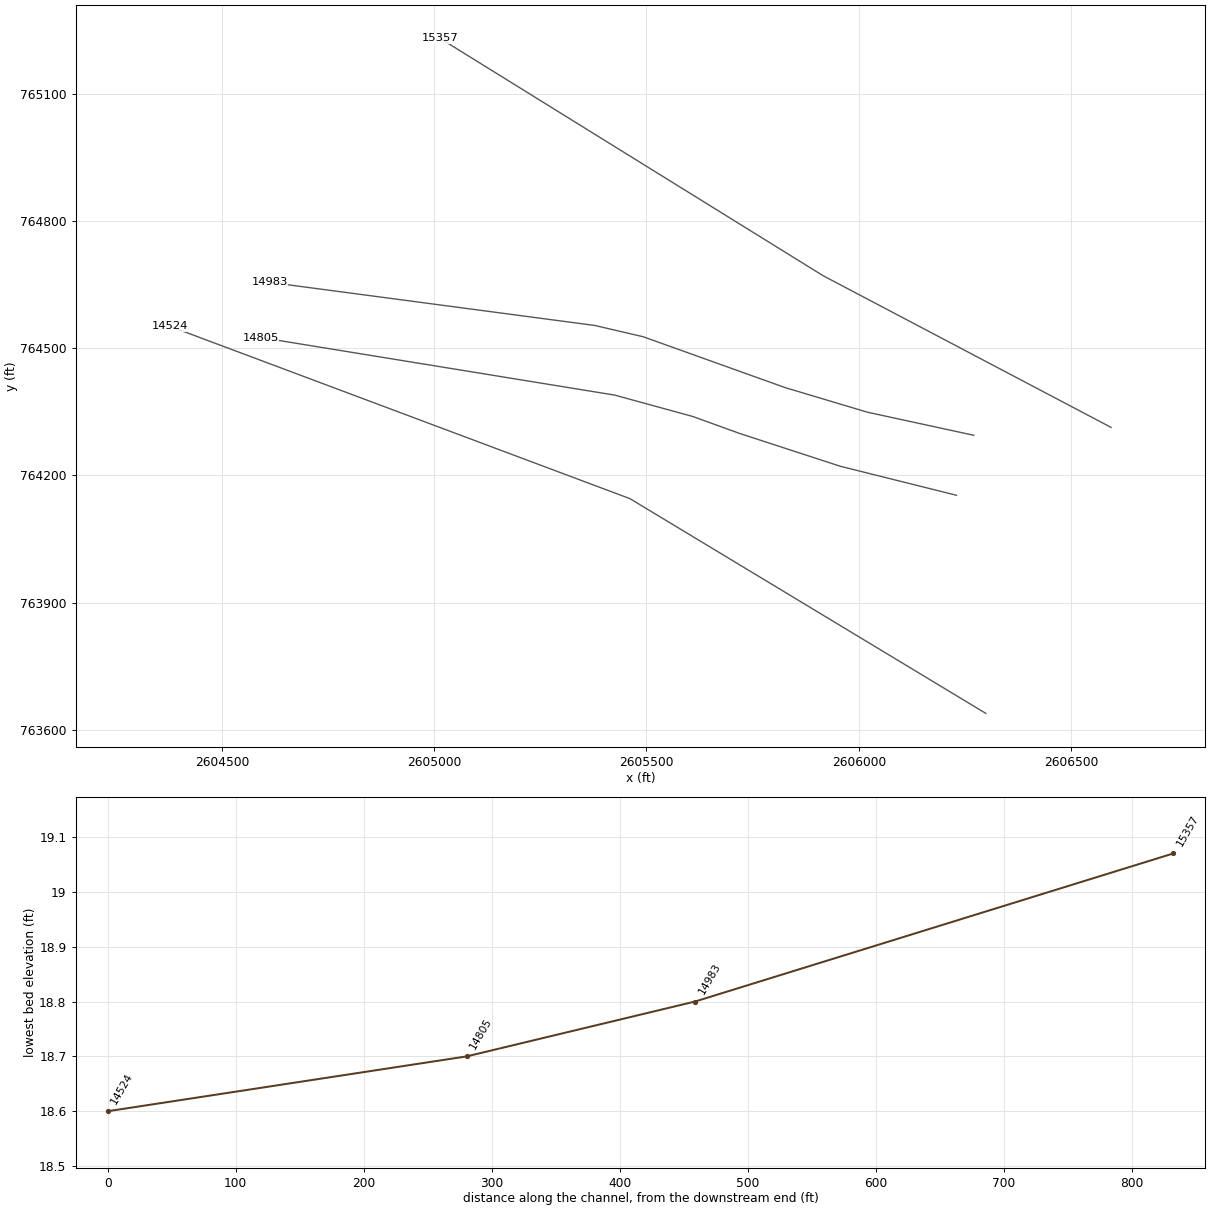
HEC-RAS study MapleSwamp.prj: S-26-65 over Maple Swamp

--- MapleSwamp.g06 (geometry) --- (continued)

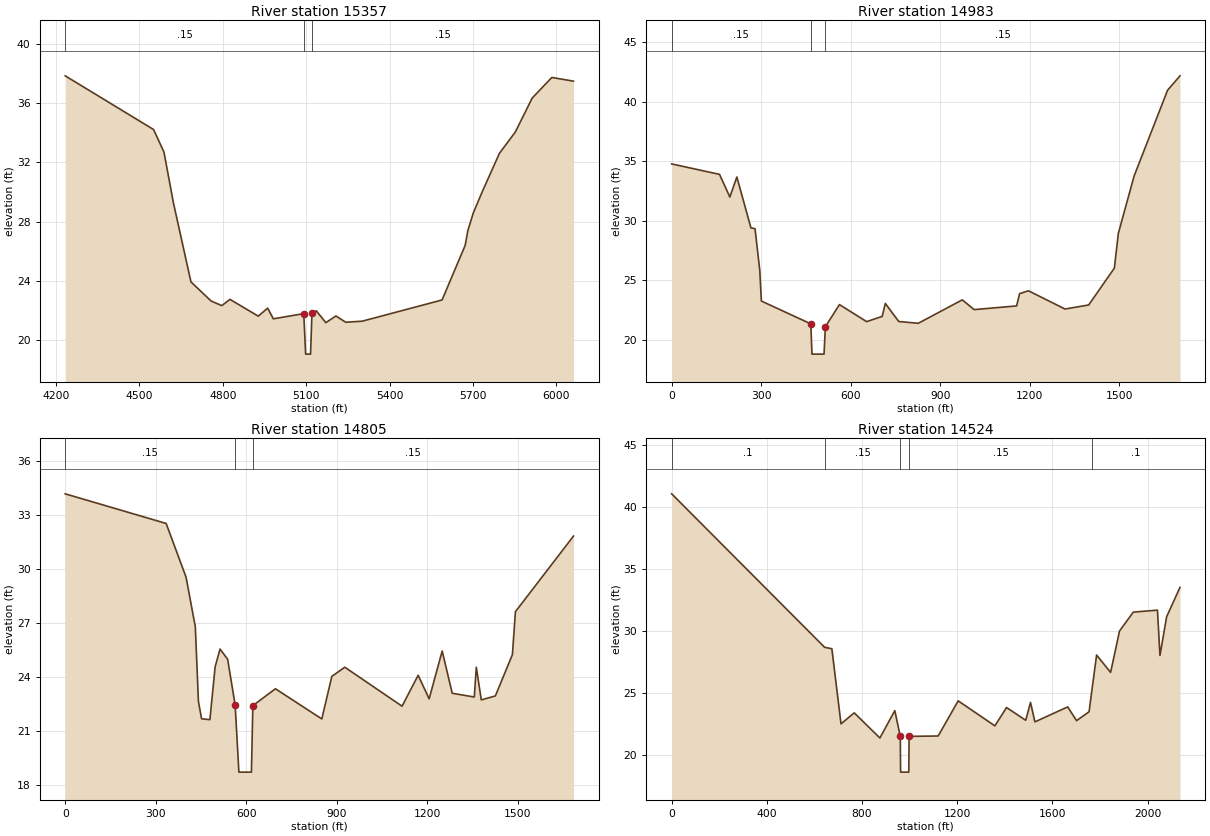
Type RM Length L Ch R = 1 ,15357   ,373.7,373.7,373.7
BEGIN DESCRIPTION:
Maple Swamp 20.0
END DESCRIPTION:
XS GIS Cut Line= 3
      2606594.28        764313.3       2605915.6       764671.07
      2605013.64       765230.37
#Sta/Elev= 30
  4232.8   37.83  4550.7   34.21  4588.1   32.69    4622   29.27  4685.1   23.94
  4757.6   22.65  4796.1   22.34  4825.5   22.76  4927.2   21.63  4961.1   22.17
  4981.5   21.45 5090.88    21.8 5097.73   19.07 5115.33   19.07 5120.35   21.83
    5136   21.99  5170.3   21.19  5206.6   21.64  5241.9   21.22  5301.1   21.29
  5588.4   22.72  5671.5    26.4  5681.1   27.39  5700.8   28.59    5733   30.02
  5794.9   32.61  5851.9   34.04  5912.6   36.33  5983.2   37.72  6061.3   37.47
#Mann= 3 ,0,0
  4232.8     .15       0 5090.88     .05       0 5120.35     .15       0
Bank Sta=5090.88,5120.35
XS Rating Curve= 0 ,0
Exp/Cntr=0.3,0.1

Type RM Length L Ch R = 1 ,14983   ,178.4,178.4,178.4
BEGIN DESCRIPTION:
Maple Swamp (HWY-65) US
END DESCRIPTION:
XS GIS Cut Line= 6
2606270.99543383 764294.697914162606020.25670458764349.151248127
2605826.05042104764407.279025191      2605492.18         764527.
2605378.51949651764553.548940603 2604612.5311043 764655.20192812
#Sta/Elev= 30
       0   34.78  160.37    33.9  194.95      32  218.45   33.68  265.63   29.41
  279.33   29.34  295.24   25.84  300.58   23.26  466.37   21.34  470.14    18.8
  510.62    18.8     515    21.1  562.23   22.96  653.45   21.53  705.54   21.97
  715.93   23.06  760.97   21.54  826.44   21.39  973.91   23.36 1013.62   22.54
 1155.94   22.85 1165.86   23.88 1195.65   24.12 1318.11   22.59 1397.54   22.93
 1483.59   26.03 1496.83   28.94 1549.78   33.77 1661.85   40.97 1703.46   42.18
#Mann= 3 ,0,0
       0     .15       0  466.37     .05       0     515     .15       0
Bank Sta=466.37,515
XS Rating Curve= 0 ,0
Exp/Cntr=0.3,0.1

Type RM Length L Ch R = 1 ,14805   ,280.5,280.5,280.5
BEGIN DESCRIPTION:
Maple Swamp (HWY-65) DS
END DESCRIPTION:
XS GIS Cut Line= 6
2606230.15242302764153.3335826612605956.41891485764221.747375249
2605717.76125913764299.580046683 2605609.6181506764338.869154525
2605425.12236869  764389.45403362604591.13352491764525.198147551
#Sta/Elev= 30
       0   34.19  334.55   32.54  400.54   29.55  431.18   26.79  441.53   22.63
  451.88   21.67  479.49   21.62  496.83   24.56  513.07   25.55  538.37   24.98
  563.19   22.43  575.61    18.7  617.11    18.7  621.84    22.4  696.63   23.34
  850.33   21.66  883.58   24.03  926.51   24.54 1116.29   22.37 1169.63   24.09
 1206.05   22.78 1249.26   25.44 1282.51   23.09 1355.65   22.88 1362.29   24.54
 1378.92   22.72 1425.46   22.94 1481.97   25.24 1491.95   27.63 1684.52   31.84
#Mann= 3 ,0,0
       0     .15       0  563.19     .05       0  621.84     .15       0
Bank Sta=563.19,621.84
XS Rating Curve= 0 ,0
Exp/Cntr=0.3,0.1

Type RM Length L Ch R = 1 ,14524   ,509.7,509.7,509.7
BEGIN DESCRIPTION:
Maple Swamp 19.0
END DESCRIPTION:
XS GIS Cut Line= 3
       2606299.2       763639.26      2605460.96       764145.41
      2604377.67       764551.49
#Sta/Elev= 30
       0   41.09   642.6   28.69   673.2   28.57   711.6    22.5   767.1   23.39
     875   21.36   937.7   23.57   960.7   21.49961.9998    18.6996.4001    18.6
   997.7   21.49  1119.9   21.52    1204   24.36  1358.2   22.34  1407.2   23.82
  1487.8   22.79    1508   24.23  1526.4   22.66  1664.1   23.87  1701.6   22.76
  1754.1   23.48  1768.1   25.54  1785.7   28.06  1844.5   26.66  1881.9      30
  1939.8   31.53  2041.4   31.69  2051.9   28.03    2080   31.16  2136.1   33.53
#Mann= 5 ,-1,0
       0      .1       0   642.6     .15       0   960.7    .052       0
   997.7     .15       0  1768.1      .1       0
Bank Sta=960.7,997.7
XS Rating Curve= 0 ,0
Exp/Cntr=0.3,0.1