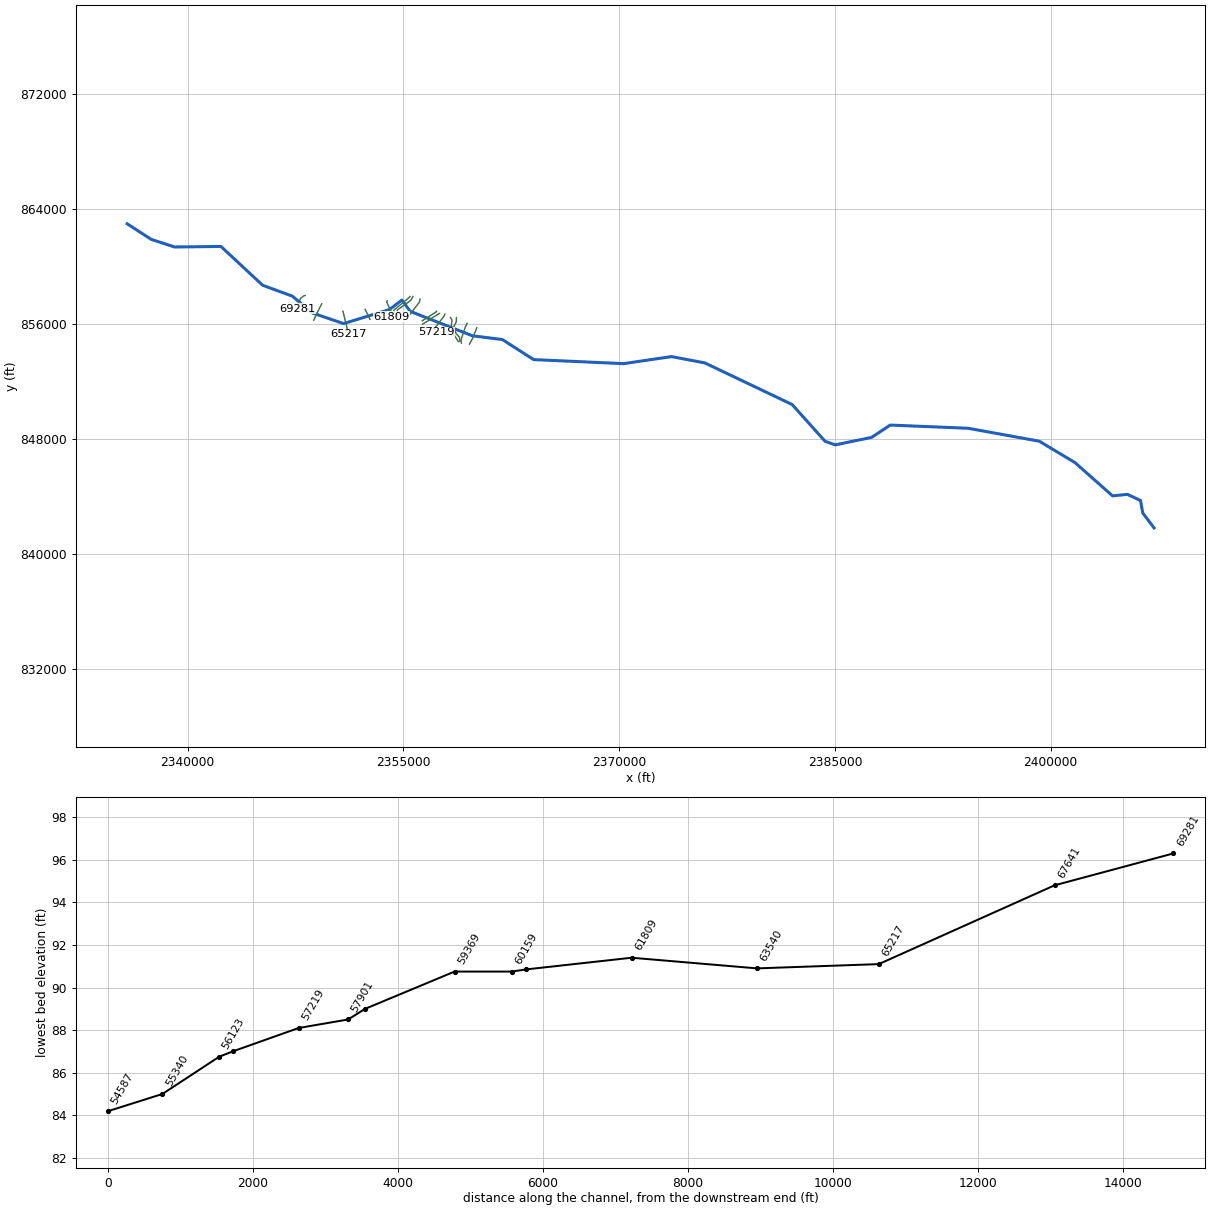
--- JefferiesCreek.prj (project) ---

Proj Title=S-21-29 over Jeffries Creek
Current Plan=p10
Default Exp/Contr=0.3,0.1
English Units
Geom File=g01
Geom File=g02
Geom File=g04
Geom File=g07
Geom File=g09
Flow File=f01
Flow File=f02
Flow File=f03
Flow File=f04
Plan File=p01
Plan File=p02
Plan File=p03
Plan File=p04
Plan File=p05
Plan File=p07
Plan File=p09
Plan File=p10
Y Axis Title=Elevation
X Axis Title(PF)=Main Channel Distance
X Axis Title(XS)=Station
BEGIN DESCRIPTION:
END DESCRIPTION:
DSS Export Rating Curves= 0
DSS Export Rating Curve Sorted= 0
DSS Export Volume Flow Curves= 0
DXF OffsetX= 0
DXF OffsetY= 0
DXF ScaleX= 1
DXF ScaleY= 10

--- JefferiesCreek.p10 (plan) ---

Plan Title=Revised Conditions Floodway
Program Version=6.60
Short Identifier=REV_FW
Geom File=g09
Flow File=f02
Subcritical Flow
K Sum by GR= 0
Std Step Tol= 0.01
Critical Tol= 0.01
Num of Std Step Trials= 20
Max Error Tol= 0.3
Flow Tol Ratio= 0.001
Split Flow NTrial= 30
Split Flow Tol= 0.02
Split Flow Ratio= 0.02
Log Output Level= 0
Friction Slope Method= 1
Unsteady Friction Slope Method= 2
Unsteady Bridges Friction Slope Method= 1
Calc Critical at every XS
Parabolic Critical Depth
Global Vel Dist= 0 , 0 , 0
Global Log Level= 0
CheckData=True
Encroach Param=-1 ,0,0, 3
Encroach River=Jeffries Creek
Encroach Reach=Reach 1
Encroach Node=69281
       1   595.8   961.8       1   595.8   961.8
Encroach Node=67641
       1   595.7   980.6       1   595.7   980.6
Encroach Node=65217
       1     519   983.9       1     519   983.9
Encroach Node=63540
       1   137.3   584.9       1   137.3   584.9
Encroach Node=61809
       1   295.8     766       1   295.8     766
Encroach Node=60351
       1     301  1215.7       1     301  1215.7
Encroach Node=60159
       1   780.3  1005.4       1   780.3  1005.4
Encroach Node=59369
       1   654.4  1232.5       1   654.4  1232.5
Encroach Node=58136
       1   359.7   931.7       1   359.7   931.7
Encroach Node=57901
       1   534.1   809.2       1   534.1   809.2
Encroach Node=57219
       1   544.7   770.5       1   544.7   770.5
Encroach Node=56310
       1   522.1   774.6       1   522.1   774.6
Encroach Node=56123
       1   523.1   702.2       1   523.1   702.2
Encroach Node=55340
       1   339.2   974.7       1   339.2   974.7
Encroach Node=54587
       1   542.1   833.4       1   542.1   833.4
Encroach Node=54294
       1   465.5   710.2       1   465.5   710.2
Encroach Node=53775
       1   268.2     700       1   268.2     700
Encroach Node=53342
       1   192.2   787.8       1   192.2   787.8
Encroach Node=51665
       1   203.4   894.2       1   203.4   894.2
Flow Ratio Tolerance=0.1
Flow Ratio Min Ratio=0.5
Flow Ratio Max Ratio=4
Flow Ratio Max Iterations= 10
Computation Interval=1MIN
Output Interval=1HOUR
Instantaneous Interval=1HOUR
Mapping Interval=1HOUR
Computation Time Step Use Courant=        0
Computation Time Step Use Time Series=    0
Computation Time Step Count To Double=0
Computation Time Step Max Doubling=0
Computation Time Step Max Halving=0
Computation Time Step Residence Courant=0
Run HTab= 0
Run UNet= 0
Run Sediment= 0
Run PostProcess= 0
Run WQNet= 0
Run RASMapper= 0
UNET Theta= 1
UNET Theta Warmup= 1
UNET ZTol= 0.02
UNET ZSATol= 0.02
UNET MxIter= 20
UNET Max Iter WO Improvement= 0
UNET MaxInSteps= 0
UNET DtIC= 0
UNET DtMin= 0
UNET MaxCRTS= 20
UNET WFStab= 2
UNET SFStab= 1
UNET WFX= 1
UNET SFX= 1
UNET Gravity=32.17405
UNET 1D Methodology=Finite Difference
UNET DSS MLevel= 4
UNET Pardiso=0
UNET DZMax Abort= 100
UNET Use Existing IB Tables=-1
UNET Froude Reduction=False
UNET Froude Limit= 0.8
UNET Froude Power= 4
UNET D1 Cores= 0
UNET WindReference=Eulerian
UNET WindDragFormulation=Hsu (1988)
UNET D2 Coriolis=0
UNET D2 Cores= 0
UNET D2 Theta= 1
UNET D2 Theta Warmup= 1
UNET D2 Z Tol= 0.01
UNET D2 Volume Tol= 0.01
UNET D2 Max Iterations= 20
UNET D2 Advanced Convergence=0
UNET D2 WS Max Tol=0.15
UNET D2 WS RMS Tol=0.002
UNET D2 WS Stall Tol=1
UNET D2 Equation= 0
UNET D2 RampUpFraction=0.1
UNET D2 TimeSlices= 1
UNET D2 Turbulence Formulation=None
UNET D2 Eddy Viscosity=0.3
UNET D2 Transverse Eddy Viscosity=0.1
UNET D2 Smagorinsky Mixing=0.05
UNET D2 BCVolumeCheck=0
UNET D2 Cores=0
UNET D2 SolverType=PARDISO (Direct)
UNET D2 Minimum Iterations= 3
UNET D2 Maximum Iterations= 30
UNET D2 Restart Number= 10
UNET D2 Relaxation Coeff=1.3
UNET D2 SOR Precondition Iterations= 10
UNET D2 ILUT Maximum Fill= 8
UNET D2 ILUT Tolerance=1E-08
UNET D2 Convergence Tolerance=0.00001
PS Theta= 1
PS WS Tol= 0.01
PS Volume Tol= 0.01
PS Max Iterations= 20
PS Equation= 0
PS Advance Time Step=-1
PS Target Courant=0.9
PS Time Slices= 1
PS Iterate With 2D=0
PS Project Initial WSE from DS=-1
PS Ramp Up Initial WSE from US=-1
PS Cores=0
UNET D1D2 MaxIter= 0
UNET D1D2 ZTol=0.01
UNET D1D2 QTol=0.1
UNET D1D2 MinQTol=1
Write IC File= 0
Write IC File at Fixed DateTime=0
Write IC File at Sim End=0
Echo Input=False
Echo Parameters=False
Echo Output=False
Write Detailed= 0
HDF Write Warmup=0
HDF Write Time Slices=0
HDF Flush=0
HDF Compression= 1
HDF Chunk Size= 1
HDF Spatial Parts= 1
HDF Use Max Rows=0
HDF Fixed Rows= 1
Calibration Method= 0
Calibration Iterations= 20
Calibration Max Change=0.05
Calibration Tolerance=0.2
Calibration Maximum=1.5
Calibration Minimum=0.5
Calibration Optimization Method= 1
WQ AD Non Conservative
WQ ULTIMATE=-1
WQ Max Comp Step=1HOUR
WQ Output Interval=15MIN
WQ Output Selected Increments= 0
WQ Create Restart=0
WQ Fixed Restart=0
WQ System Summary=0
WQ Write To DSS=0
Sorting and Armoring Iterations= 10
XS Update Threshold= 0.02
Bed Roughness Predictor= 0
Processes Affected by Predictor=Sediment Only
Hydraulics Update Threshold= 0.02
Energy Slope Method= 1
Volume Change Method= 1
Sediment Retention Method= 0
Sediment TS Multiplier= 1
Warm Up Method= 0
XS Weighting Method= 0
Number of US Weighted Cross Sections= 1
Number of DS Weighted Cross Sections= 1
Upstream XS Weight=0
Main XS Weight=1
Downstream XS Weight=0
Number of DS XS's Weighted with US Boundary= 1
Upstream Boundary Weight= 1
Weight of XSs Associated with US Boundary= 0
Number of US XS's Weighted with DS Boundary= 1
Downstream Boundary Weight= 0.5
Weight of XSs Associated with DS Boundary= 0.5
Percentile Method= 0
Sediment Output Level= 3
Mass or Volume Output= 0
Output Increment Type= 1
Profile and TS Output Increment= 1
Transport Output Increment 1
XS Output Flag= 0
XS Output Increment= 10
Read HDF5 Sediment Hotstart= 0
Sediment Hotstart Type= 0
Write Gradation File= 0
Read Gradation Hotstart= 0
Write HDF5 File= 1
Write Binary Output= 1
Write DSS Sediment File= 0
DSS Sediment Output Type= 1
SV Curve= 0
Specific Gage Flag= 0
Subcell Erosion Methods= 0
Subcell Deposition Methods= 0
Advection Scheme= 1
Matrix Solver= 0
Implicit Weighting Factor= 1
Maximum Outer Loop Convergence Iterations= 5
Convergence Maximum Absolute= 0.001
Convergence RMSE= 0.0001
Grain Fractions Max Abs Error= 0.001
Max Subgrid Regions= 1
Max Subgrid Length Scale= 3.402823E+38
Initial Layer Thickness= 3
Min Layer Thickness= 0.1
Max Layer Thickness= 6
Number of Layers= 5

--- JefferiesCreek.p01 (plan) ---

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Plan Title=Corrected Effective
Short Identifier=CE
Geom File=g01
Flow File=f01
Encroach Param=-1 ,0,0, 0

--- JefferiesCreek.p02 (plan) ---

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Plan Title=Corrected Effective Floodway
Short Identifier=CE FW
Geom File=g01
Flow File=f02
Encroach Param=-1 ,0,0, 2
       1   595.8   961.8
       1   595.7   980.6
       1     519   983.9
       1   137.3   584.9
       1   295.8     766
       1     301  1215.7
       1   780.3  1005.4
       1   654.4  1232.5
       1   359.7   931.7
       1   534.1   809.2
       1   544.7   770.5
       1   522.1   774.6
       1   523.1   702.2
       1   339.2   974.7
       1   542.1   833.4
       1   465.5   710.2
       1   268.2     700
       1   192.2   787.8
       1   203.4   894.2

--- JefferiesCreek.p03 (plan) ---

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Plan Title=Existing
Short Identifier=EX
Geom File=g02
Flow File=f04
Encroach Param=-1 ,0,0, 2

--- JefferiesCreek.p04 (plan) ---

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Plan Title=Sensitivity Analysis
Short Identifier=EX SA
Geom File=g02
Flow File=f03
Encroach Param=-1 ,0,0, 2

--- JefferiesCreek.p05 (plan) ---

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Plan Title=Natural
Short Identifier=NAT
Geom File=g04
Flow File=f04
Encroach Param=-1 ,0,0, 2

--- JefferiesCreek.p07 (plan) ---

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Plan Title=Proposed
Short Identifier=PROP
Geom File=g07
Flow File=f04
Encroach Param=-1 ,0,0, 2

--- JefferiesCreek.p09 (plan) ---

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Plan Title=Revised Conditions
Short Identifier=REV
Geom File=g09
Flow File=f01
Encroach Param=-1 ,0,0, 0

--- JefferiesCreek.f02 (steady flow) ---

Flow Title=Floodway
Program Version=6.60
Number of Profiles= 2
Profile Names=100yr,100yr FW
River Rch & RM=Jeffries Creek,Reach 1         ,69281
    3620    3620
River Rch & RM=Jeffries Creek,Reach 1         ,60351
    4550    4550
River Rch & RM=Jeffries Creek,Reach 1         ,54294
    5250    5250
Boundary for River Rch & Prof#=Jeffries Creek,Reach 1         , 1
Up Type= 0
Dn Type= 1
Dn Known WS=93
Boundary for River Rch & Prof#=Jeffries Creek,Reach 1         , 2
Up Type= 0
Dn Type= 1
Dn Known WS=94
DSS Import GetInterval= 0
DSS Import GetPeak= 0
DSS Import FillOption= 0

--- JefferiesCreek.f01 (steady flow) ---

Flow Title=FEMA Flows
Program Version=6.60
Number of Profiles= 4
Profile Names=10yr,50yr,100yr,500yr
River Rch & RM=Jeffries Creek,Reach 1         ,69281
    1650    2850    3620    5700
River Rch & RM=Jeffries Creek,Reach 1         ,60351
    2150    3600    4550    7000
River Rch & RM=Jeffries Creek,Reach 1         ,54294
    2500    4200    5250    8100
Boundary for River Rch & Prof#=Jeffries Creek,Reach 1         , 1
Up Type= 0
Dn Type= 3
Dn Slope=0.001
Boundary for River Rch & Prof#=Jeffries Creek,Reach 1         , 2
Up Type= 0
Dn Type= 3
Dn Slope=0.001
Boundary for River Rch & Prof#=Jeffries Creek,Reach 1         , 3
Up Type= 0
Dn Type= 1
Dn Known WS=93
Boundary for River Rch & Prof#=Jeffries Creek,Reach 1         , 4
Up Type= 0
Dn Type= 3
Dn Slope=0.001
DSS Import GetInterval= 0
DSS Import GetPeak= 0
DSS Import FillOption= 0

--- JefferiesCreek.f03 (steady flow) ---

Flow Title=Sensitivity
Program Version=6.60
Number of Profiles= 3
Profile Names=100yr - 3ft,100yr ,100yr + 3ft
River Rch & RM=Jeffries Creek,Reach 1         ,69281
    3880    3880    3880
River Rch & RM=Jeffries Creek,Reach 1         ,60351
    4620    4620    4620
Boundary for River Rch & Prof#=Jeffries Creek,Reach 1         , 1
Up Type= 0
Dn Type= 1
Dn Known WS=82.71
Boundary for River Rch & Prof#=Jeffries Creek,Reach 1         , 2
Up Type= 0
Dn Type= 1
Dn Known WS=85.71
Boundary for River Rch & Prof#=Jeffries Creek,Reach 1         , 3
Up Type= 0
Dn Type= 1
Dn Known WS=88.71
DSS Import GetInterval= 0
DSS Import GetPeak= 0
DSS Import FillOption= 0

--- JefferiesCreek.f04 (steady flow) ---

Flow Title=USGS Flows
Program Version=6.60
Number of Profiles= 6
Profile Names=2-year,10-year,25-year,50-year,100-year,500-year
River Rch & RM=Jeffries Creek,Reach 1         ,69281
     681    1810    2540    3210    3880    5570
River Rch & RM=Jeffries Creek,Reach 1         ,60351
     821    2160    3030    3830    4620    6620
Boundary for River Rch & Prof#=Jeffries Creek,Reach 1         , 1
Up Type= 0
Dn Type= 3
Dn Slope=0.001
Boundary for River Rch & Prof#=Jeffries Creek,Reach 1         , 2
Up Type= 0
Dn Type= 3
Dn Slope=0.001
Boundary for River Rch & Prof#=Jeffries Creek,Reach 1         , 3
Up Type= 0
Dn Type= 3
Dn Slope=0.001
Boundary for River Rch & Prof#=Jeffries Creek,Reach 1         , 4
Up Type= 0
Dn Type= 3
Dn Slope=0.001
Boundary for River Rch & Prof#=Jeffries Creek,Reach 1         , 5
Up Type= 0
Dn Type= 3
Dn Slope=0.001
Boundary for River Rch & Prof#=Jeffries Creek,Reach 1         , 6
Up Type= 0
Dn Type= 3
Dn Slope=0.001
DSS Import GetInterval= 0
DSS Import GetPeak= 0
DSS Import FillOption= 0

--- JefferiesCreek.g09 (geometry) ---

Geom Title=Revised Conditions
Program Version=6.60

River Reach=Jeffries Creek  ,Reach 1
Reach XY= 30
2335787.80950891862993.8813729372337464.07795542 861908.02190727
2339089.21631837861378.6806565792342308.45851559861416.751611748
2345206.75515026858718.3807162582347280.75091658857955.196118519
2348647.78339062 856795.909827032350837.43490903856049.122422483
2354029.50878266857027.2526658772354893.17670063857687.430505591
2355470.73960621856899.8645953622359789.95818852855202.615512283
2361881.93875369854936.7846465092364051.78147794853543.620090677
2370303.06735514853262.9128491472373640.99274345  853752.0994661
2375952.64086598853314.5193154342382028.92283601850417.212743568
2384315.59316097847861.7216162152385021.61054416847609.799703038
2387550.96028141848130.2499249152388847.92850186848987.218148092
2394263.40564682848766.4994823412399209.56922582847865.899690878
2401686.90246515846381.664745779 2404307.8068821844063.213199419
2405339.06979396844167.2242489812406251.94919607843739.716984346
 2406409.0834736842865.3289155492407193.46327181841831.692337837

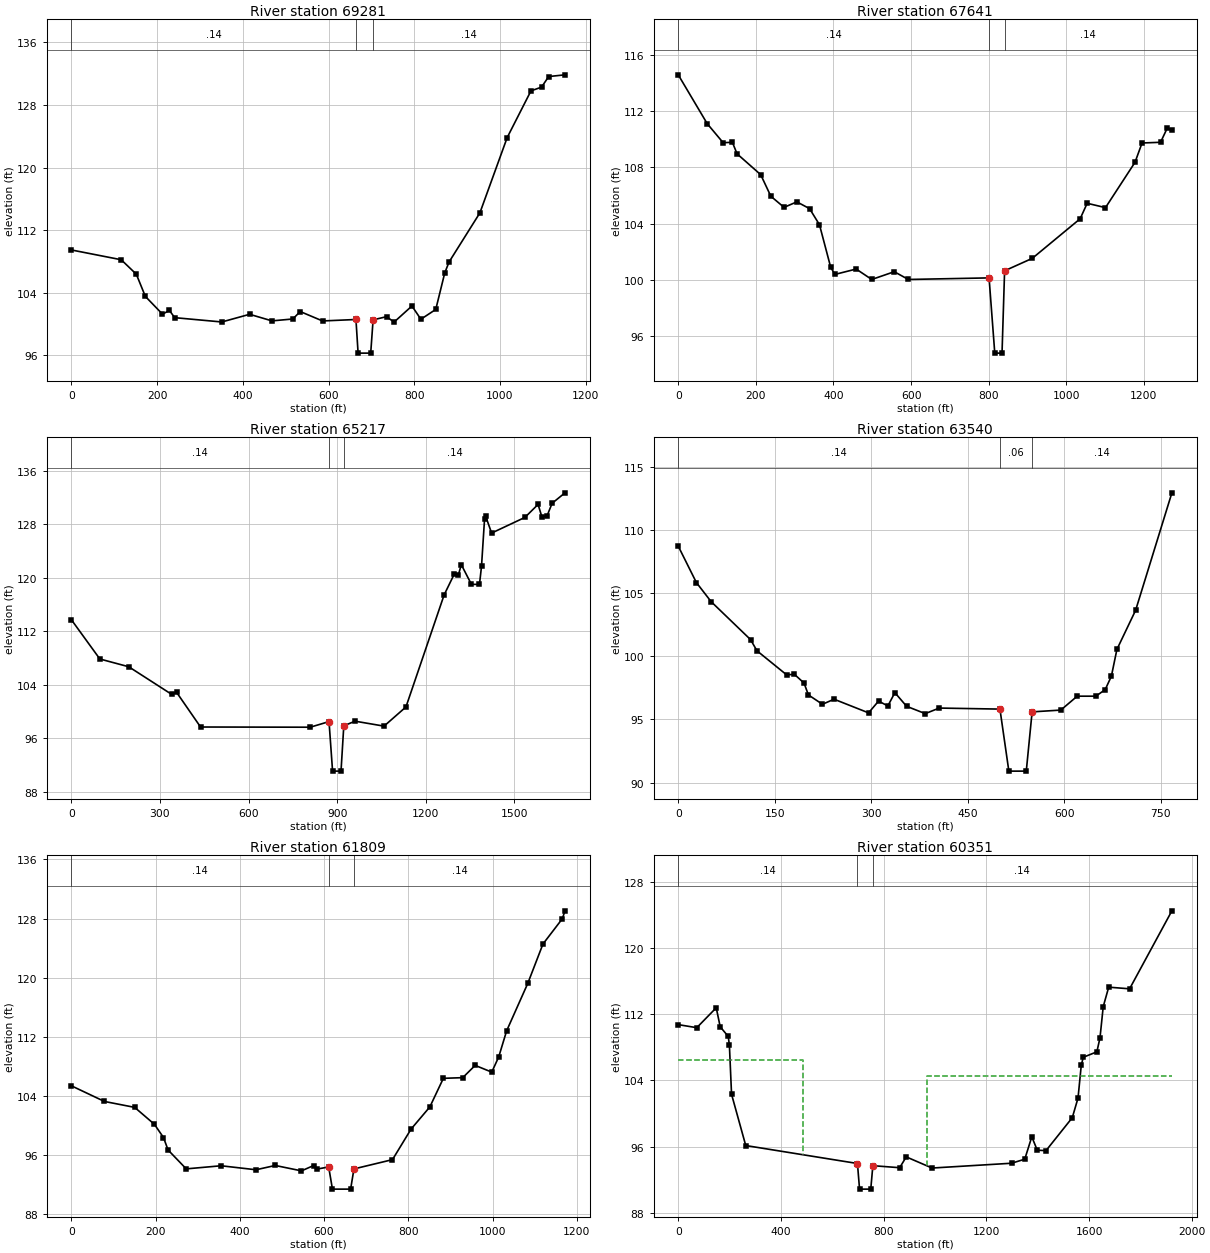
Type RM Length L Ch R = 1 ,69281   ,1640,1640,1640
XS GIS Cut Line= 6
2348168.61103781858002.5228116372348085.68674509857986.342461839
2347842.98149813857808.3586140642347784.32773011857638.464941187
2347667.02019408857302.7226828822347622.52423213857076.197785713
#Sta/Elev= 30
       0  109.48   116.3  108.23   151.6  106.38   172.6  103.55   212.6  101.28
   228.9  101.75   241.1  100.83     351  100.28     416  101.26     468  100.42
   516.6  100.66     534  101.61   586.1  100.41     664 100.596  669.01    96.3
  698.42    96.3     704 100.548   735.5  100.96   752.9  100.26   794.6  102.32
   815.5  100.63   850.2  101.88   871.1  106.53   881.1  107.93   953.2  114.22
  1016.8  123.83  1072.3   129.8    1097  130.28  1113.7  131.631151.693  131.85
#Mann= 3 ,0,0
       0     .14       0     664     .06       0     704     .14       0
Bank Sta=664,704
XS Rating Curve= 0 ,0
Exp/Cntr(USF)=0,0
Exp/Cntr=0.3,0.1

Type RM Length L Ch R = 1 ,67641   ,2423.2,2423.2,2423.2
XS GIS Cut Line= 5
2349319.43841718857422.052762641  2349173.815269857151.031903528
2349062.57536414856918.4393751852348900.77186616856576.629485706
2348761.21634915856279.315558172
#Sta/Elev= 30
       0  114.56    74.7  111.09   115.7  109.74   139.5  109.77   151.6  108.95
   212.5  107.47   238.6  105.94   272.7  105.15   305.6  105.54   338.4  105.06
   363.9  103.92     393  100.88   403.9  100.39   458.5  100.77   498.7  100.03
   556.7  100.58     593  100.03     801 100.142  815.68    94.8  834.38    94.8
     841 100.645   912.4  101.53  1035.7  104.34  1053.8  105.44    1101  105.13
  1177.1  108.35  1195.2  109.72  1242.9  109.77  1260.2  110.781272.101  110.63
#Mann= 3 ,0,0
       0     .14       0     801     .06       0     841     .14       0
Bank Sta=801,841
XS Rating Curve= 0 ,0
Exp/Cntr(USF)=0,0
Exp/Cntr=0.3,0.1

Type RM Length L Ch R = 1 ,65217   ,1677.7,1677.7,1677.7
XS GIS Cut Line= 3
2350794.21114314856908.617416703 2351074.7346593855752.613916061
2351210.37240337855290.212515803
#Sta/Elev= 30
       0  113.72    96.5  107.85   194.4  106.69   339.6  102.57   356.5  102.86
   437.5   97.69   808.9   97.66   872.5  98.498   884.5    91.1  913.11    91.1
   922.5  97.877   960.8   98.56  1058.8   97.82    1133  100.69  1262.3  117.43
  1296.5  120.53  1310.1  120.35  1320.4  121.94  1354.6     119  1381.9  118.99
  1388.8  121.69    1399  128.69  1402.5  129.22    1423  126.66  1535.8     129
  1580.3  130.94  1593.5  129.04    1611  129.26  1627.9  131.111671.438  132.67
#Mann= 3 ,0,0
       0     .14       0   872.5     .06       0   922.5     .14       0
Bank Sta=872.5,922.5
XS Rating Curve= 0 ,0
Exp/Cntr(USF)=0,0
Exp/Cntr=0.3,0.1

Type RM Length L Ch R = 1 ,63540   ,1730.3,1730.3,1730.3
XS GIS Cut Line= 2
2352340.75740834857036.9334446012352670.04775216856343.949288199
#Sta/Elev= 30
       0   108.7    28.2  105.82    51.1  104.31   112.3  101.31   122.4  100.42
   168.4   98.52   180.5   98.56   195.5   97.87   202.3   96.93   224.1   96.19
   242.2   96.59   295.8   95.51   311.3   96.44   325.8   96.06   336.7   97.11
   354.9   96.03   383.9   95.45   405.7   95.89     500  95.808  513.85    90.9
  540.93    90.9     550  95.588   594.6   95.73   620.1   96.83   649.1   96.83
   663.6   97.35   673.2   98.41   681.8  100.53   710.9  103.63 767.241  112.92
#Mann= 3 ,0,0
       0     .14       0     500     .06       0     550     .14       0
Bank Sta=500,550
XS Rating Curve= 0 ,0
Exp/Cntr(USF)=0,0
Exp/Cntr=0.3,0.1

Type RM Length L Ch R = 1 ,61809   ,1458.5,1458.5,1458.5
XS GIS Cut Line= 4
2353864.97400072 857631.716810812353834.01087884857559.469526419
2354158.38644141856841.4199856362354173.13078516856536.212069944
#Sta/Elev= 30
       0  105.38    78.6  103.26   150.4  102.46   197.2  100.17   218.8   98.38
   229.6    96.7   272.8   94.14   355.6   94.56   438.4   94.02   484.2    94.6
   546.4   93.87   575.2   94.59   583.4   94.11     611  94.401  619.93    91.4
  663.12    91.4     671  94.134   762.5   95.39   806.6   99.52   851.2  102.52
   883.3  106.39   929.3  106.48   958.8  108.14   998.2  107.23  1014.7  109.28
  1033.5  112.81  1083.7  119.23  1119.8  124.56  1165.8  127.981172.084  129.05
#Mann= 3 ,0,0
       0     .14       0     611     .06       0     671     .14       0
Bank Sta=611,671
XS Rating Curve= 0 ,0
Exp/Cntr(USF)=0,0
Exp/Cntr=0.5,0.3

Type RM Length L Ch R = 1 ,60351   ,191.7,191.7,191.7
XS GIS Cut Line= 4
 2355455.0336001857937.1289831522355389.50318341857857.036251653
2354320.99333364856976.0162051632354484.81937534856573.732258315
#Sta/Elev= 30
       0  110.74    72.2  110.37     148  112.78   163.4  110.48   194.8  109.31
   199.3  108.22   207.6  102.32   262.9   96.12     698  93.948  706.18   90.85
  749.86   90.85     758  93.686   862.5   93.44     888   94.75   988.7    93.4
  1298.1   93.98  1349.7   94.47  1377.1   97.18  1398.3   95.56  1432.3    95.5
  1534.8   99.49  1557.1  101.86  1569.7   105.8  1577.4  106.79  1630.5  107.45
  1642.7  109.14  1655.3  112.91  1676.6  115.27    1758  115.071922.734   124.5
#Mann= 3 ,0,0
       0     .14       0     698     .06       0     758     .14       0
#XS Ineff= 2 , 0
             486   106.5     970           104.5
Permanent Ineff=
       F       F
Bank Sta=698,758
XS Rating Curve= 0 ,0
Exp/Cntr(USF)=0,0
Exp/Cntr=0.5,0.3

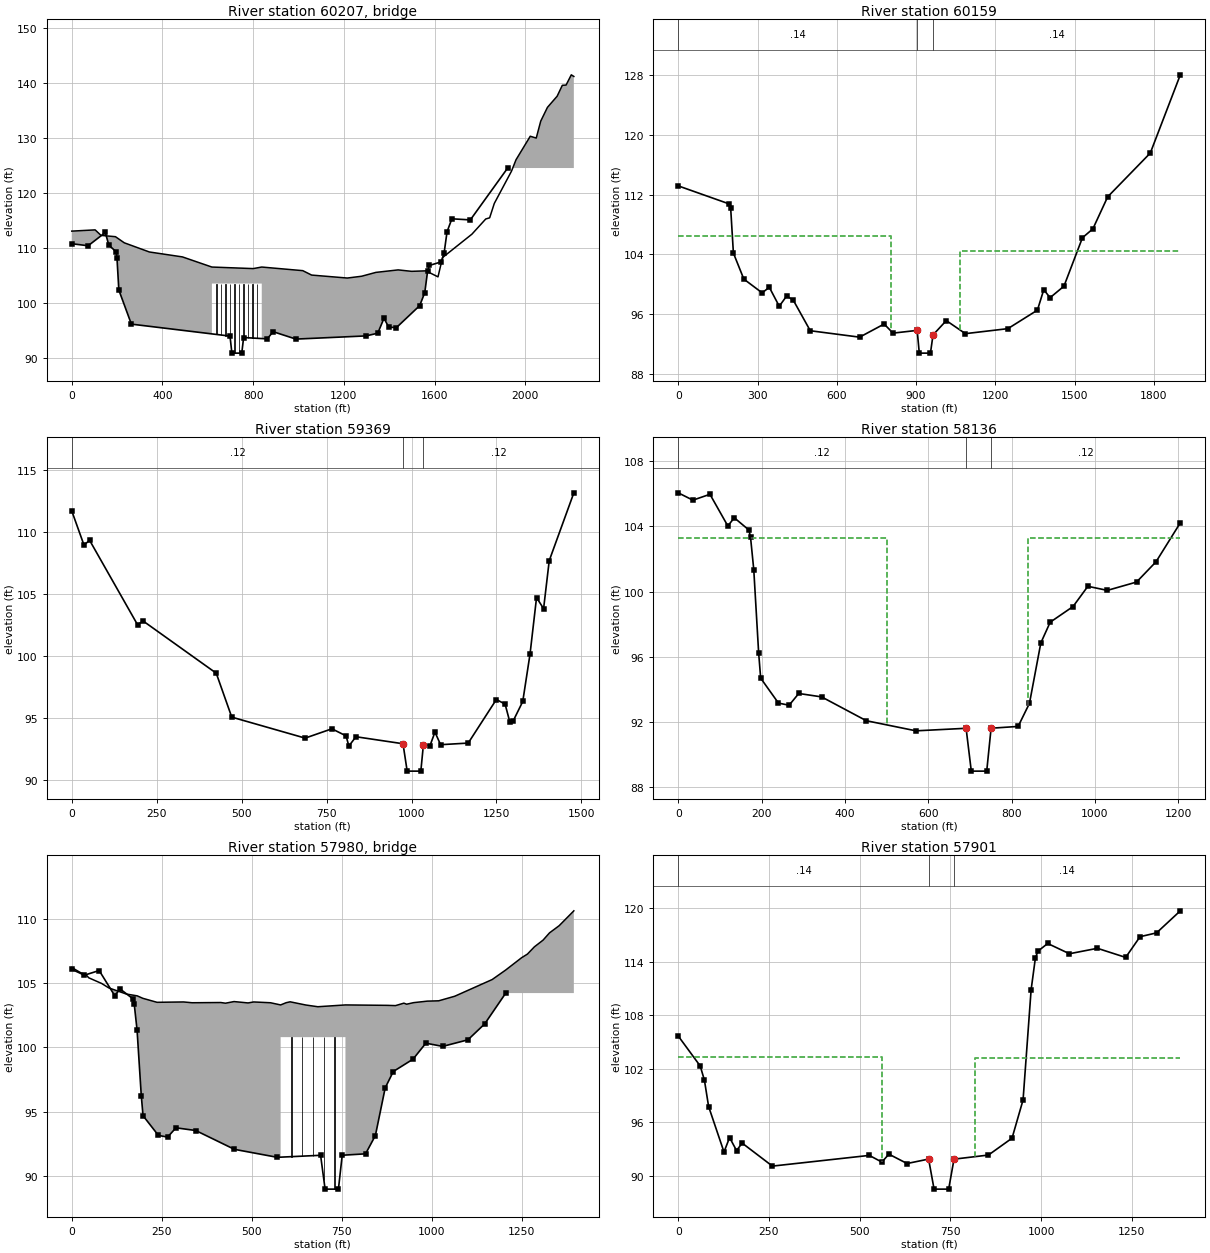
Type RM Length L Ch R = 3 ,60207   ,,,
Bridge Culvert--1,0,-1,-1, 0
Deck Dist Width WeirC Skew NumUp NumDn MinLoCord MaxHiCord MaxSubmerge Is_Ogee
132,18,2.6,0, 39, 39, , , 0.98, 0, 2,2,,
       0 103.073 128.995 192.671 231.584 342.188 488.082  617.99     618     618
 800.146     838     838  838.011018.9961057.9921215.3461278.4681341.6591439.638
1498.985 1561.941615.4231635.4791765.0151826.013  1843.2 1863.711939.698 1959.52
2022.2922048.723 2068.522098.1152140.8632163.7532180.3112203.318 2214.61
 113.031 113.257 112.254 112.019 110.907  109.24 108.344   106.5   106.5   106.5
 106.218   106.5   106.5   106.5 105.844  105.04 104.502 104.828  105.53 105.982
  105.72  105.81 104.715 108.226 112.476 115.238 115.448 118.063 123.938 126.009
 130.278 129.949 133.027 135.528 137.556 139.541 139.583 141.444  141.15
                                                                           103.5
   103.5   103.5
                                                                                
                                                                        
       0 103.073 128.995 192.671 231.584 342.188 488.082 660.937 771.361 800.146
  823.99     824     824    1044    1044 1044.011215.3461278.4681341.6591439.638
1498.985 1561.941615.4231635.4791765.0151826.013  1843.2 1863.711939.698 1959.52
2022.2922048.723 2068.522098.1152140.8632163.7532180.3112203.318 2214.61
 113.031 113.257 112.254 112.019 110.907  109.24 108.344 107.311 107.056 106.718
   106.5   106.5   106.5   106.5   106.5   106.5 104.502 104.828  105.53 105.982
  105.72  105.81 104.715 108.226 112.476 115.238 115.448 118.063 123.938 126.009
 130.278 129.949 133.027 135.528 137.556 139.541 139.583 141.444  141.15
                                                                                
                   103.5   103.5
                                                                                
                                                                        
Pier Skew, UpSta & Num, DnSta & Num=  ,638, 2 ,844, 2 , 0 , 0 , 0 ,,
       2       2
   90.75   103.5
       2       2
   90.75   103.5
Pier Skew, UpSta & Num, DnSta & Num=  ,658, 2 ,864, 2 , 0 , 0 , 0 ,,
       2       2
   90.75   103.5
       2       2
   90.75   103.5
Pier Skew, UpSta & Num, DnSta & Num=  ,678, 2 ,884, 2 , 0 , 0 , 0 ,,
       2       2
   90.75   103.5
       2       2
   90.75   103.5
Pier Skew, UpSta & Num, DnSta & Num=  ,698, 2 ,904, 2 , 0 , 0 , 0 ,,
       2       2
   90.75   103.5
       2       2
   90.75   103.5
Pier Skew, UpSta & Num, DnSta & Num=  ,718, 2 ,924, 2 , 0 , 0 , 0 ,,
       2       2
   90.75   103.5
       2       2
   90.75   103.5
Pier Skew, UpSta & Num, DnSta & Num=  ,738, 2 ,944, 2 , 0 , 0 , 0 ,,
       2       2
   90.75   103.5
       2       2
   90.75   103.5
Pier Skew, UpSta & Num, DnSta & Num=  ,758, 2 ,964, 2 , 0 , 0 , 0 ,,
       2       2
   90.75   103.5
       2       2
   90.75   103.5
Pier Skew, UpSta & Num, DnSta & Num=  ,778, 2 ,984, 2 , 0 , 0 , 0 ,,
       2       2
   90.75   103.5
       2       2
   90.75   103.5
Pier Skew, UpSta & Num, DnSta & Num=  ,798, 2 ,1004, 2 , 0 , 0 , 0 ,,
       2       2
   90.75   103.5
       2       2
   90.75   103.5
Pier Skew, UpSta & Num, DnSta & Num=  ,818, 2 ,1024, 2 , 0 , 0 , 0 ,,
       2       2
   90.75   103.5
       2       2
   90.75   103.5
Abutment Skew #Up #Dn= , 2 , 2
     618     638
   102.5    82.5
     824     844
   102.5    82.5
Abutment Skew #Up #Dn= , 2 , 2
     818  838.01
    82.5   102.5
    1024 1043.99
    82.5   102.5
BR Coef=-1 , 1 , 1 ,1.25, 0 ,,,0.8,0,2,0,
WSPro=,,,, 1 ,,,, 0 ,,,, 0 ,,,,-1 ,-1 ,-1 , 0 , 0 , 0 , 0 , 0
BC Design=,, 0 ,, 0 ,,,,,,
BC Use User HTab Curves=0
BC User HTab FreeFlow(D)= 0

Type RM Length L Ch R = 1 ,60159   ,790.7,790.7,790.7
XS GIS Cut Line= 5
 2355657.0857182857933.4884044472355515.10314872857671.366737723
2354859.79898191857196.271216785 2354570.3729749856996.039388038
2354606.77876195856557.349654145
#Sta/Elev= 30
       0  113.16   193.8  110.73   198.4  110.18   208.7  104.16   248.2  100.67
   317.4   98.83   344.6   99.57   382.2   97.03   410.1    98.4   434.9   97.87
   499.6   93.75   686.2   92.89   779.1   94.65   812.6   93.43     904  93.796
  912.07   90.75  954.26   90.75     964  93.189  1014.2   95.11  1086.5   93.36
  1247.3   94.03    1359   96.51    1383   99.25  1406.9   98.18  1459.4   99.72
  1529.3  106.21  1568.8   107.4  1624.8  111.69  1786.1  117.561899.648  128.04
#Mann= 3 ,0,0
       0     .14       0     904     .06       0     964     .14       0
#XS Ineff= 2 , 0
          803.15   106.5 1064.85           104.5
Permanent Ineff=
       F       F
Bank Sta=904,964
XS Rating Curve= 0 ,0
Exp/Cntr(USF)=0,0
Exp/Cntr=0.5,0.3

Type RM Length L Ch R = 1 ,59369   ,1232.9,1232.9,1232.9
XS GIS Cut Line= 3
2356154.14524489857748.9576627282356109.74926591857539.224934446
2355335.11597751856541.080855323
#Sta/Elev= 30
       0  111.71   35.84  108.97   52.61  109.34  193.48  102.55  210.24  102.84
  425.23   98.64  470.92    95.1   686.9   93.41  765.69   94.16  807.34   93.59
  815.65   92.77  836.42   93.52     975  92.956  987.25   90.75 1027.47   90.75
    1035  92.865 1054.53   92.81    1069   93.89 1085.62   92.88 1166.91   93.01
 1249.76   96.52 1275.48   96.15 1289.13   94.74 1298.87   94.77 1327.46   96.36
 1348.87  100.18 1368.05  104.73 1388.81  103.84 1405.43  107.71 1477.85  113.17
#Mann= 3 ,0,0
       0     .12       0     975     .06       0    1035     .12       0
Bank Sta=975,1035
XS Rating Curve= 0 ,0
Exp/Cntr(USF)=0,0
Exp/Cntr=0.5,0.3

Type RM Length L Ch R = 1 ,58136   ,234.6,234.6,234.6
XS GIS Cut Line= 3
2357302.15484009 856912.774707612357260.86198695856852.509462489
2356306.66227254856243.160872935
#Sta/Elev= 30
       0  106.06   35.18  105.61   76.11  105.97  119.03  104.03   134.6  104.53
 169.641  103.78  173.53  103.34  181.32  101.35     193   96.26  197.89    94.7
  240.57   93.17  266.18   93.04  289.34   93.76  344.21   93.55 451.499   92.09
  570.63   91.47     691  91.626  703.49      89 740.509      89     751   91.63
   815.9   91.74  843.15   93.16 870.401   96.86  892.88   98.13  947.75   99.09
   983.3  100.331030.019  100.081100.101  100.59 1146.82  101.83 1205.22  104.22
#Mann= 3 ,-1,0
       0     .12       0     691     .06       0     751     .12       0
#XS Ineff= 2 , 0
       0     500   103.3     840       0  103.27
Permanent Ineff=
       F       F
Bank Sta=691,751
XS Rating Curve= 0 ,0
Exp/Cntr(USF)=0,0
Exp/Cntr=0.5,0.3

Type RM Length L Ch R = 3 ,57980   ,,,
Bridge Culvert--1,0,-1,-1, 0
Deck Dist Width WeirC Skew NumUp NumDn MinLoCord MaxHiCord MaxSubmerge Is_Ogee
80,76,2.6,0, 44, 44, , , 0.98, 0, 2,2,,
       0  26.166  39.189  47.111  83.058 102.561 151.407 181.774 197.375 236.755
 310.389 334.141 413.879 426.778 450.621 489.581 505.186 551.919  579.99     580
     580 595.422 606.465 650.054 683.289     760     760 876.427 899.023  922.27
 929.902 948.981 987.141 1018.961063.4591167.4081204.6491248.8161265.3611284.642
1308.6741326.7591353.4711394.276
 106.203 105.777 105.656 105.406 104.964 104.625 104.146 104.005 103.813 103.503
 103.531  103.47 103.487 103.434 103.561 103.455 103.531 103.469   103.3   103.3
   103.3 103.474 103.542 103.293  103.16   103.3   103.3 103.267 103.247 103.438
 103.356 103.476 103.594  103.62 103.974  105.27 106.003 106.958 107.247 107.809
 108.328 108.896 109.451 110.605
                                                                                
                                                                                
   100.8   100.8   100.8   100.8   100.8   100.8
                                                                                
                                
       0  26.166  39.189  47.111  83.058 102.561 151.407 181.774 197.375 236.755
 310.389 334.141 413.879 426.778 450.621 489.581 505.186 551.919 595.422  599.99
     600     600 606.465 650.054 683.289     780     780 876.427 899.023  922.27
 929.902 948.981 987.141 1018.961063.4591167.4081204.6491248.8161265.3611284.642
1308.6741326.7591353.4711394.276
 106.203 105.777 105.656 105.406 104.964 104.625 104.146 104.005 103.813 103.503
 103.531  103.47 103.487 103.434 103.561 103.455 103.531 103.469 103.474   103.3
   103.3   103.3 103.542 103.293  103.16   103.3   103.3 103.267 103.247 103.438
 103.356 103.476 103.594  103.62 103.974  105.27 106.003 106.958 107.247 107.809
 108.328 108.896 109.451 110.605
                                                                                
                                                                                
           100.8   100.8   100.8   100.8   100.8
                                                                                
                                
Pier Skew, UpSta & Num, DnSta & Num=  ,610, 2 ,630, 2 , 0 , 0 , 0 ,,
     1.3     1.3
    88.5   100.8
     1.3     1.3
    88.5   100.8
Pier Skew, UpSta & Num, DnSta & Num=  ,640, 2 ,660, 2 , 0 , 0 , 0 ,,
     1.3     1.3
    88.5   100.8
     1.3     1.3
    88.5   100.8
Pier Skew, UpSta & Num, DnSta & Num=  ,670, 2 ,690, 2 , 0 , 0 , 0 ,,
     1.3     1.3
    88.5   100.8
     1.3     1.3
    88.5   100.8
Pier Skew, UpSta & Num, DnSta & Num=  ,700, 2 ,720, 2 , 0 , 0 , 0 ,,
     1.3     1.3
    88.5   100.8
     1.3     1.3
    88.5   100.8
Pier Skew, UpSta & Num, DnSta & Num=  ,730, 2 ,750, 2 , 0 , 0 , 0 ,,
     1.3     1.3
    88.5   100.8
     1.3     1.3
    88.5   100.8
Abutment Skew #Up #Dn= , 2 , 2
  580.01     600
    99.8    79.8
  600.01     620
    99.8    79.8
Abutment Skew #Up #Dn= , 2 , 2
     740  760.01
    79.8    99.8
     760  780.01
    79.8    99.8
BR Coef=-1 , 1 , 1 ,1.25, 0 ,,,0.8,0,2,0,
WSPro=,,,, 1 ,,,, 0 ,,,, 0 ,,,,-1 ,-1 ,-1 , 0 , 0 , 0 , 0 , 0
BC Design=,, 0 ,, 0 ,,,,,,
BC Use User HTab Curves=0
BC User HTab FreeFlow(D)= 0

Type RM Length L Ch R = 1 ,57901   ,681.8,681.8,681.8
XS GIS Cut Line= 4
 2357503.4505629856755.8917374742356949.68207244856415.692664835
2356853.29233519856321.1929224352356335.43374684856020.683741604
#Sta/Elev= 30
       0  105.66    60.6   102.3    72.2   100.7    83.7   97.76   126.1   92.66
   141.5   94.28   160.7   92.82   176.1   93.66   259.5   91.08   526.6   92.28
 561.199   91.53   580.5   92.42   630.6   91.37 689.999  91.867 705.041    88.5
  745.24    88.5     760  91.859   854.9   92.32   919.9   94.21   950.3    98.5
   972.5  110.85   984.4  114.45   991.7  115.181018.099  116.03  1078.1  114.88
  1155.1  115.49    1233  114.471272.699  116.79  1318.2  117.22 1383.64  119.69
#Mann= 3 ,0,0
       0     .14       0 689.999    .055       0     760     .14       0
#XS Ineff= 2 , 0
       0 560.865   103.3 819.135       0  103.25
Permanent Ineff=
       F       F
Bank Sta=689.999,760
XS Rating Curve= 0 ,0
Exp/Cntr(USF)=0,0
Exp/Cntr=0.5,0.3

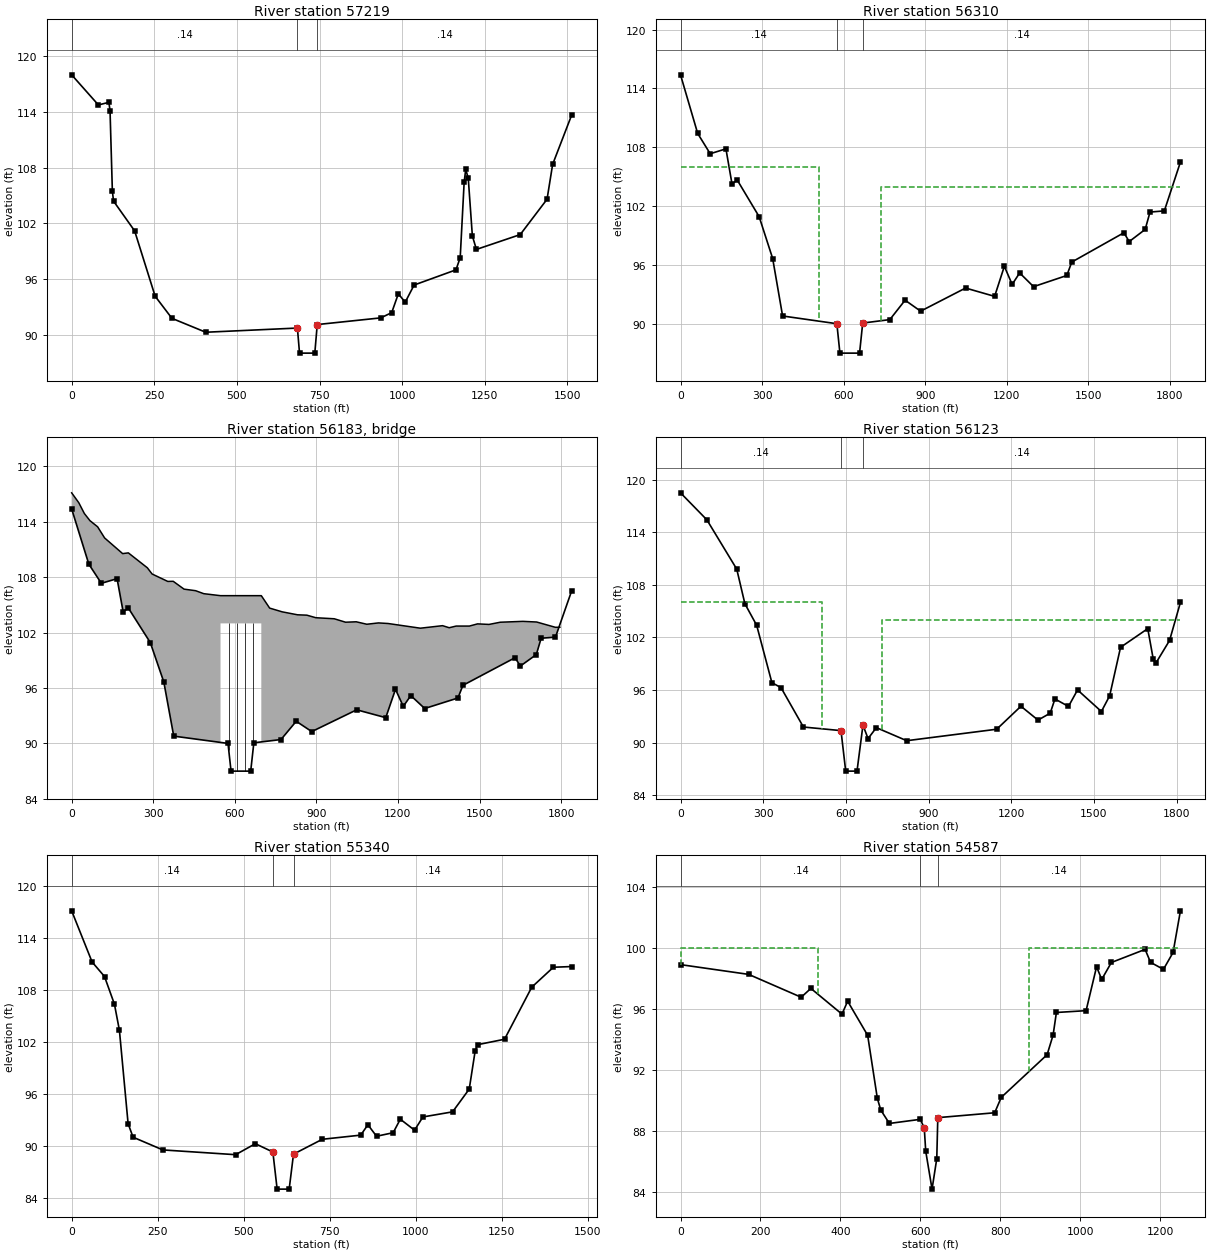
Type RM Length L Ch R = 1 ,57219   ,909.4,909.4,909.4
XS GIS Cut Line= 4
2357881.25920478856709.6585110912357830.03374643 856579.08381333
2357162.09394634855709.2554420872357263.54044229855453.128150324
#Sta/Elev= 30
       0  117.94   80.86  114.71  112.58  114.99   116.1  114.11  123.15  105.48
  126.68   104.4  190.51  101.21  252.56    94.2  303.37   91.83  405.67   90.34
     683  90.789   689.4    88.1  735.63    88.1     743  91.163  935.16   91.88
  968.26   92.44  988.34   94.46 1009.11   93.56 1036.05    95.4  1162.7   97.03
 1175.55   98.34 1187.52  106.45 1192.28   107.8 1199.93  106.84 1212.34  100.66
 1224.61   99.22 1357.12  100.81 1438.29   104.6 1455.22  108.34 1512.45   113.6
#Mann= 3 ,-1,0
       0     .14       0     683    .055       0     743     .14       0
Bank Sta=683,743
XS Rating Curve= 0 ,0
Exp/Cntr(USF)=0,0
Exp/Cntr=0.5,0.3

Type RM Length L Ch R = 1 ,56310   ,186.5,186.5,186.5
XS GIS Cut Line= 6
2358272.32302269856476.9577527192358377.04816701856278.428278003
2358341.62459168856038.124297366 2358341.2133349 855677.83013109
2358531.11943133855243.2042131532358823.40587017854793.223716251
#Sta/Elev= 30
       0  115.39   63.14  109.41  109.16  107.34  167.01  107.84  189.27  104.27
  208.74  104.65  289.18  100.92  338.93   96.65  375.41   90.79     575      90
  586.19      87  658.48      87     670  90.066  769.85   90.42  825.92    92.4
  883.05   91.28 1048.37   93.64 1155.18   92.79 1190.99   95.86 1219.64   94.01
  1247.3   95.18 1298.41   93.78 1420.71   94.92 1438.94   96.29 1630.66   99.28
 1650.22   98.38 1708.91   99.62 1726.69  101.39 1779.34  101.51 1838.53  106.49
#Mann= 3 ,-1,0
       0     .14       0     575    .055       0     670     .14       0
#XS Ineff= 2 , 0
       0   507.5     106  737.51       0  103.93
Permanent Ineff=
       F       F
Bank Sta=575,670
XS Rating Curve= 0 ,0
Exp/Cntr(USF)=0,0
Exp/Cntr=0.5,0.3

Type RM Length L Ch R = 3 ,56183   ,,,
Bridge Culvert--1,0,-1,-1, 0
Deck Dist Width WeirC Skew NumUp NumDn MinLoCord MaxHiCord MaxSubmerge Is_Ogee
40,76.33,2.6,0, 42, 42, , , 0.98, 0, 2,2,,
       0  26.267  46.671  67.241  95.497 121.231 187.469   208.5 278.375 295.851
 353.474 373.502 413.255 456.058 485.692  547.49   547.5   697.5  697.51 728.155
 774.214 830.733 864.798 898.064 965.7411007.3661046.6271085.5081128.5871163.712
1282.5441364.0711388.3981414.113  1462.81492.6951534.8771576.3051659.2731709.968
1778.9091795.562
 117.137 116.063 114.899 114.125 113.458  112.25 110.555 110.634 109.019 108.348
 107.543 107.556 106.709 106.537 106.217     106     106     106     106 104.654
  104.25 103.929  103.89 103.612   103.5 103.126 103.172 102.906  103.05 102.986
 102.479 102.752 102.529 102.709 102.709 102.946 102.886 103.125 103.219 103.149
 102.576 102.581
                                                                                
                                                     103     103
                                                                                
                                                                                
                
       0  26.267  46.671  67.241  95.497 121.231 187.469   208.5 278.375 295.851
 353.474 373.502 413.255 456.058 485.692 547.154 547.155 697.155 697.156 728.155
 774.214 830.733 864.798 898.064 965.7411007.3661046.6271085.5081128.5871163.712
1282.5441364.0711388.3981414.113  1462.81492.6951534.8771576.3051659.2731709.968
1778.9091795.562
 117.137 116.063 114.899 114.125 113.458  112.25 110.555 110.634 109.019 108.348
 107.543 107.556 106.709 106.537 106.217     106     106     106     106 104.654
  104.25 103.929  103.89 103.612   103.5 103.126 103.172 102.906  103.05 102.986
 102.479 102.752 102.529 102.709 102.709 102.946 102.886 103.125 103.219 103.149
 102.576 102.581
                                                                                
                                                     103     103
                                                                                
                                                                                
                
Pier Skew, UpSta & Num, DnSta & Num=  ,577.5, 2 ,577.16, 2 , 0 , 0 , 0 ,,
     1.3     1.3
   86.75     103
     1.3     1.3
   86.75     103
Pier Skew, UpSta & Num, DnSta & Num=  ,607.5, 2 ,607.16, 2 , 0 , 0 , 0 ,,
     1.3     1.3
   86.75     103
     1.3     1.3
   86.75     103
Pier Skew, UpSta & Num, DnSta & Num=  ,637.5, 2 ,637.16, 2 , 0 , 0 , 0 ,,
     1.3     1.3
   86.75     103
     1.3     1.3
   86.75     103
Pier Skew, UpSta & Num, DnSta & Num=  ,667.5, 2 ,667.16, 2 , 0 , 0 , 0 ,,
     1.3     1.3
   86.75     103
     1.3     1.3
   86.75     103
Abutment Skew #Up #Dn= , 2 , 2
  547.49   567.5
     102      82
  547.17  567.17
     102      82
Abutment Skew #Up #Dn= , 2 , 2
   677.5  697.51
      82     102
  677.16  697.17
      82     102
BR Coef=-1 , 1 , 1 ,1.25, 0 ,,,0.8,0,2,0,
WSPro=,,,, 1 ,,,, 0 ,,,, 0 ,,,,-1 ,-1 ,-1 , 0 , 0 , 0 , 0 , 0
BC Design=,, 0 ,, 0 ,,,,,,
BC Use User HTab Curves=0
BC User HTab FreeFlow(D)= 0

Type RM Length L Ch R = 1 ,56123   ,783.1,783.1,783.1
XS GIS Cut Line= 6
2358683.52510089856470.7053037882358670.22928892 856163.36282453
2358506.57199231855846.3285156082358661.69412909855350.677233618
2358895.72416431855100.5764663672358918.82584161854817.329814299
#Sta/Elev= 30
       0  118.49   95.62  115.41     204  109.79  233.56  105.84  276.25  103.39
  331.53   96.84  364.67   96.27   445.9   91.78  582.31   91.37  599.37   86.75
   640.4   86.75     662  91.988  680.52   90.46  710.58   91.71  820.77   90.22
 1147.41   91.53 1235.27   94.15 1297.22   92.57 1341.45   93.36 1358.61   94.98
 1407.79   94.13 1440.71   96.01 1527.17   93.55 1557.19   95.34  1596.7  100.87
 1695.46     103 1715.21   99.55 1725.09   99.08 1774.52  101.65 1813.97  105.99
#Mann= 3 ,-1,0
       0     .14       0  582.31    .055       0     662     .14       0
#XS Ineff= 2 , 0
       0 512.075     106 732.245       0  103.93
Permanent Ineff=
       F       F
Bank Sta=582.31,662
XS Rating Curve= 0 ,0
Exp/Cntr(USF)=0,0
Exp/Cntr=0.5,0.3

Type RM Length L Ch R = 1 ,55340   ,753.4,753.4,753.4
XS GIS Cut Line= 4
2359425.08758033856068.2085669432359287.30695591855768.152984876
2359004.09122794854909.320425999  2359030.116457854691.933218583
#Sta/Elev= 30
       0  117.16   59.38  111.25   95.49  109.57  124.37  106.37  138.81  103.36
  164.09   92.57  178.53      91  265.18   89.53  476.73   88.98  534.02   90.25
     585   89.29  597.41      85  632.39      85     645  89.042  728.75   90.76
  840.47   91.24  861.26   92.44  886.42   91.11  934.79   91.52  955.52   93.08
  996.98   91.81 1021.17   93.34 1107.54   93.93 1155.91   96.56 1173.19  100.98
  1180.1  101.69 1258.59  102.32 1337.78  108.34 1400.57  110.64 1453.44  110.72
#Mann= 3 ,-1,0
       0     .14       0     585    .055       0     645     .14       0
Bank Sta=585,645
XS Rating Curve= 0 ,0
Exp/Cntr(USF)=0,0
Exp/Cntr=0.5,0.3

Type RM Length L Ch R = 1 ,54587   ,294.5,294.5,294.5
XS GIS Cut Line= 3
2360101.74353581855758.9676099142359783.31720382854970.556259074
2359588.89343381 854619.98111472
#Sta/Elev= 30
       0   98.92  170.56   98.28  302.03   96.78  326.26   97.36  404.11   95.67
  418.27   96.52  468.39   94.28  492.58   90.15  501.16   89.38  522.75    88.5
   600.4   88.77  610.11   88.18   613.7   86.68  629.52   84.19  641.35   86.19
  643.94   88.88  786.29    89.2  802.76   90.21  917.51   93.01  932.51    94.3
  940.77   95.78 1015.06    95.9 1041.32   98.78 1054.21   97.95 1078.34   99.06
 1162.81   99.92 1176.39   99.07 1208.67   98.61  1232.8   99.72 1251.17  102.45
#Mann= 3 ,-1,0
       0     .14       0   600.4    .055       0  643.94     .14       0
#XS Ineff= 2 , 0
          343.59     100 871.835             100
Permanent Ineff=
       F       F
Bank Sta=610.11,643.94
XS Rating Curve= 0 ,0
Exp/Cntr(USF)=0,0
Exp/Cntr=0.5,0.3