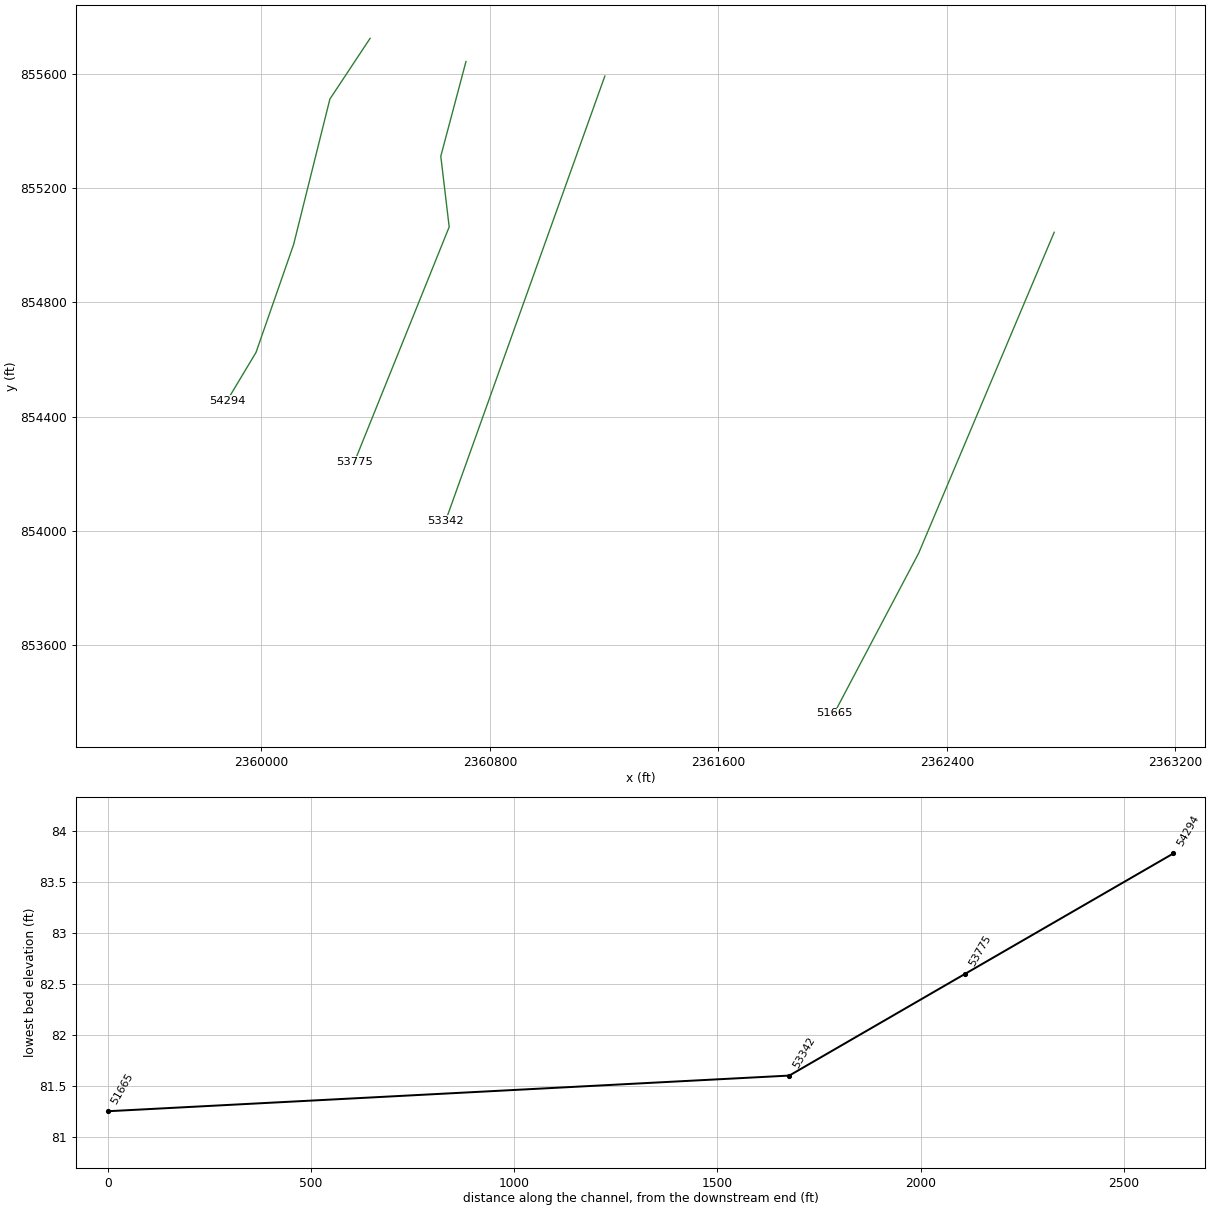
HEC-RAS study JefferiesCreek.prj: S-21-29 over Jeffries Creek

--- JefferiesCreek.g09 (geometry) --- (continued)

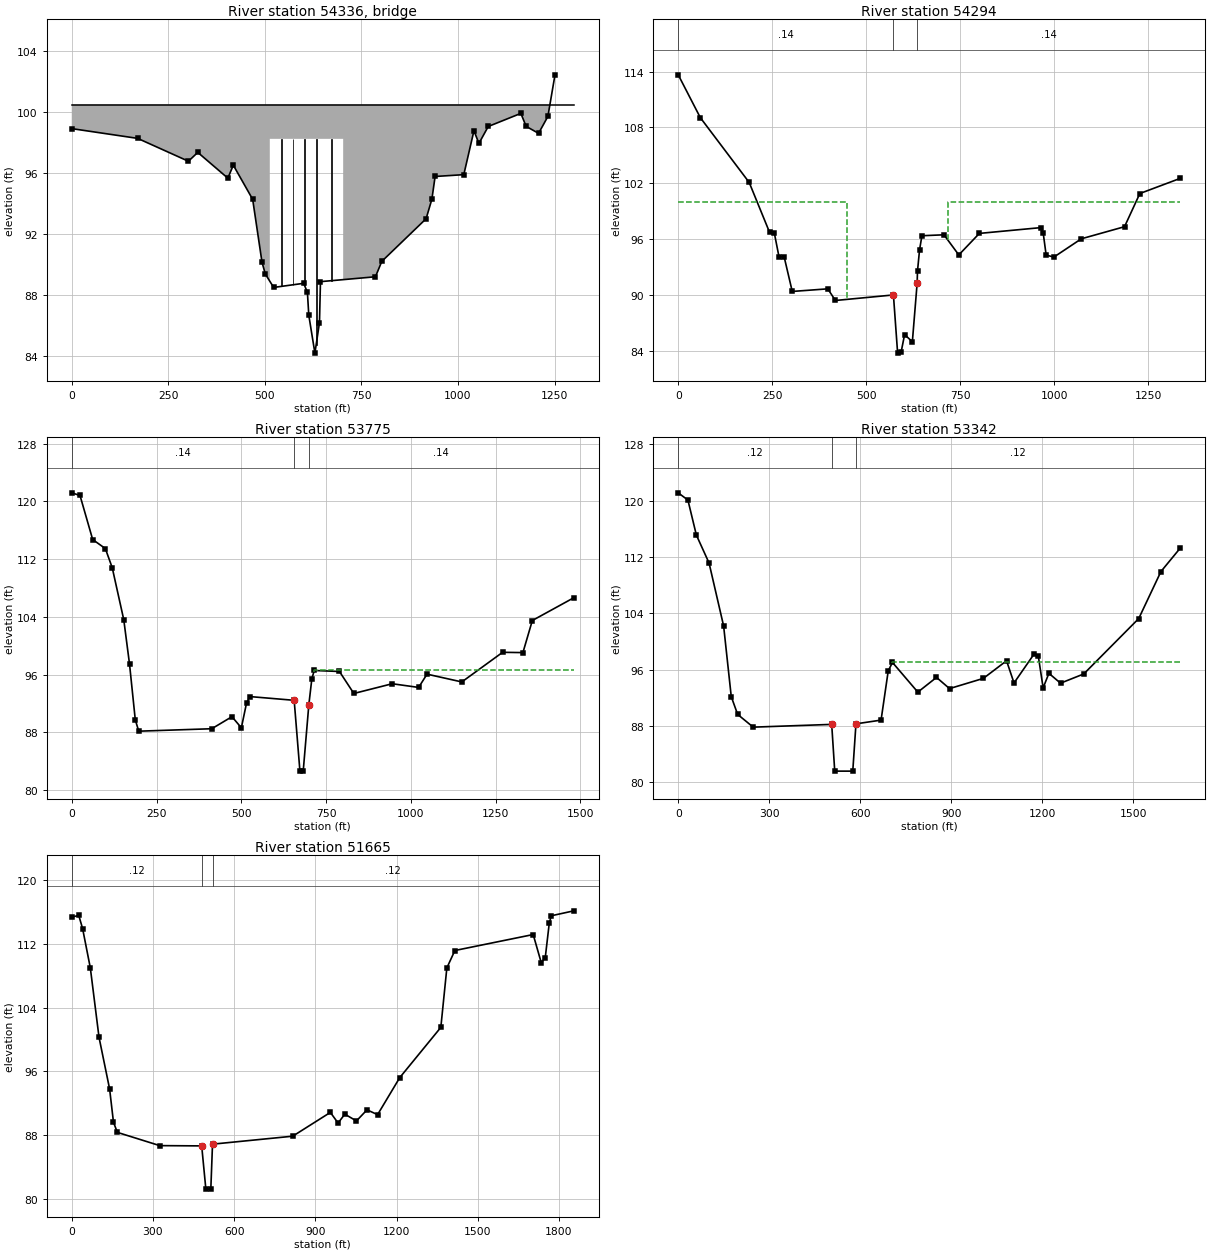
Type RM Length L Ch R = 3 ,54336   ,,,
Bridge Culvert--1,0,-1,-1, 0
Deck Dist Width WeirC Skew NumUp NumDn MinLoCord MaxHiCord MaxSubmerge Is_Ogee
169.125,46.25,2.6,0, 6, 6, , , 0.98, 0, 2,2,,
       0   512.7  512.71  702.71  702.72    1300
   100.5   100.5   100.5   100.5   100.5   100.5
                   98.25   98.25
       0   487.7  487.71  677.71  677.72    1300
   100.5   100.5   100.5   100.5   100.5   100.5
                   98.25   98.25
Pier Skew, UpSta & Num, DnSta & Num=  ,542.71, 2 ,517.71, 2 , 0 , 0 , 0 ,,
       2       2
       0     100
       2       2
       0     100
Pier Skew, UpSta & Num, DnSta & Num=  ,572.71, 2 ,547.71, 2 , 0 , 0 , 0 ,,
       2       2
       0     100
       2       2
       0     100
Pier Skew, UpSta & Num, DnSta & Num=  ,602.71, 2 ,577.71, 2 , 0 , 0 , 0 ,,
       2       2
       0     100
       2       2
       0     100
Pier Skew, UpSta & Num, DnSta & Num=  ,632.71, 2 ,607.71, 2 , 0 , 0 , 0 ,,
       2       2
       0     100
       2       2
       0     100
Pier Skew, UpSta & Num, DnSta & Num=  ,672.71, 2 ,647.71, 2 , 0 , 0 , 0 ,,
       2       2
       0     100
       2       2
       0     100
Abutment Skew #Up #Dn= , 3 , 3
   512.7  514.71  534.71
      97      97      87
  487.71  489.71  509.71
      97      97      87
Abutment Skew #Up #Dn= , 3 , 3
  680.71  700.71  702.72
      87      97      97
  650.71  675.71  677.72
      87      97      97
BR Coef=-1 , 1 , 1 ,1.25, 0 ,,,0.8,0,2,0,
WSPro=,,,, 1 ,,,, 0 ,,,, 0 ,,,,-1 ,-1 ,-1 , 0 , 0 , 0 , 0 , 0
BR D #Sta/Elev= 30
       0  113.65   58.76  109.05  188.61   102.1  242.62   96.76  255.46   96.66
  267.89   94.11  281.43   94.13  290.64   91.87  303.08    90.4  363.67   89.89
  397.48   90.68  417.77   89.43     572  90.025  583.16   83.78  592.43   83.89
  601.71   85.77  622.32      85     635  91.268     680    91.7  769.45   95.82
  856.01    97.2  935.92    96.7  965.09   97.24  970.25   96.63  977.98    94.3
 1001.17   94.13 1071.42   96.05 1186.31   97.35 1226.96  100.91 1334.58  102.54
BR D #Mann= 3
       0     .14     572    .055     635     .14
BC Design=,, 0 ,, 0 ,,4,542.71,517.71,30,2
BC Use User HTab Curves=0
BC User HTab FreeFlow(D)= 0

Type RM Length L Ch R = 1 ,54294   ,511.9,511.9,511.9
XS GIS Cut Line= 5
 2360380.3665763855725.2879017232360239.52416023855512.493381787
 2360112.4598066855002.7050714382359980.80276548  854624.5738022
2359879.76364091854456.175261244
#Sta/Elev= 30
       0  113.65   58.76  109.05  188.61   102.1  242.62   96.76  255.46   96.66
  267.89   94.11  281.43   94.13  303.08    90.4  397.48   90.68  417.77   89.43
     572  90.025  583.16   83.78  592.43   83.89  601.71   85.77  622.32      85
     635  91.268  636.03   92.61  641.44   94.86  647.72   96.38   706.4   96.48
  745.78   94.32  800.42   96.63  963.71   97.25  970.25   96.63  977.98    94.3
  998.59   94.09 1071.42   96.05 1186.31   97.35 1226.96  100.91 1334.58  102.54
#Mann= 3 ,-1,0
       0     .14       0     572    .055       0     635     .14       0
#XS Ineff= 2 , 0
          448.75     100 716.673             100
Permanent Ineff=
       F       F
Bank Sta=572,635
XS Rating Curve= 0 ,0
Exp/Cntr(USF)=0,0
Exp/Cntr=0.5,0.3

Type RM Length L Ch R = 1 ,53775   ,433.3,433.3,433.3
XS GIS Cut Line= 4
2360716.10312691855643.9925133852360627.90336733855312.193417812
2360657.30328719855064.3940932712360325.50419162854241.196337167
#Sta/Elev= 30
       0   121.2    24.3  120.83   61.65  114.72      99  113.47  119.37   110.8
  153.32   103.6  170.29   97.45  187.27   89.72  197.45   88.14  412.83   88.48
   472.3   90.15  500.04   88.61  515.26   92.03  525.17   92.94  655.78  92.422
  672.73    82.6  682.43    82.6     699  91.805  707.89  95.413  714.96   96.56
  789.25   96.42   831.7   93.37  944.91   94.72 1022.74   94.21  1047.5   96.05
 1150.09   94.97 1270.37   99.08 1330.25   99.04 1357.99  103.49 1480.41  106.65
#Mann= 3 ,0,0
       0     .14       0  655.78    .055       0     699     .14       0
#XS Ineff= 2 , 0
                          713.96           96.56
Permanent Ineff=
       F       F
Bank Sta=655.78,699
XS Rating Curve= 0 ,0
Exp/Cntr(USF)=0,0
Exp/Cntr=0.3,0.1

Type RM Length L Ch R = 1 ,53342   ,1676.9,1676.9,1676.9
XS GIS Cut Line= 2
2361202.43733539855593.2498283172360644.77218888854034.587410466
#Sta/Elev= 30
       0  121.09   31.94  120.06   59.75   115.1  101.63  111.13  149.67  102.19
  174.81   92.17  195.87   89.65   247.2   87.84     506  88.232  515.99    81.6
  575.47    81.6     586   88.31  668.76   88.84  692.42   95.84  706.36   97.02
  789.99   92.81  851.52    94.9  894.54   93.31 1006.06   94.76 1082.51   97.26
 1107.12   94.11 1173.33   98.22 1187.27    97.9 1203.14   93.41 1222.12   95.48
 1260.45   94.08 1337.12   95.39 1518.33  103.25 1591.51  109.92 1655.42  113.26
#Mann= 3 ,-1,0
       0     .12       0     506    .055       0     586     .12       0
#XS Ineff= 2 , 0
                          705.36           97.02
Permanent Ineff=
       F       F
Bank Sta=506,586
XS Rating Curve= 0 ,0
Exp/Cntr(USF)=0,0
Exp/Cntr=0.3,0.1

Type RM Length L Ch R = 1 ,51665   ,0,0,0
XS GIS Cut Line= 3
2362775.87278337855045.6412799452362301.29507704853921.283344873
2362005.32188384853359.954875019
#Sta/Elev= 30
       0  115.33   25.88  115.53   40.12  113.87   68.61  108.95  100.66  100.27
  139.84   93.79  154.09   89.63  168.33   88.36  325.03    86.7     480  86.665
   495.4   81.25  513.72   81.25     520  86.881  816.33   87.88   955.4   90.86
  983.89   89.53 1008.82   90.64 1051.74   89.79 1090.73   91.18  1129.9   90.58
 1211.82   95.22 1363.54  101.51 1385.79  108.96 1415.47  111.14 1704.79  113.14
 1734.43  109.63  1749.3  110.23 1764.14  114.55 1771.55  115.49 1854.99  116.11
#Mann= 3 ,-1,0
       0     .12       0     480    .055       0     520     .12       0
Bank Sta=480,520
XS Rating Curve= 0 ,0
Exp/Cntr(USF)=0,0
Exp/Cntr=0.3,0.1
LCMann Table=0

Chan Stop Cuts=-1
Use User Specified Reach Order=0
Composite Channel Slope=5

--- JefferiesCreek.g01 (geometry) ---

Geom Title=Corrected Effective
Program Version=6.60

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
River Reach=Jeffries Creek  ,Reach 1

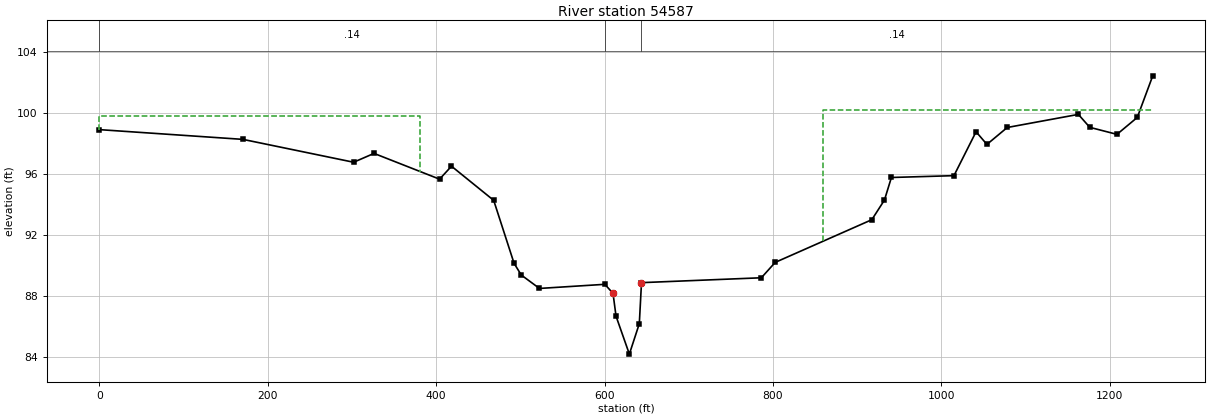
Type RM Length L Ch R = 1 ,54587   ,294.5,294.5,294.5
XS GIS Cut Line= 3
2360101.74353581855758.9676099142359783.31720382854970.556259074
2359588.89343381 854619.98111472
#Sta/Elev= 30
       0   98.92  170.56   98.28  302.03   96.78  326.26   97.36  404.11   95.67
  418.27   96.52  468.39   94.28  492.58   90.15  501.16   89.38  522.75    88.5
   600.4   88.77  610.11   88.18   613.7   86.68  629.52   84.19  641.35   86.19
  643.94   88.88  786.29    89.2  802.76   90.21  917.51   93.01  932.51    94.3
  940.77   95.78 1015.06    95.9 1041.32   98.78 1054.21   97.95 1078.34   99.06
 1162.81   99.92 1176.39   99.07 1208.67   98.61  1232.8   99.72 1251.17  102.45
#Mann= 3 ,-1,0
       0     .14       0   600.4    .055       0  643.94     .14       0
#XS Ineff= 2 , 0
       0  381.29   99.79  859.71       0  100.22
Permanent Ineff=
       F       F
Bank Sta=610.11,643.94
XS Rating Curve= 0 ,0
Exp/Cntr(USF)=0,0
Exp/Cntr=0.5,0.3