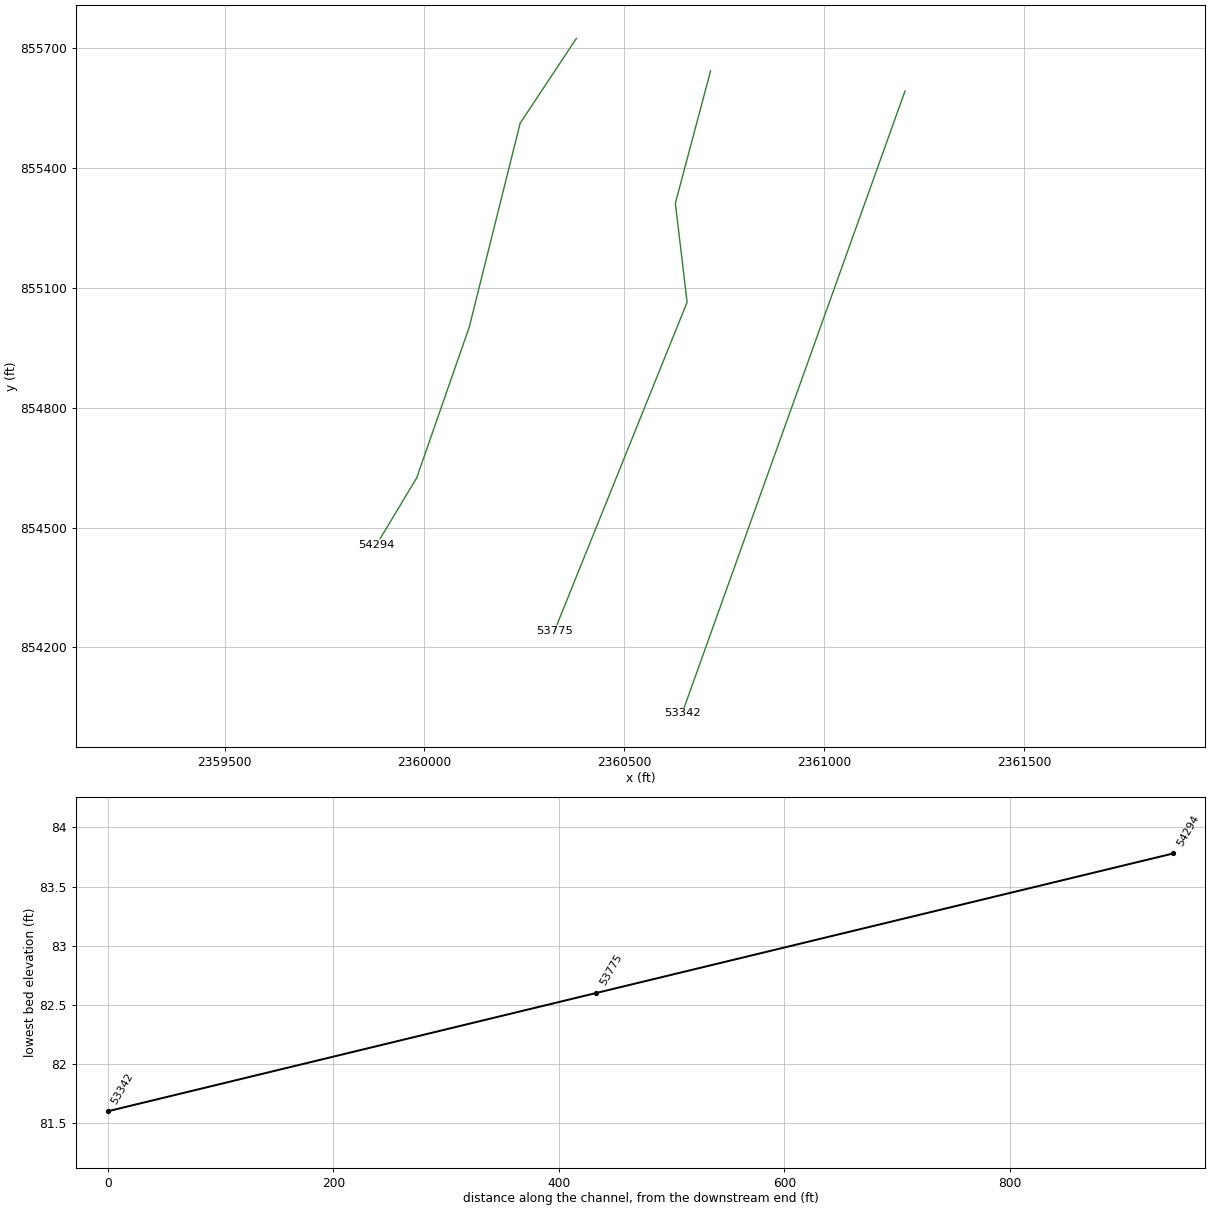
HEC-RAS study JefferiesCreek.prj: S-21-29 over Jeffries Creek

--- JefferiesCreek.g01 (geometry) --- (continued)

Type RM Length L Ch R = 3 ,54336   ,,,
Bridge Culvert--1,0,-1,-1, 0
Deck Dist Width WeirC Skew NumUp NumDn MinLoCord MaxHiCord MaxSubmerge Is_Ogee
174,36.5,2.6,0, 36, 37, , , 0.98, 0, 2,2,,
       0  14.718  49.333   92.34 134.298 194.088  249.67 261.202 317.333 367.274
 389.207 419.439 455.915 498.011 519.452 538.091  555.28  555.29  685.71  686.72
 716.544 751.525 792.205 805.513 816.603 885.054 935.466 993.9951037.809 1085.52
1136.0051180.6821232.1271239.3241281.973 1327.52
 103.241 102.906 101.938 101.344 101.031 100.469 100.156 100.129 100.125 100.156
 100.094  99.938   99.85  99.906 100.188 100.369  100.56  100.56  100.28  100.28
 100.313 100.313 100.375 100.531 100.502   100.5 100.413 100.563 100.472 100.438
 100.347 100.297 100.501 100.563 101.241 101.875
                                                                                
                                                          98.103  98.105
                                                                                
                                                
       0  14.718  49.333   92.34 134.298 194.088  249.67 261.202 317.333 367.274
 389.207 419.439 455.915 498.011 519.452  530.28  530.29  660.71  660.72 667.346
 672.388 716.544 751.525 792.205 805.513 816.603 885.054 935.466 993.9951037.809
 1085.521136.0051180.6821232.1271239.3241281.973 1327.52
 103.241 102.906 101.938 101.344 101.031 100.469 100.156 100.129 100.125 100.156
 100.094  99.938   99.85  99.906 100.188  100.56  100.56  100.28  100.28 100.139
 100.219 100.313 100.313 100.375 100.531 100.502   100.5 100.413 100.563 100.472
 100.438 100.347 100.297 100.501 100.563 101.241 101.875
                                                                                
                                                  98.103  98.105
                                                                                
                                                        
Pier Skew, UpSta & Num, DnSta & Num=  ,569.7483, 2 ,544.7483, 2 , 0 , 0 , 0 ,,
     1.5     1.5
   83.25   98.17
     1.5     1.5
   83.25   98.17
Pier Skew, UpSta & Num, DnSta & Num=  ,595.1233, 2 ,570.1233, 2 , 0 , 0 , 0 ,,
     1.5     1.5
   83.25   98.17
     1.5     1.5
   83.25   98.17
Pier Skew, UpSta & Num, DnSta & Num=  ,620.4983, 2 ,595.4983, 2 , 0 , 0 , 0 ,,
     1.5     1.5
   83.25   98.17
     1.5     1.5
   83.25   98.17
Pier Skew, UpSta & Num, DnSta & Num=  ,645.8733, 2 ,620.8733, 2 , 0 , 0 , 0 ,,
     1.5     1.5
   83.25   98.17
     1.5     1.5
   83.25   98.17
Pier Skew, UpSta & Num, DnSta & Num=  ,671.2483, 2 ,646.2483, 2 , 0 , 0 , 0 ,,
     1.5     1.5
   83.25   98.17
     1.5     1.5
   83.25   98.17
Abutment Skew #Up #Dn= , 2 , 2
  555.28     575
      97      60
  530.28     550
      97      60
Abutment Skew #Up #Dn= , 2 , 2
     666   685.7
      60      97
     641   660.7
      60      97
BR Coef=-1 , 1 , 1 ,1.25, 0 ,,,0.8,0,2,0,
WSPro=,,,, 1 ,,,, 0 ,,,, 0 ,,,,-1 ,-1 ,-1 , 0 , 0 , 0 , 0 , 0
BR D #Sta/Elev= 30
       0  113.65   58.76  109.05  188.61   102.1  242.62   96.76  255.46   96.66
  267.89   94.11  281.43   94.13  290.64   91.87  303.08    90.4  363.67   89.89
  397.48   90.68  417.77   89.43     572  90.025  583.16   83.78  592.43   83.89
  601.71   85.77  622.32      85     635  91.268     680    91.7  769.45   95.82
  856.01    97.2  935.92    96.7  965.09   97.24  970.25   96.63  977.98    94.3
 1001.17   94.13 1071.42   96.05 1186.31   97.35 1226.96  100.91 1334.58  102.54
BR D #Mann= 3
       0     .14     572    .055     635     .14
BC Design=,, 0 ,, 0 ,,,,,,
BC Use User HTab Curves=0
BC User HTab FreeFlow(D)= 0

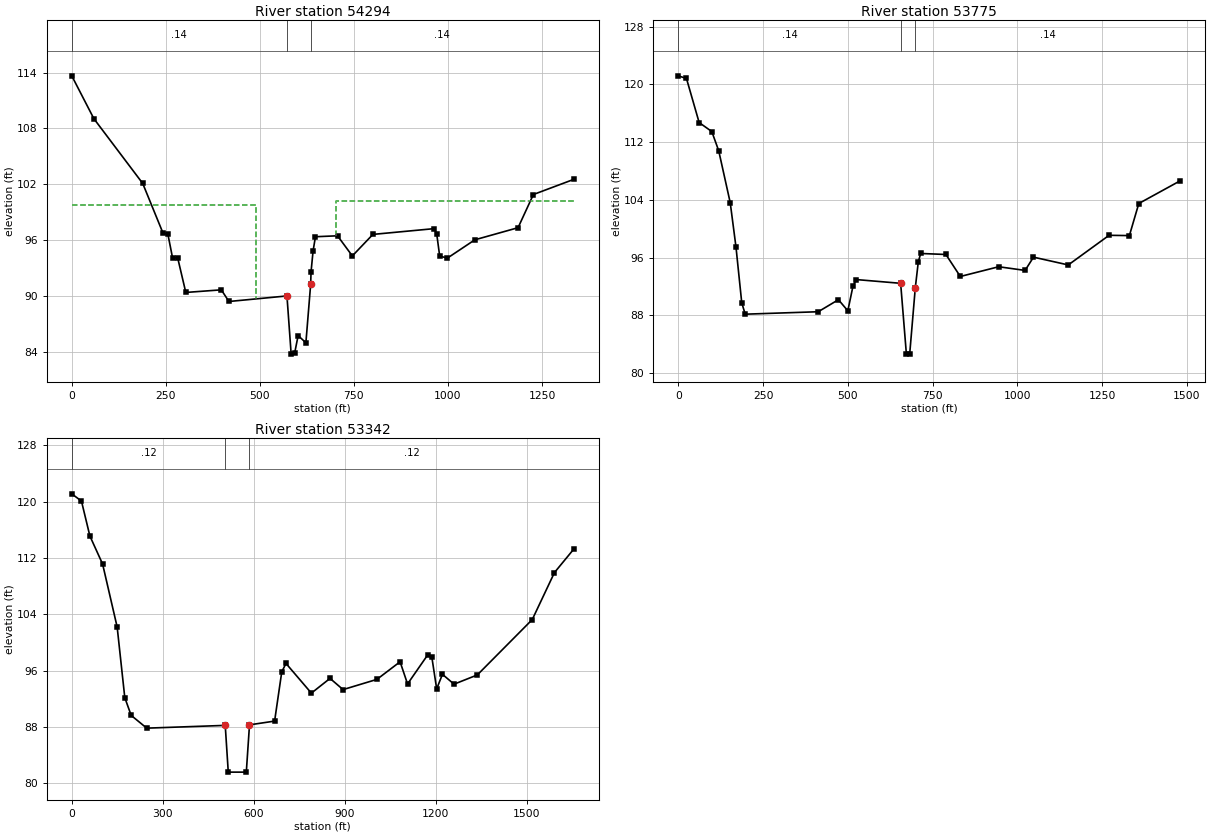
Type RM Length L Ch R = 1 ,54294   ,511.9,511.9,511.9
XS GIS Cut Line= 5
 2360380.3665763855725.2879017232360239.52416023855512.493381787
 2360112.4598066855002.7050714382359980.80276548  854624.5738022
2359879.76364091854456.175261244
#Sta/Elev= 30
       0  113.65   58.76  109.05  188.61   102.1  242.62   96.76  255.46   96.66
  267.89   94.11  281.43   94.13  303.08    90.4  397.48   90.68  417.77   89.43
     572  90.025  583.16   83.78  592.43   83.89  601.71   85.77  622.32      85
     635  91.268  636.03   92.61  641.44   94.86  647.72   96.38   706.4   96.48
  745.78   94.32  800.42   96.63  963.71   97.25  970.25   96.63  977.98    94.3
  998.59   94.09 1071.42   96.05 1186.31   97.35 1226.96  100.91 1334.58  102.54
#Mann= 3 ,-1,0
       0     .14       0     572    .055       0     635     .14       0
#XS Ineff= 2 , 0
       0  488.89   99.79  702.11       0  100.22
Permanent Ineff=
       F       F
Bank Sta=572,635
XS Rating Curve= 0 ,0
Exp/Cntr(USF)=0,0
Exp/Cntr=0.5,0.3

Type RM Length L Ch R = 1 ,53775   ,433.3,433.3,433.3
XS GIS Cut Line= 4
2360716.10312691855643.9925133852360627.90336733855312.193417812
2360657.30328719855064.3940932712360325.50419162854241.196337167
#Sta/Elev= 30
       0   121.2    24.3  120.83   61.65  114.72      99  113.47  119.37   110.8
  153.32   103.6  170.29   97.45  187.27   89.72  197.45   88.14  412.83   88.48
   472.3   90.15  500.04   88.61  515.26   92.03  525.17   92.94  655.78  92.422
  672.73    82.6  682.43    82.6     699  91.805  707.89  95.413  714.96   96.56
  789.25   96.42   831.7   93.37  944.91   94.72 1022.74   94.21  1047.5   96.05
 1150.09   94.97 1270.37   99.08 1330.25   99.04 1357.99  103.49 1480.41  106.65
#Mann= 3 ,0,0
       0     .14       0  655.78    .055       0     699     .14       0
#XS Ineff= 2 , 0
       0                  714.96       0   96.56
Permanent Ineff=
       F       F
Bank Sta=655.78,699
XS Rating Curve= 0 ,0
Exp/Cntr(USF)=0,0
Exp/Cntr=0.3,0.1

Type RM Length L Ch R = 1 ,53342   ,1676.9,1676.9,1676.9
XS GIS Cut Line= 2
2361202.43733539855593.2498283172360644.77218888854034.587410466
#Sta/Elev= 30
       0  121.09   31.94  120.06   59.75   115.1  101.63  111.13  149.67  102.19
  174.81   92.17  195.87   89.65   247.2   87.84     506  88.232  515.99    81.6
  575.47    81.6     586   88.31  668.76   88.84  692.42   95.84  706.36   97.02
  789.99   92.81  851.52    94.9  894.54   93.31 1006.06   94.76 1082.51   97.26
 1107.12   94.11 1173.33   98.22 1187.27    97.9 1203.14   93.41 1222.12   95.48
 1260.45   94.08 1337.12   95.39 1518.33  103.25 1591.51  109.92 1655.42  113.26
#Mann= 3 ,-1,0
       0     .12       0     506    .055       0     586     .12       0
#XS Ineff= 2 , 0
       0                  706.36       0   97.02
Permanent Ineff=
       F       F
Bank Sta=506,586
XS Rating Curve= 0 ,0
Exp/Cntr(USF)=0,0
Exp/Cntr=0.3,0.1

--- JefferiesCreek.g02 (geometry) ---

Geom Title=Existing
Program Version=6.60

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
River Reach=Jeffries Creek  ,Reach 1

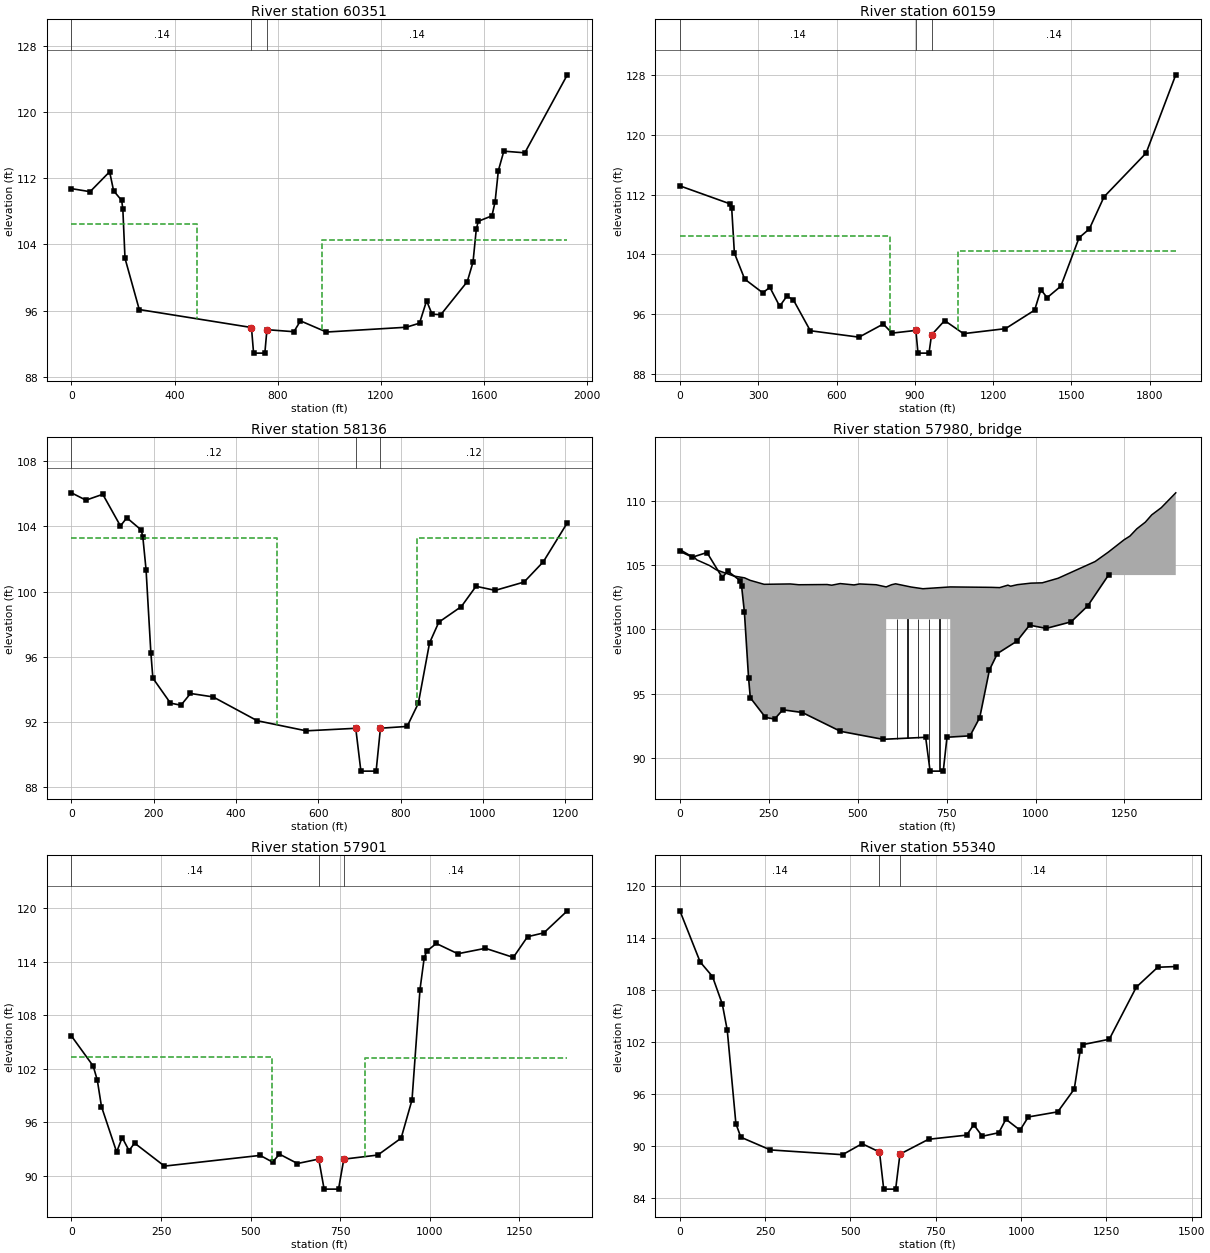
Type RM Length L Ch R = 1 ,60351   ,191.7,191.7,191.7
XS GIS Cut Line= 4
 2355455.0336001857937.1289831522355389.50318341857857.036251653
2354320.99333364856976.0162051632354484.81937534856573.732258315
#Sta/Elev= 30
       0  110.74    72.2  110.37     148  112.78   163.4  110.48   194.8  109.31
   199.3  108.22   207.6  102.32   262.9   96.12     698  93.948  706.18   90.85
  749.86   90.85     758  93.686   862.5   93.44     888   94.75   988.7    93.4
  1298.1   93.98  1349.7   94.47  1377.1   97.18  1398.3   95.56  1432.3    95.5
  1534.8   99.49  1557.1  101.86  1569.7   105.8  1577.4  106.79  1630.5  107.45
  1642.7  109.14  1655.3  112.91  1676.6  115.27    1758  115.071922.734   124.5
#Mann= 3 ,0,0
       0     .14       0     698     .06       0     758     .14       0
#XS Ineff= 2 , 0
       0     486   106.5     970       0   104.5
Permanent Ineff=
       F       F
Bank Sta=698,758
XS Rating Curve= 0 ,0
Exp/Cntr(USF)=0,0
Exp/Cntr=0.5,0.3

Type RM Length L Ch R = 1 ,60159   ,790.7,790.7,790.7
XS GIS Cut Line= 5
 2355657.0857182857933.4884044472355515.10314872857671.366737723
2354859.79898191857196.271216785 2354570.3729749856996.039388038
2354606.77876195856557.349654145
#Sta/Elev= 30
       0  113.16   193.8  110.73   198.4  110.18   208.7  104.16   248.2  100.67
   317.4   98.83   344.6   99.57   382.2   97.03   410.1    98.4   434.9   97.87
   499.6   93.75   686.2   92.89   779.1   94.65   812.6   93.43     904  93.796
  912.07   90.75  954.26   90.75     964  93.189  1014.2   95.11  1086.5   93.36
  1247.3   94.03    1359   96.51    1383   99.25  1406.9   98.18  1459.4   99.72
  1529.3  106.21  1568.8   107.4  1624.8  111.69  1786.1  117.561899.648  128.04
#Mann= 3 ,0,0
       0     .14       0     904     .06       0     964     .14       0
#XS Ineff= 2 , 0
       0  803.15   106.5 1064.85       0   104.5
Permanent Ineff=
       F       F
Bank Sta=904,964
XS Rating Curve= 0 ,0
Exp/Cntr(USF)=0,0
Exp/Cntr=0.5,0.3

Type RM Length L Ch R = 1 ,58136   ,234.6,234.6,234.6
XS GIS Cut Line= 3
2357302.15484009 856912.774707612357260.86198695856852.509462489
2356306.66227254856243.160872935
#Sta/Elev= 30
       0  106.06   35.18  105.61   76.11  105.97  119.03  104.03   134.6  104.53
  169.64  103.78  173.53  103.34  181.32  101.35     193   96.26  197.89    94.7
  240.57   93.17  266.18   93.04  289.34   93.76  344.21   93.55   451.5   92.09
  570.63   91.47     691  91.626  703.49      89  740.51      89     751   91.63
   815.9   91.74  843.15   93.16   870.4   96.86  892.88   98.13  947.75   99.09
   983.3  100.33 1030.02  100.08  1100.1  100.59 1146.82  101.83 1205.22  104.22
#Mann= 3 ,-1,0
       0     .12       0     691     .06       0     751     .12       0
#XS Ineff= 2 , 0
       0     500   103.3     840       0  103.27
Permanent Ineff=
       F       F
Bank Sta=691,751
XS Rating Curve= 0 ,0
Exp/Cntr(USF)=0,0
Exp/Cntr=0.5,0.3

Type RM Length L Ch R = 3 ,57980   ,,,
Bridge Culvert--1,0,-1,-1, 0
Deck Dist Width WeirC Skew NumUp NumDn MinLoCord MaxHiCord MaxSubmerge Is_Ogee
80,76.33,2.6,0, 44, 44, , , 0.98, 0, 2,2,,
       0  26.165  39.189  47.111  83.058  102.56 151.407 181.774 197.375 236.755
 310.389 334.142 413.879 426.778 450.621 489.582 505.186 551.919  579.99     580
     580 595.423 606.465 650.054  683.29     760     760 876.427 899.023  922.27
 929.902 948.981 987.141 1018.96 1063.461167.4081204.6491248.8161265.3611284.642
1308.6741326.7591353.4711394.276
 106.203 105.777 105.656 105.406 104.964 104.625 104.146 104.005 103.813 103.503
 103.531  103.47 103.487 103.434 103.561 103.455 103.531 103.469   103.3   103.3
   103.3 103.474 103.542 103.293  103.16   103.3   103.3 103.267 103.247 103.438
 103.356 103.476 103.594  103.62 103.974  105.27 106.003 106.958 107.247 107.809
 108.328 108.896 109.451 110.605
                                                                                
                                                                                
   100.8   100.8   100.8   100.8   100.8   100.8
                                                                                
                                
       0  26.165  39.189  47.111  83.058  102.56 151.407 181.774 197.375 236.755
 310.389 334.142 413.879 426.778 450.621 489.582 505.186 551.919 595.423  599.99
     600     600 606.465 650.054  683.29     780     780 876.427 899.023  922.27
 929.902 948.981 987.141 1018.96 1063.461167.4081204.6491248.8161265.3611284.642
1308.6741326.7591353.4711394.276
 106.203 105.777 105.656 105.406 104.964 104.625 104.146 104.005 103.813 103.503
 103.531  103.47 103.487 103.434 103.561 103.455 103.531 103.469 103.474   103.3
   103.3   103.3 103.542 103.293  103.16   103.3   103.3 103.267 103.247 103.438
 103.356 103.476 103.594  103.62 103.974  105.27 106.003 106.958 107.247 107.809
 108.328 108.896 109.451 110.605
                                                                                
                                                                                
           100.8   100.8   100.8   100.8   100.8
                                                                                
                                
Pier Skew, UpSta & Num, DnSta & Num=  ,610, 2 ,630, 2 , 0 , 0 , 0 ,,
     1.3     1.3
    88.5   100.8
     1.3     1.3
    88.5   100.8
Pier Skew, UpSta & Num, DnSta & Num=  ,640, 2 ,660, 2 , 0 , 0 , 0 ,,
     1.3     1.3
    88.5   100.8
     1.3     1.3
    88.5   100.8
Pier Skew, UpSta & Num, DnSta & Num=  ,670, 2 ,690, 2 , 0 , 0 , 0 ,,
     1.3     1.3
    88.5   100.8
     1.3     1.3
    88.5   100.8
Pier Skew, UpSta & Num, DnSta & Num=  ,700, 2 ,720, 2 , 0 , 0 , 0 ,,
     1.3     1.3
    88.5   100.8
     1.3     1.3
    88.5   100.8
Pier Skew, UpSta & Num, DnSta & Num=  ,730, 2 ,750, 2 , 0 , 0 , 0 ,,
     1.3     1.3
    88.5   100.8
     1.3     1.3
    88.5   100.8
Abutment Skew #Up #Dn= , 2 , 2
  580.01     600
    99.8    79.8
  600.01     620
    99.8    79.8
Abutment Skew #Up #Dn= , 2 , 2
     740  760.01
    79.8    99.8
     760  780.01
    79.8    99.8
BR Coef=-1 , 1 , 1 ,1.25, 0 ,,,0.8,0,2,0,
WSPro=,,,, 1 ,,,, 0 ,,,, 0 ,,,,-1 ,-1 ,-1 , 0 , 0 , 0 , 0 , 0
BC Design=,, 0 ,, 0 ,,,,,,
BC Use User HTab Curves=0
BC User HTab FreeFlow(D)= 0

Type RM Length L Ch R = 1 ,57901   ,681.8,681.8,681.8
XS GIS Cut Line= 4
 2357503.4505629856755.8917374742356949.68207244856415.692664835
2356853.29233519856321.1929224352356335.43374684856020.683741604
#Sta/Elev= 30
       0  105.66    60.6   102.3    72.2   100.7    83.7   97.76   126.1   92.66
   141.5   94.28   160.7   92.82   176.1   93.66   259.5   91.08   526.6   92.28
   561.2   91.53   580.5   92.42   630.6   91.37     690  91.867  705.04    88.5
  745.24    88.5     760  91.859   854.9   92.32   919.9   94.21   950.3    98.5
   972.5  110.85   984.4  114.45   991.7  115.18  1018.1  116.03  1078.1  114.88
  1155.1  115.49    1233  114.47  1272.7  116.79  1318.2  117.22 1383.64  119.69
#Mann= 3 ,0,0
       0     .14       0     690    .055       0     760     .14       0
#XS Ineff= 2 , 0
       0 560.865   103.3 819.135       0  103.25
Permanent Ineff=
       F       F
Bank Sta=690,760
XS Rating Curve= 0 ,0
Exp/Cntr(USF)=0,0
Exp/Cntr=0.5,0.3

Type RM Length L Ch R = 1 ,55340   ,753,753,753
XS GIS Cut Line= 4
2359425.08758033856068.2085669432359287.30695591855768.152984876
2359004.09122794854909.320425999  2359030.116457854691.933218583
#Sta/Elev= 30
       0  117.16   59.38  111.25   95.49  109.57  124.37  106.37  138.81  103.36
  164.09   92.57  178.53      91  265.18   89.53  476.73   88.98  534.02   90.25
     585   89.29  597.41      85  632.39      85     645  89.042  728.75   90.76
  840.47   91.24  861.26   92.44  886.42   91.11  934.79   91.52  955.52   93.08
  996.98   91.81 1021.17   93.34 1107.54   93.93 1155.91   96.56 1173.19  100.98
  1180.1  101.69 1258.59  102.32 1337.78  108.34 1400.57  110.64 1453.44  110.72
#Mann= 3 ,-1,0
       0     .14       0     585    .055       0     645     .14       0
Bank Sta=585,645
XS Rating Curve= 0 ,0
Exp/Cntr(USF)=0,0
Exp/Cntr=0.5,0.3

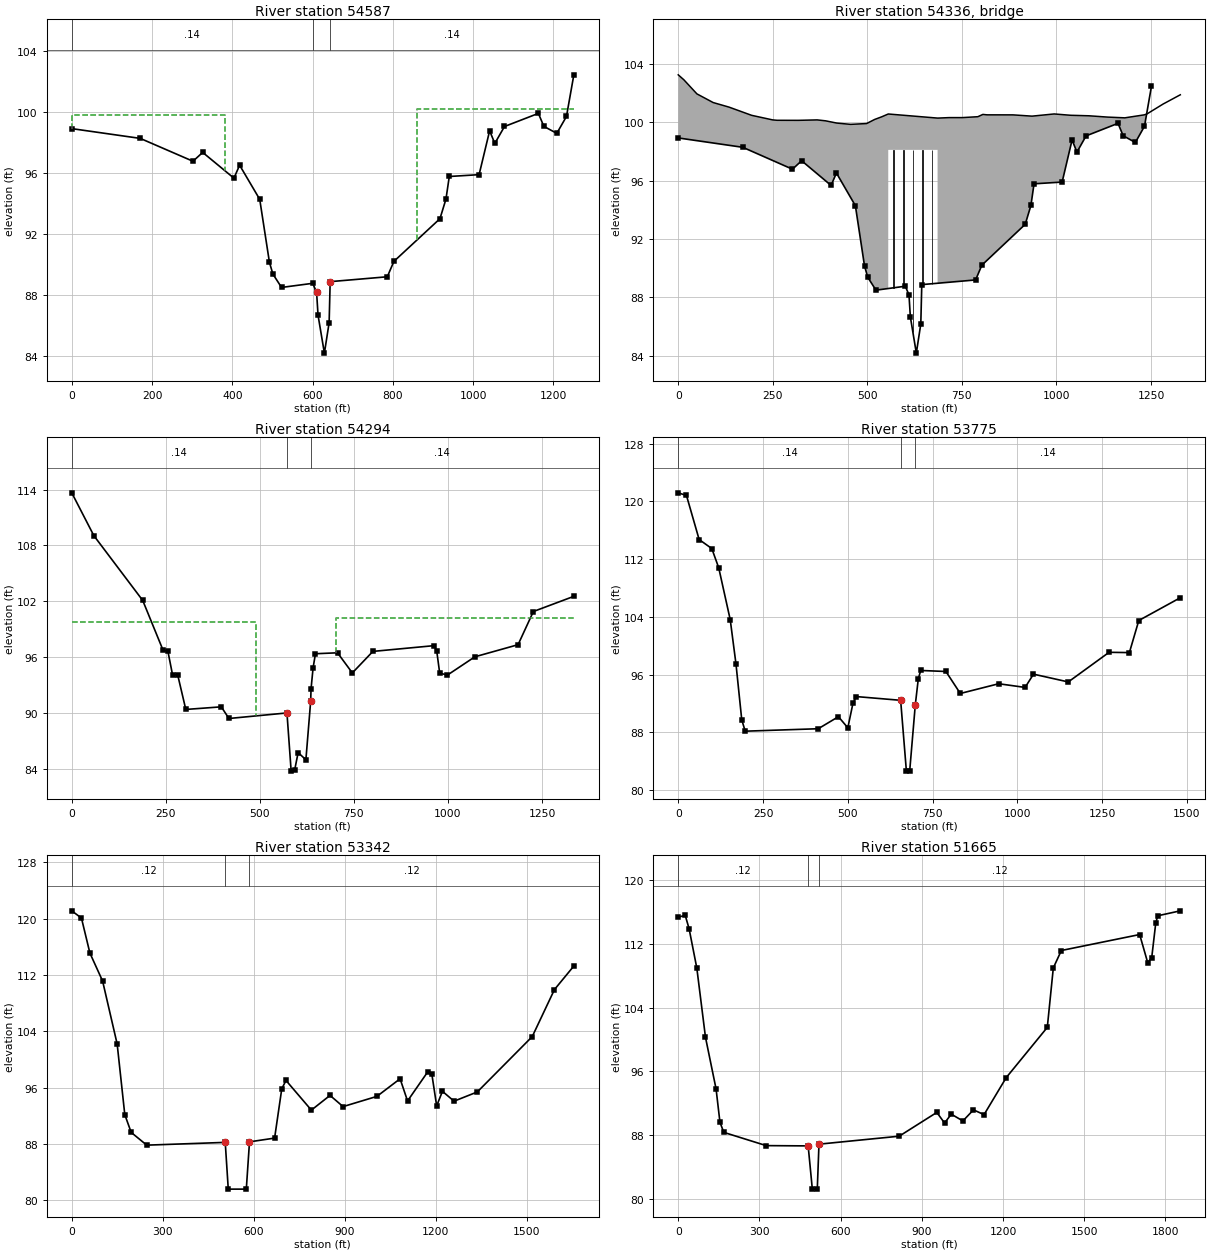
Type RM Length L Ch R = 1 ,54587   ,293.3,293.3,293.3
XS GIS Cut Line= 3
2360101.74353581855758.9676099142359783.31720382854970.556259074
2359588.89343381 854619.98111472
#Sta/Elev= 30
       0   98.92  170.56   98.28  302.03   96.78  326.26   97.36  404.11   95.67
  418.27   96.52  468.39   94.28  492.58   90.15  501.16   89.38  522.75    88.5
   600.4   88.77  610.11   88.18   613.7   86.68  629.52   84.19  641.35   86.19
  643.94   88.88  786.29    89.2  802.76   90.21  917.51   93.01  932.51    94.3
  940.77   95.78 1015.06    95.9 1041.32   98.78 1054.21   97.95 1078.34   99.06
 1162.81   99.92 1176.39   99.07 1208.67   98.61  1232.8   99.72 1251.17  102.45
#Mann= 3 ,-1,0
       0     .14       0   600.4    .055       0  643.94     .14       0
#XS Ineff= 2 , 0
       0  381.29   99.79  859.71       0  100.22
Permanent Ineff=
       F       F
Bank Sta=610.11,643.94
XS Rating Curve= 0 ,0
Exp/Cntr(USF)=0,0
Exp/Cntr=0.5,0.3

Type RM Length L Ch R = 3 ,54336   ,,,
Bridge Culvert--1,0,-1,-1, 0
Deck Dist Width WeirC Skew NumUp NumDn MinLoCord MaxHiCord MaxSubmerge Is_Ogee
174,36.5,2.6,0, 36, 37, , , 0.98, 0, 2,2,,
       0  14.718  49.333   92.34 134.298 194.088  249.67 261.202 317.333 367.274
 389.207 419.439 455.915 498.011 519.452 538.091  555.28  555.29  685.71  686.72
 716.544 751.525 792.205 805.513 816.603 885.054 935.466 993.9951037.809 1085.52
1136.0051180.6821232.1271239.3241281.973 1327.52
 103.241 102.906 101.938 101.344 101.031 100.469 100.156 100.129 100.125 100.156
 100.094  99.938   99.85  99.906 100.188 100.369  100.56  100.56  100.28  100.28
 100.313 100.313 100.375 100.531 100.502   100.5 100.413 100.563 100.472 100.438
 100.347 100.297 100.501 100.563 101.241 101.875
                                                                                
                                                          98.103  98.105
                                                                                
                                                
       0  14.718  49.333   92.34 134.298 194.088  249.67 261.202 317.333 367.274
 389.207 419.439 455.915 498.011 519.452  530.28  530.29  660.71  660.72 667.346
 672.388 716.544 751.525 792.205 805.513 816.603 885.054 935.466 993.9951037.809
 1085.521136.0051180.6821232.1271239.3241281.973 1327.52
 103.241 102.906 101.938 101.344 101.031 100.469 100.156 100.129 100.125 100.156
 100.094  99.938   99.85  99.906 100.188  100.56  100.56  100.28  100.28 100.139
 100.219 100.313 100.313 100.375 100.531 100.502   100.5 100.413 100.563 100.472
 100.438 100.347 100.297 100.501 100.563 101.241 101.875
                                                                                
                                                  98.103  98.105
                                                                                
                                                        
Pier Skew, UpSta & Num, DnSta & Num=  ,569.7483, 2 ,544.7483, 2 , 0 , 0 , 0 ,,
     1.5     1.5
   83.25   98.17
     1.5     1.5
   83.25   98.17
Pier Skew, UpSta & Num, DnSta & Num=  ,595.1233, 2 ,570.1233, 2 , 0 , 0 , 0 ,,
     1.5     1.5
   83.25   98.17
     1.5     1.5
   83.25   98.17
Pier Skew, UpSta & Num, DnSta & Num=  ,620.4983, 2 ,595.4983, 2 , 0 , 0 , 0 ,,
     1.5     1.5
   83.25   98.17
     1.5     1.5
   83.25   98.17
Pier Skew, UpSta & Num, DnSta & Num=  ,645.8733, 2 ,620.8733, 2 , 0 , 0 , 0 ,,
     1.5     1.5
   83.25   98.17
     1.5     1.5
   83.25   98.17
Pier Skew, UpSta & Num, DnSta & Num=  ,671.2483, 2 ,646.2483, 2 , 0 , 0 , 0 ,,
     1.5     1.5
   83.25   98.17
     1.5     1.5
   83.25   98.17
Abutment Skew #Up #Dn= , 2 , 2
  555.28     575
      97      60
  530.28     550
      97      60
Abutment Skew #Up #Dn= , 2 , 2
     666   685.7
      60      97
     641   660.7
      60      97
BR Coef=-1 , 1 , 1 ,1.25, 0 ,,,0.8,0,2,0,
WSPro=,,,, 1 ,,,, 0 ,,,, 0 ,,,,-1 ,-1 ,-1 , 0 , 0 , 0 , 0 , 0
BR D #Sta/Elev= 30
       0  113.65   58.76  109.05  188.61   102.1  242.62   96.76  255.46   96.66
  267.89   94.11  281.43   94.13  290.64   91.87  303.08    90.4  363.67   89.89
  397.48   90.68  417.77   89.43     572  90.025  583.16   83.78  592.43   83.89
  601.71   85.77  622.32      85     635  91.268     680    91.7  769.45   95.82
  856.01    97.2  935.92    96.7  965.09   97.24  970.25   96.63  977.98    94.3
 1001.17   94.13 1071.42   96.05 1186.31   97.35 1226.96  100.91 1334.58  102.54
BR D #Mann= 3
       0     .14     572    .055     635     .14
BC Design=,, 0 ,, 0 ,,,,,,
BC Use User HTab Curves=0
BC User HTab FreeFlow(D)= 0

Type RM Length L Ch R = 1 ,54294   ,518.8,518.8,518.8
XS GIS Cut Line= 5
 2360380.3665763855725.2879017232360239.52416023855512.493381787
 2360112.4598066855002.7050714382359980.80276548  854624.5738022
2359879.76364091854456.175261244
#Sta/Elev= 30
       0  113.65   58.76  109.05  188.61   102.1  242.62   96.76  255.46   96.66
  267.89   94.11  281.43   94.13  303.08    90.4  397.48   90.68  417.77   89.43
     572  90.025  583.16   83.78  592.43   83.89  601.71   85.77  622.32      85
     635  91.268  636.03   92.61  641.44   94.86  647.72   96.38   706.4   96.48
  745.78   94.32  800.42   96.63  963.71   97.25  970.25   96.63  977.98    94.3
  998.59   94.09 1071.42   96.05 1186.31   97.35 1226.96  100.91 1334.58  102.54
#Mann= 3 ,-1,0
       0     .14       0     572    .055       0     635     .14       0
#XS Ineff= 2 , 0
       0  488.89   99.79  702.11       0  100.22
Permanent Ineff=
       F       F
Bank Sta=572,635
XS Rating Curve= 0 ,0
Exp/Cntr(USF)=0,0
Exp/Cntr=0.5,0.3

Type RM Length L Ch R = 1 ,53775   ,433.3,433.3,433.3
XS GIS Cut Line= 4
2360716.10312691855643.9925133852360627.90336733855312.193417812
2360657.30328719855064.3940932712360325.50419162854241.196337167
#Sta/Elev= 30
       0   121.2    24.3  120.83   61.65  114.72      99  113.47  119.37   110.8
  153.32   103.6  170.29   97.45  187.27   89.72  197.45   88.14  412.83   88.48
   472.3   90.15  500.04   88.61  515.26   92.03  525.17   92.94  655.78  92.422
  672.73    82.6  682.43    82.6     699  91.805  707.89  95.413  714.96   96.56
  789.25   96.42   831.7   93.37  944.91   94.72 1022.74   94.21  1047.5   96.05
 1150.09   94.97 1270.37   99.08 1330.25   99.04 1357.99  103.49 1480.41  106.65
#Mann= 3 ,0,0
       0     .14       0  655.78    .055       0     699     .14       0
#XS Ineff= 2 , 0
       0                  714.96       0   96.56
Permanent Ineff=
       F       F
Bank Sta=655.78,699
XS Rating Curve= 0 ,0
Exp/Cntr(USF)=0,0
Exp/Cntr=0.3,0.1

Type RM Length L Ch R = 1 ,53342   ,1676.9,1676.9,1676.9
XS GIS Cut Line= 2
2361202.43733539855593.2498283172360644.77218888854034.587410466
#Sta/Elev= 30
       0  121.09   31.94  120.06   59.75   115.1  101.63  111.13  149.67  102.19
  174.81   92.17  195.87   89.65   247.2   87.84     506  88.232  515.99    81.6
  575.47    81.6     586   88.31  668.76   88.84  692.42   95.84  706.36   97.02
  789.99   92.81  851.52    94.9  894.54   93.31 1006.06   94.76 1082.51   97.26
 1107.12   94.11 1173.33   98.22 1187.27    97.9 1203.14   93.41 1222.12   95.48
 1260.45   94.08 1337.12   95.39 1518.33  103.25 1591.51  109.92 1655.42  113.26
#Mann= 3 ,-1,0
       0     .12       0     506    .055       0     586     .12       0
#XS Ineff= 2 , 0
       0                  706.36       0   97.02
Permanent Ineff=
       F       F
Bank Sta=506,586
XS Rating Curve= 0 ,0
Exp/Cntr(USF)=0,0
Exp/Cntr=0.3,0.1

Type RM Length L Ch R = 1 ,51665   ,995.5,995.5,995.5
XS GIS Cut Line= 3
2362775.87278337855045.6412799452362301.29507704853921.283344873
2362005.32188384853359.954875019
#Sta/Elev= 30
       0  115.33   25.88  115.53   40.12  113.87   68.61  108.95  100.66  100.27
  139.84   93.79  154.09   89.63  168.33   88.36  325.03    86.7     480  86.665
   495.4   81.25  513.72   81.25     520  86.881  816.33   87.88   955.4   90.86
  983.89   89.53 1008.82   90.64 1051.74   89.79 1090.73   91.18  1129.9   90.58
 1211.82   95.22 1363.54  101.51 1385.79  108.96 1415.47  111.14 1704.79  113.14
 1734.43  109.63  1749.3  110.23 1764.14  114.55 1771.55  115.49 1854.99  116.11
#Mann= 3 ,-1,0
       0     .12       0     480    .055       0     520     .12       0
Bank Sta=480,520
XS Rating Curve= 0 ,0
Exp/Cntr(USF)=0,0
Exp/Cntr=0.3,0.1

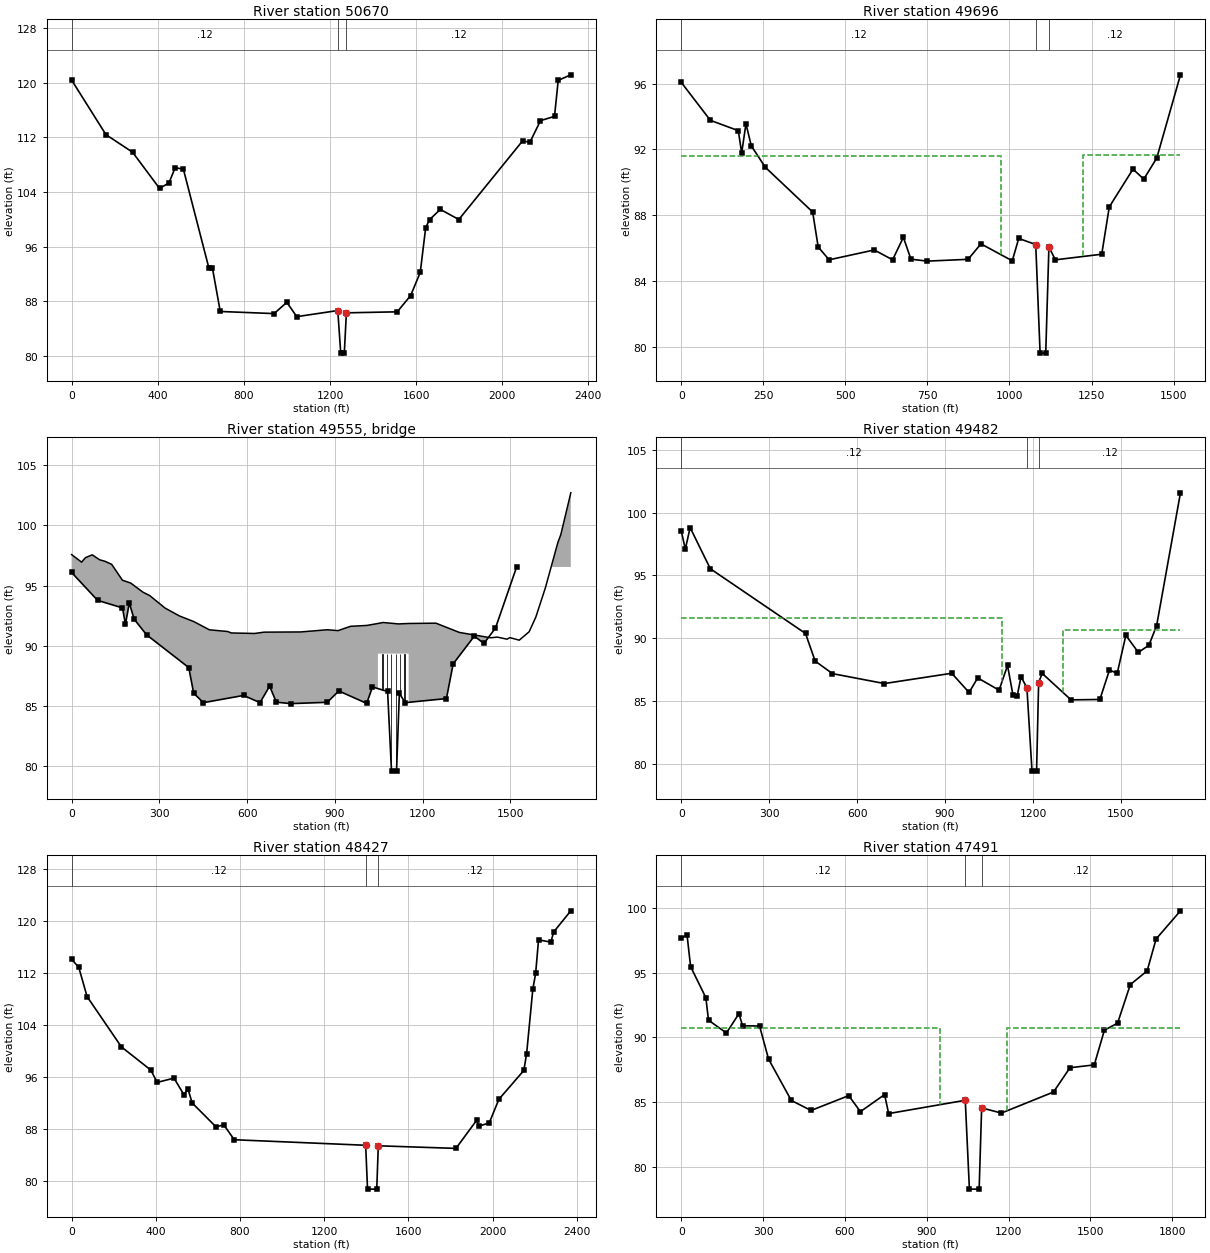
Type RM Length L Ch R = 1 ,50670   ,973.6,973.6,973.6
XS GIS Cut Line= 4
2363546.90013075855252.8232327722363434.13805447854749.421106492
 2363369.7025823853867.4605812512363003.22583437853025.772226112
#Sta/Elev= 30
       0  120.39   159.4   112.4   283.2  109.82   408.2  104.53   451.9  105.32
     481  107.57   519.1  107.33   637.5   92.85     654   92.85   690.2    86.5
   940.2   86.19   999.4   87.84  1045.5   85.74    1236  86.635 1249.76    80.4
 1266.24    80.4    1276  86.301  1512.1   86.45  1574.4   88.83  1619.1   92.24
  1644.2   98.78  1662.1   99.95  1712.2  101.45  1798.1   99.97  2095.1  111.52
  2127.8  111.25  2177.4  114.45  2242.5  115.08  2259.7  120.352318.199  121.16
#Mann= 3 ,0,0
       0     .12       0    1236    .055       0    1276     .12       0
Bank Sta=1236,1276
XS Rating Curve= 0 ,0
Exp/Cntr(USF)=0,0
Exp/Cntr=0.5,0.3

Type RM Length L Ch R = 1 ,49696   ,213.8,213.8,213.8
XS GIS Cut Line= 3
2364130.43179389854647.782203588 2364197.9561415854483.375096362
2364133.36763509853141.695667752
#Sta/Elev= 30
       0   96.08    88.7   93.77   173.8   93.14     184   91.78   197.1   93.56
   213.5   92.21   256.2   90.91   400.3   88.19   417.2   86.06   450.5   85.28
     588   85.88   643.9   85.28   676.7   86.65   699.7   85.32     749    85.2
   873.8   85.31   913.2   86.25  1008.5   85.22  1028.2   86.58    1080   86.21
 1093.33    79.6  1110.5    79.6 1120.17   86.06  1139.9   85.28  1281.1   85.62
  1304.1    88.5  1376.4    90.8  1409.2   90.19  1448.7   91.47 1520.97   96.54
#Mann= 3 ,0,0
       0     .12       0    1080    .055       0 1120.17     .12       0
#XS Ineff= 2 , 0
       0     975   91.61    1224       0   91.69
Permanent Ineff=
       F       F
Bank Sta=1080,1120.17
XS Rating Curve= 0 ,0
Exp/Cntr=0.5,0.3

Type RM Length L Ch R = 3 ,49555   ,,,
Bridge Culvert--1,0,-1,-1, 0
Deck Dist Width WeirC Skew NumUp NumDn MinLoCord MaxHiCord MaxSubmerge Is_Ogee
72,36.5,2.6,0, 44, 45, , , 0.98, 0, 2,2,,
       0  33.961  47.247  70.498  95.603 114.095 136.761 173.702 201.718  244.11
 266.729 319.672 368.967 418.188 470.758 533.424 545.838 624.992  657.81 782.525
 874.409 910.507 953.1681009.139 1046.99    1047    10471064.7421117.248    1152
    1152 1245.23 1325.111432.2821455.2531488.0691497.9141529.9741563.7011586.517
1619.3331661.9941671.8381706.177
  97.566  96.937  97.313  97.545  97.136  97.008  96.758  95.438  95.205   94.44
  94.167  93.123  92.469      92  91.326  91.183  91.064  91.021   91.13  91.147
   91.33  91.256  91.614  91.688   91.85   91.85   91.85   91.93  91.813   91.85
   91.85  91.875  91.108  90.664  90.719  90.546  90.675  90.465  91.161  92.375
  94.813  98.577  99.209 102.689
                                                                                
                                                                                
                                                   89.35   89.35   89.35   89.35
                                                                                
                                
       0  33.961  47.247  70.498  95.603 114.095 136.761 173.702 201.718  244.11
 266.729 319.672 368.967 418.188 470.758 533.424 545.838 624.992  657.81 782.525
 874.409 910.507 953.1681009.1391064.7421117.248 1145.99    1146    1146 1245.23
    1251    1251 1251.01 1325.111432.2821455.2531488.0691497.9141529.9741563.701
1586.5171619.3331661.9941671.8381706.177
  97.566  96.937  97.313  97.545  97.136  97.008  96.758  95.438  95.205   94.44
  94.167  93.123  92.469      92  91.326  91.183  91.064  91.021   91.13  91.147
   91.33  91.256  91.614  91.688   91.93  91.813   91.85   91.85   91.85  91.875
   91.85   91.85   91.85  91.108  90.664  90.719  90.546  90.675  90.465  91.161
  92.375  94.813  98.577  99.209 102.689
                                                                                
                                                                                
                                                                   89.35   89.35
   89.35
                                        
Pier Skew, UpSta & Num, DnSta & Num=  ,1062.58, 2 ,1161.5, 2 , 0 , 0 , 0 ,,
       1       1
    79.4   89.35
       1       1
    79.4   89.35
Pier Skew, UpSta & Num, DnSta & Num=  ,1077.58, 2 ,1176.5, 2 , 0 , 0 , 0 ,,
       1       1
    79.4   89.35
       1       1
    79.4   89.35
Pier Skew, UpSta & Num, DnSta & Num=  ,1092.58, 2 ,1191.5, 2 , 0 , 0 , 0 ,,
       1       1
    79.4   89.35
       1       1
    79.4   89.35
Pier Skew, UpSta & Num, DnSta & Num=  ,1107.58, 2 ,1206.5, 2 , 0 , 0 , 0 ,,
       1       1
    79.4   89.35
       1       1
    79.4   89.35
Pier Skew, UpSta & Num, DnSta & Num=  ,1122.58, 2 ,1221.5, 2 , 0 , 0 , 0 ,,
       1       1
    79.4   89.35
       1       1
    79.4   89.35
Pier Skew, UpSta & Num, DnSta & Num=  ,1137.58, 2 ,1236.5, 2 , 0 , 0 , 0 ,,
       1       1
    79.4   89.35
       1       1
    79.4   89.35
Abutment Skew #Up #Dn= , 2 , 2
    1047    1100
   89.35    63.1
    1146    1199
   89.35    63.1
Abutment Skew #Up #Dn= , 2 , 2
    1100    1152
    63.1   89.35
    1199    1251
    63.1   89.35
BR Coef=-1 , 1 , 1 ,0.9, 0 ,,,0.8,0,1.2,0,
WSPro=,,,, 1 ,,,, 0 ,,,, 0 ,,,,-1 ,-1 ,-1 , 0 , 0 , 0 , 0 , 0
BC Design=,, 0 ,, 0 ,,,,,,
BC Use User HTab Curves=0
BC User HTab FreeFlow(D)= 0

Type RM Length L Ch R = 1 ,49482   ,1055.2,1055.2,1055.2
XS GIS Cut Line= 2
2364355.12548027854779.6515132712364348.60138871853076.863617004
#Sta/Elev= 30
       0   98.54    13.8   97.09    30.2   98.81    99.1   95.53   423.9   90.37
   456.7   88.17   515.8   87.17     693   86.38   922.6    87.2   981.7   85.67
  1011.2   86.83  1084.2   85.85  1112.9   87.82  1131.6   85.45  1145.8   85.38
  1158.9   86.92    1179   86.05 1196.43    79.4 1211.99    79.4    1219   86.45
  1231.1   87.19  1329.5   85.08  1427.9   85.11  1460.7   87.46    1487   87.19
  1516.5   90.22  1559.2   88.86  1595.3   89.44  1621.5   90.99  1702.8  101.58
#Mann= 3 ,0,0
       0     .12       0    1179    .055       0    1219     .12       0
#XS Ineff= 2 , 0
       0 1093.35   91.61 1303.65       0   90.68
Permanent Ineff=
       F       F
Bank Sta=1179,1219
XS Rating Curve= 0 ,0
Exp/Cntr=0.5,0.3

Type RM Length L Ch R = 1 ,48427   ,936.3,936.3,936.3
XS GIS Cut Line= 4
2365539.24809779854867.7267492852365337.00125953853703.176406435
2365340.26330531853191.0352192442365284.80852708852515.791743138
#Sta/Elev= 30
       0  114.12    33.9  112.89    73.4  108.39   236.6  100.66   376.4   97.09
   406.4    95.2   486.3   95.86     533   93.34   552.9   94.16   572.9   92.04
   686.2   88.36   722.8   88.69   772.7   86.39    1397   85.54 1405.82    78.8
 1449.67    78.8    1457   85.46  1825.9   85.06  1924.7    89.4  1934.5   88.48
    1984   88.97    2030   92.61  2148.5   97.04  2161.7   99.63  2191.3  109.57
  2204.5  111.94  2218.3  117.11  2276.9  116.76  2290.1  118.32 2371.65  121.57
#Mann= 3 ,0,0
       0     .12       0    1397    .055       0    1457     .12       0
Bank Sta=1397,1457
XS Rating Curve= 0 ,0
Exp/Cntr=0.5,0.3

Type RM Length L Ch R = 1 ,47491   ,139,139,139
XS GIS Cut Line= 5
2365917.02170062854301.3575060172365906.91143366853982.884096634
2366057.72646812853659.5344584132366517.12649128852792.253727456
2366520.38853706852619.365301206
#Sta/Elev= 30
       0   97.68   21.09   97.95   34.22   95.48   90.03   93.08   99.88   91.33
  165.53   90.34  211.49   91.84  224.62    90.9  286.99   90.88  319.94   88.32
  403.21   85.12  475.62   84.34  613.82   85.49  656.64   84.25  745.27   85.57
  760.12    84.1    1041   85.13 1056.17   78.25 1091.87   78.25    1101   84.54
 1173.55   84.14 1364.46   85.77 1424.74   87.65 1513.85   87.87 1550.98   90.56
 1599.25    91.1 1646.02   94.09 1707.68   95.15 1740.49   97.62 1829.78    99.8
#Mann= 3 ,-1,0
       0     .12       0    1041    .055       0    1101     .12       0
#XS Ineff= 2 , 0
       0     948   90.76    1194       0    90.7
Permanent Ineff=
       F       F
Bank Sta=1041,1101
XS Rating Curve= 0 ,0
Exp/Cntr=0.5,0.3

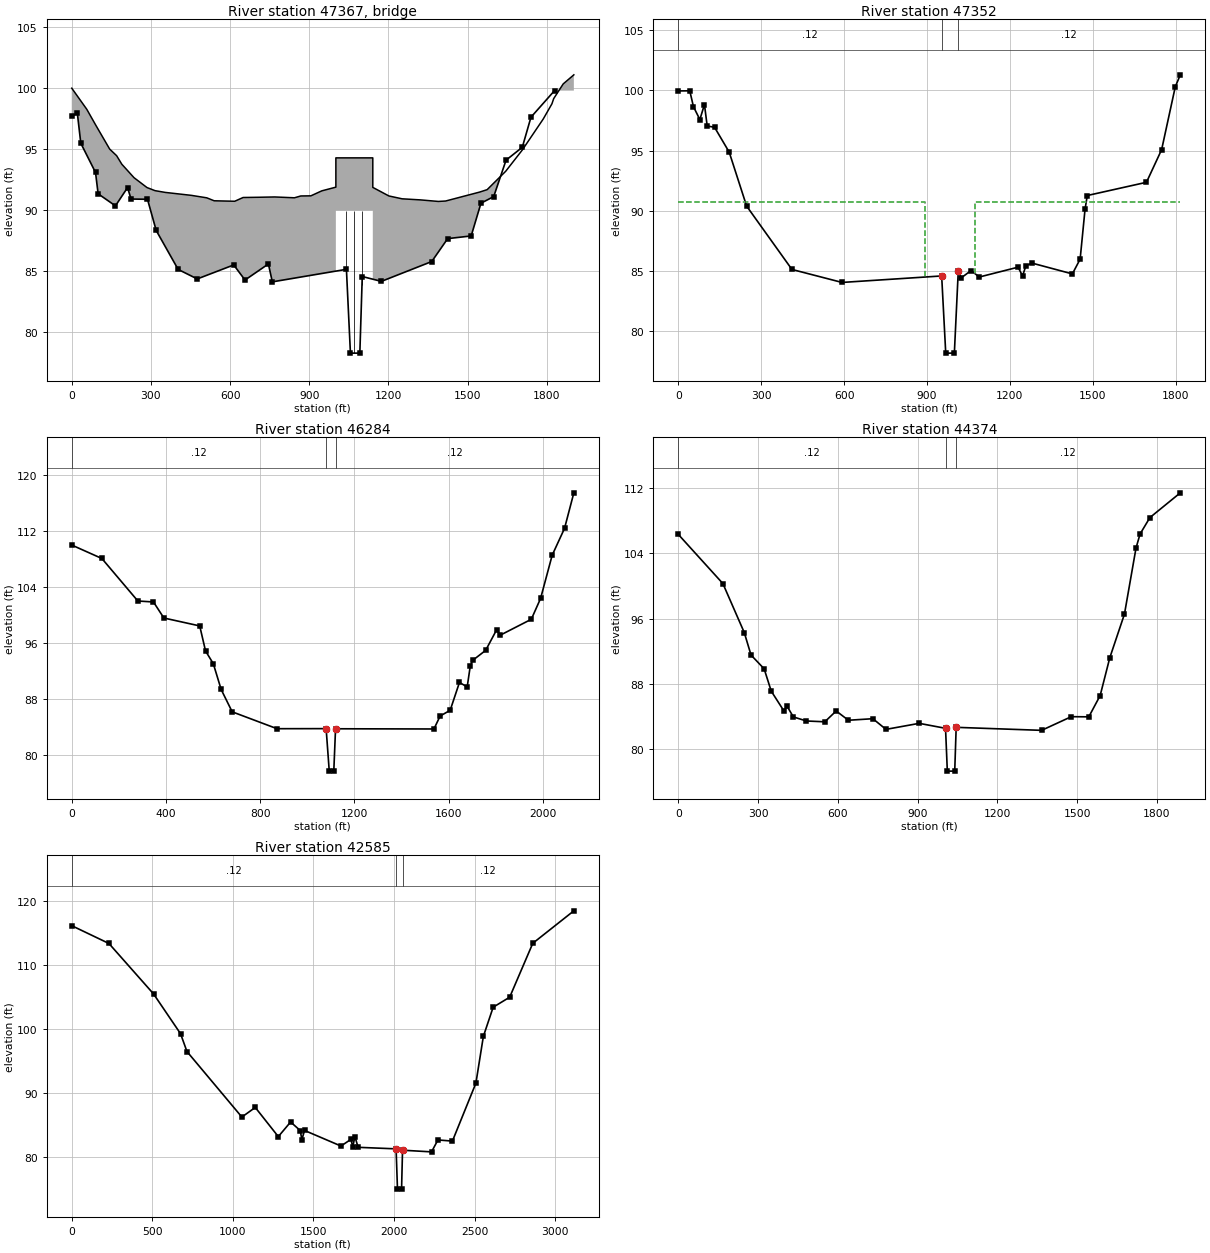
Type RM Length L Ch R = 3 ,47367   ,,,
Bridge Culvert--1,0,-1,-1, 0
Deck Dist Width WeirC Skew NumUp NumDn MinLoCord MaxHiCord MaxSubmerge Is_Ogee
53,43.25,2.6,0, 41, 40, , , 0.98, 0, 2,2,,
       0  56.852  91.096 143.716 170.026 189.759 235.801 285.077 315.404 354.479
 453.154  511.61 539.754 617.578 649.416 712.342 769.314 843.905 868.065 906.284
 947.826 1000.99    1001    1001    1141    1141 1141.01 1201.961252.0921321.322
1389.3651416.8121545.5121574.3911644.6681707.5731787.0831819.9061826.5951862.719
    1903
     100   98.27   96.96      95  94.458  93.758  92.656  91.844  91.589  91.444
  91.203      91  90.757  90.718  91.026  91.047  91.071  91.003  91.152  91.163
  91.574  91.875   94.28   94.28   94.28   94.28  91.856  91.153  90.919  90.831
  90.703  90.737  91.469  91.671  93.179  94.924  97.474  98.716  99.143 100.353
 101.097
                                                                                
                                                                                
                           89.95   89.95
                                                                                
        
 -31.148   3.096  55.716  82.026 101.759 147.801 197.077 227.404 266.479 365.154
  423.61 451.754 529.578 561.416 624.342 681.314 755.905 780.065 818.284 859.826
  912.99     913     913    1053    1053 1053.01 1113.961164.0921233.3221301.365
1328.8121457.5121486.3911556.6681619.5731699.0831731.9061738.5951774.719    1815
   98.27   96.96      95  94.458  93.758  92.656  91.844  91.589  91.444  91.203
      91  90.757  90.718  91.026  91.047  91.071  91.003  91.152  91.163  91.574
  91.875   94.28   94.28   94.28   94.28  91.856  91.153  90.919  90.831  90.703
  90.737  91.469  91.671  93.179  94.924  97.474  98.716  99.143 100.353 101.097
                                                                                
                                                                                
                   89.95   89.95
                                                                                
Pier Skew, UpSta & Num, DnSta & Num=  ,1040, 2 ,953, 2 , 0 , 0 , 0 ,,
    1.67    1.67
   78.15   89.95
    1.67    1.67
   78.15   89.95
Pier Skew, UpSta & Num, DnSta & Num=  ,1070, 2 ,983, 2 , 0 , 0 , 0 ,,
    1.67    1.67
   78.15   89.95
    1.67    1.67
   78.15   89.95
Pier Skew, UpSta & Num, DnSta & Num=  ,1100, 2 ,1013, 2 , 0 , 0 , 0 ,,
    1.67    1.67
   78.15   89.95
    1.67    1.67
   78.15   89.95
Abutment Skew #Up #Dn= , 2 , 2
 1000.99    1021
   88.95   68.95
  913.01     933
   88.95   68.95
Abutment Skew #Up #Dn= , 2 , 2
    1121 1141.01
   69.95   89.95
    1033 1053.01
   69.95   89.95
BR Coef=-1 , 1 , 1 ,1.25, 0 ,,,0.8,0,2,0,
WSPro=,,,, 1 ,,,, 0 ,,,, 0 ,,,,-1 ,-1 ,-1 , 0 , 0 , 0 , 0 , 0
BC Design=,, 0 ,, 0 ,,,,,,
BC Use User HTab Curves=0
BC User HTab FreeFlow(D)= 0

Type RM Length L Ch R = 1 ,47352   ,1067.9,1067.9,1067.9
XS GIS Cut Line= 6
 2366150.2535862854255.953762536 2366107.4490215853967.022950793
2366143.33559753853800.7895219322366201.12175988853657.394230177
 2366464.3698328853201.525616093 2366856.5289038852655.063042654
#Sta/Elev= 30
       0   99.96   41.75   99.97   55.02   98.65   78.23   97.58   94.82   98.83
  104.77   97.04   131.3   96.94  184.37   94.87   247.4   90.38  411.34   85.11
  592.55   84.03     953   84.57  967.71   78.15   998.9   78.15    1013   84.96
 1024.41   84.42  1059.3   85.02 1089.05   84.48 1229.42    85.3 1245.57   84.57
 1257.69   85.41  1279.5   85.64 1425.82   84.74 1453.95   85.97 1471.73   90.13
 1479.81   91.26 1693.85   92.36  1748.8   95.08 1798.18  100.31 1816.33   101.3
#Mann= 3 ,-1,0
       0     .12       0     953    .055       0    1013     .12       0
#XS Ineff= 2 , 0
       0 891.625   90.761074.375       0    90.7
Permanent Ineff=
       F       F
Bank Sta=953,1013
XS Rating Curve= 0 ,0
Exp/Cntr=0.5,0.3

Type RM Length L Ch R = 1 ,46284   ,1910,1910,1910
XS GIS Cut Line= 4
 2367084.1420019854441.6303144812367390.21049467853841.574979956
2367410.34657973853144.8664371852367402.29214571852383.722422251
#Sta/Elev= 30
       0  110.04   127.8  108.12   280.6  102.05   346.9  101.91   391.1   99.62
   543.3   98.49   567.9   94.92     601   93.09   634.2   89.42   681.1   86.22
   871.5   83.81    1080   83.82 1093.23   77.75 1112.54   77.75    1120    83.8
  1537.8   83.77    1564   85.62  1606.7   86.44  1646.1   90.42  1678.9   89.77
    1692   92.76  1702.2   93.57  1757.4      95  1803.6   97.92    1820   97.18
  1951.2   99.44  1990.6  102.42  2039.8  108.59  2092.3  112.43 2131.79   117.5
#Mann= 3 ,0,0
       0     .12       0    1080    .055       0    1120     .12       0
Bank Sta=1080,1120
XS Rating Curve= 0 ,0
Exp/Cntr=0.3,0.1

Type RM Length L Ch R = 1 ,44374   ,1788.9,1788.9,1788.9
XS GIS Cut Line= 4
 2369089.7965844 854375.053921282369327.40238801854113.284815615
2369250.88526481852808.4665042992369113.95988646852627.241738838
#Sta/Elev= 30
       0  106.34   167.9  100.29   248.2   94.28   273.7   91.51     323   89.82
   349.6   87.08   396.6   84.68   409.7    85.2   432.7   83.91     482   83.41
   551.1   83.31   593.8   84.64   639.8    83.5   731.8   83.69   781.1   82.38
     906   83.12    1005   82.51 1011.74   77.25 1039.57   77.25    1045   82.63
  1366.2   82.26  1477.9   83.94  1543.7   83.92  1586.4   86.54  1622.5   91.17
  1677.7   96.54  1721.2  104.66  1736.4  106.38  1773.4   108.4 1887.72  111.44
#Mann= 3 ,0,0
       0     .12       0    1005    .055       0    1045     .12       0
Bank Sta=1005,1045
XS Rating Curve= 0 ,0
Exp/Cntr=0.3,0.1

Type RM Length L Ch R = 1 ,42585   ,,,
XS GIS Cut Line= 5
2370142.22106211854932.8558101562370856.77733069854502.020412922
2371115.97911439 852925.793349872371098.46548036852782.181550792
2371249.08273305852263.777983389
#Sta/Elev= 30
       0  116.08   230.6  113.31   507.7  105.44   675.1   99.24   714.9   96.46
  1055.8   86.24  1138.9   87.74  1281.9   83.19  1358.4   85.47  1418.2   84.13
  1428.2   82.72  1444.8   84.15  1670.9   81.72  1732.6   82.76  1744.1   81.59
  1757.4    83.2  1777.3   81.52    2013   81.28 2021.63      75 2046.96      75
    2053   81.07  2232.9   80.81  2272.8   82.67  2362.6   82.49  2508.4   91.53
  2554.7   98.82  2615.5  103.37    2718  104.93  2861.5  113.34  3116.3   118.4
#Mann= 3 ,0,0
       0     .12       0    2013    .055       0    2053     .12       0
Bank Sta=2013,2053
XS Rating Curve= 0 ,0
Exp/Cntr=0.3,0.1
LCMann Table=0

--- JefferiesCreek.g04 (geometry) ---

Geom Title=Natural
Program Version=6.60

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
River Reach=Jeffries Creek  ,Reach 1