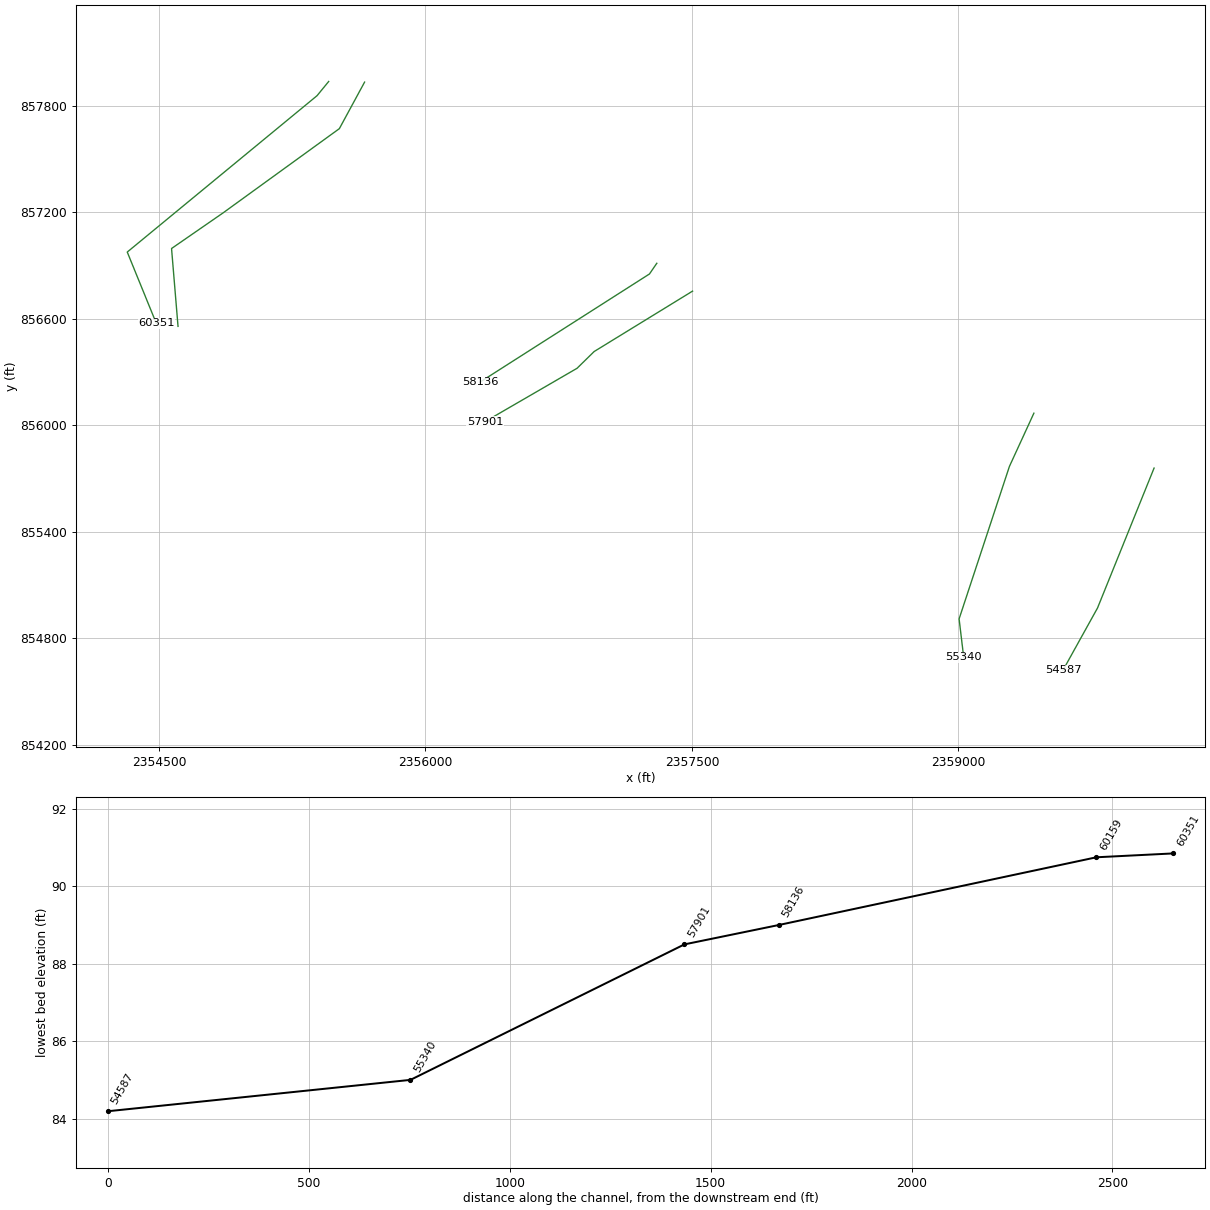
HEC-RAS study JefferiesCreek.prj: S-21-29 over Jeffries Creek

--- JefferiesCreek.g04 (geometry) --- (continued)

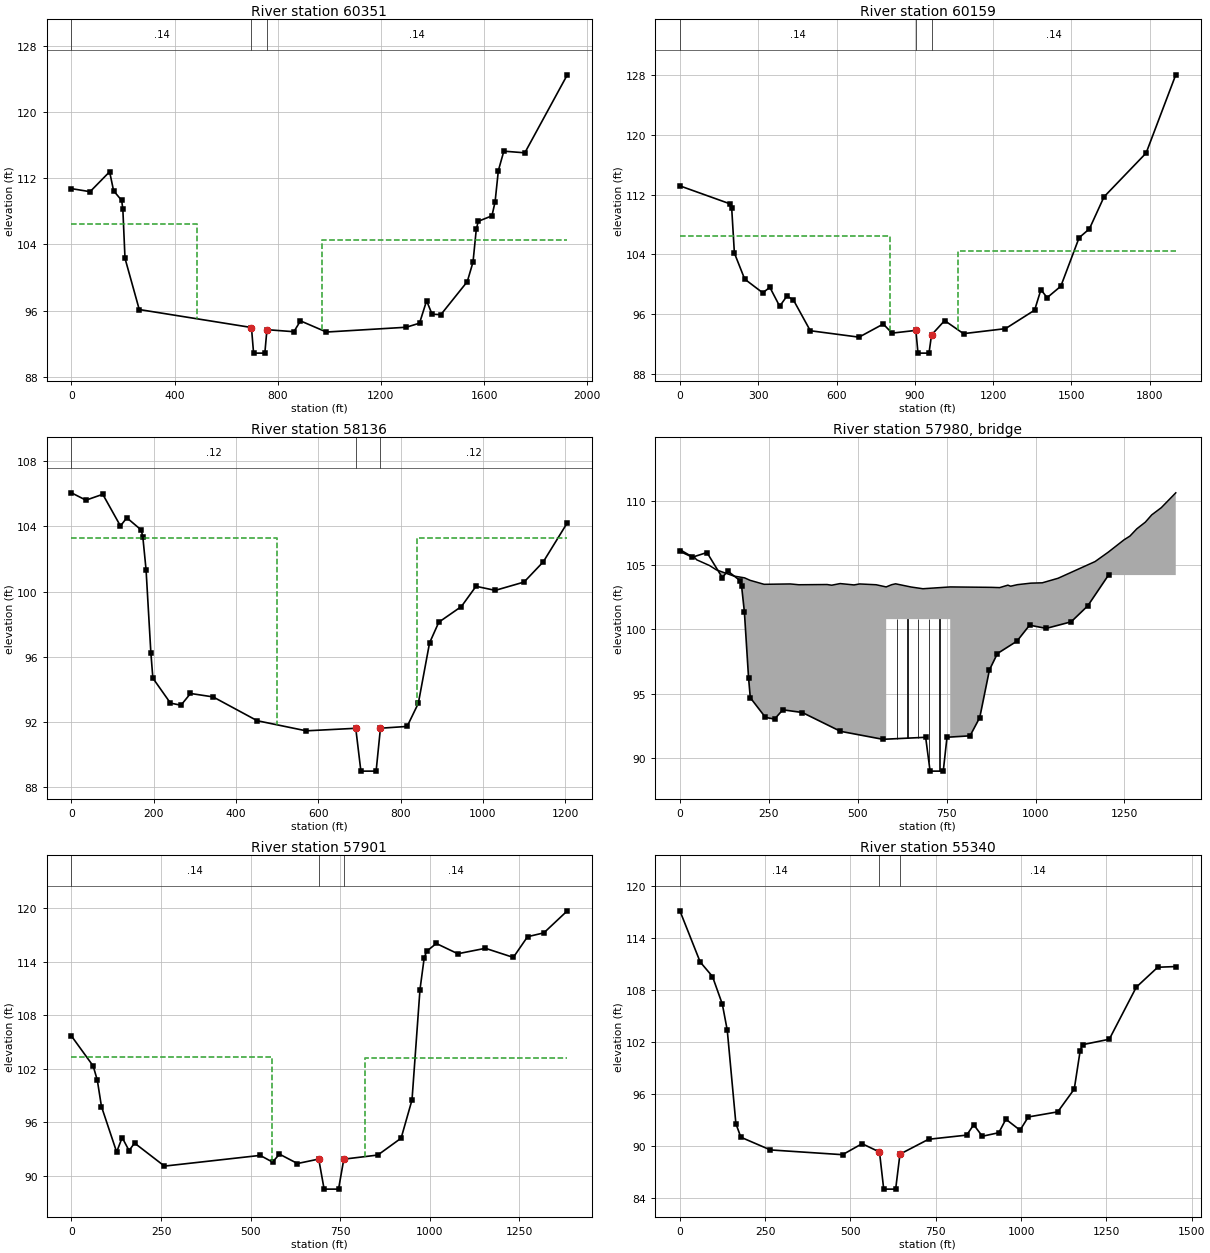
Type RM Length L Ch R = 1 ,60351   ,191.7,191.7,191.7
XS GIS Cut Line= 4
 2355455.0336001857937.1289831522355389.50318341857857.036251653
2354320.99333364856976.0162051632354484.81937534856573.732258315
#Sta/Elev= 30
       0  110.74    72.2  110.37     148  112.78   163.4  110.48   194.8  109.31
   199.3  108.22   207.6  102.32   262.9   96.12     698  93.948  706.18   90.85
  749.86   90.85     758  93.686   862.5   93.44     888   94.75   988.7    93.4
  1298.1   93.98  1349.7   94.47  1377.1   97.18  1398.3   95.56  1432.3    95.5
  1534.8   99.49  1557.1  101.86  1569.7   105.8  1577.4  106.79  1630.5  107.45
  1642.7  109.14  1655.3  112.91  1676.6  115.27    1758  115.071922.734   124.5
#Mann= 3 ,0,0
       0     .14       0     698     .06       0     758     .14       0
#XS Ineff= 2 , 0
       0     486   106.5     970       0   104.5
Permanent Ineff=
       F       F
Bank Sta=698,758
XS Rating Curve= 0 ,0
Exp/Cntr(USF)=0,0
Exp/Cntr=0.5,0.3

Type RM Length L Ch R = 1 ,60159   ,790.7,790.7,790.7
XS GIS Cut Line= 5
 2355657.0857182857933.4884044472355515.10314872857671.366737723
2354859.79898191857196.271216785 2354570.3729749856996.039388038
2354606.77876195856557.349654145
#Sta/Elev= 30
       0  113.16   193.8  110.73   198.4  110.18   208.7  104.16   248.2  100.67
   317.4   98.83   344.6   99.57   382.2   97.03   410.1    98.4   434.9   97.87
   499.6   93.75   686.2   92.89   779.1   94.65   812.6   93.43     904  93.796
  912.07   90.75  954.26   90.75     964  93.189  1014.2   95.11  1086.5   93.36
  1247.3   94.03    1359   96.51    1383   99.25  1406.9   98.18  1459.4   99.72
  1529.3  106.21  1568.8   107.4  1624.8  111.69  1786.1  117.561899.648  128.04
#Mann= 3 ,0,0
       0     .14       0     904     .06       0     964     .14       0
#XS Ineff= 2 , 0
       0  803.15   106.5 1064.85       0   104.5
Permanent Ineff=
       F       F
Bank Sta=904,964
XS Rating Curve= 0 ,0
Exp/Cntr(USF)=0,0
Exp/Cntr=0.5,0.3

Type RM Length L Ch R = 1 ,58136   ,234.6,234.6,234.6
XS GIS Cut Line= 3
2357302.15484009 856912.774707612357260.86198695856852.509462489
2356306.66227254856243.160872935
#Sta/Elev= 30
       0  106.06   35.18  105.61   76.11  105.97  119.03  104.03   134.6  104.53
  169.64  103.78  173.53  103.34  181.32  101.35     193   96.26  197.89    94.7
  240.57   93.17  266.18   93.04  289.34   93.76  344.21   93.55   451.5   92.09
  570.63   91.47     691  91.626  703.49      89  740.51      89     751   91.63
   815.9   91.74  843.15   93.16   870.4   96.86  892.88   98.13  947.75   99.09
   983.3  100.33 1030.02  100.08  1100.1  100.59 1146.82  101.83 1205.22  104.22
#Mann= 3 ,-1,0
       0     .12       0     691     .06       0     751     .12       0
#XS Ineff= 2 , 0
       0     500   103.3     840       0  103.27
Permanent Ineff=
       F       F
Bank Sta=691,751
XS Rating Curve= 0 ,0
Exp/Cntr(USF)=0,0
Exp/Cntr=0.5,0.3

Type RM Length L Ch R = 3 ,57980   ,,,
Bridge Culvert--1,0,-1,-1, 0
Deck Dist Width WeirC Skew NumUp NumDn MinLoCord MaxHiCord MaxSubmerge Is_Ogee
80,76.33,2.6,0, 44, 44, , , 0.98, 0, 2,2,,
       0  26.165  39.189  47.111  83.058  102.56 151.407 181.774 197.375 236.755
 310.389 334.142 413.879 426.778 450.621 489.582 505.186 551.919  579.99     580
     580 595.423 606.465 650.054  683.29     760     760 876.427 899.023  922.27
 929.902 948.981 987.141 1018.96 1063.461167.4081204.6491248.8161265.3611284.642
1308.6741326.7591353.4711394.276
 106.203 105.777 105.656 105.406 104.964 104.625 104.146 104.005 103.813 103.503
 103.531  103.47 103.487 103.434 103.561 103.455 103.531 103.469   103.3   103.3
   103.3 103.474 103.542 103.293  103.16   103.3   103.3 103.267 103.247 103.438
 103.356 103.476 103.594  103.62 103.974  105.27 106.003 106.958 107.247 107.809
 108.328 108.896 109.451 110.605
                                                                                
                                                                                
   100.8   100.8   100.8   100.8   100.8   100.8
                                                                                
                                
       0  26.165  39.189  47.111  83.058  102.56 151.407 181.774 197.375 236.755
 310.389 334.142 413.879 426.778 450.621 489.582 505.186 551.919 595.423  599.99
     600     600 606.465 650.054  683.29     780     780 876.427 899.023  922.27
 929.902 948.981 987.141 1018.96 1063.461167.4081204.6491248.8161265.3611284.642
1308.6741326.7591353.4711394.276
 106.203 105.777 105.656 105.406 104.964 104.625 104.146 104.005 103.813 103.503
 103.531  103.47 103.487 103.434 103.561 103.455 103.531 103.469 103.474   103.3
   103.3   103.3 103.542 103.293  103.16   103.3   103.3 103.267 103.247 103.438
 103.356 103.476 103.594  103.62 103.974  105.27 106.003 106.958 107.247 107.809
 108.328 108.896 109.451 110.605
                                                                                
                                                                                
           100.8   100.8   100.8   100.8   100.8
                                                                                
                                
Pier Skew, UpSta & Num, DnSta & Num=  ,610, 2 ,630, 2 , 0 , 0 , 0 ,,
     1.3     1.3
    88.5   100.8
     1.3     1.3
    88.5   100.8
Pier Skew, UpSta & Num, DnSta & Num=  ,640, 2 ,660, 2 , 0 , 0 , 0 ,,
     1.3     1.3
    88.5   100.8
     1.3     1.3
    88.5   100.8
Pier Skew, UpSta & Num, DnSta & Num=  ,670, 2 ,690, 2 , 0 , 0 , 0 ,,
     1.3     1.3
    88.5   100.8
     1.3     1.3
    88.5   100.8
Pier Skew, UpSta & Num, DnSta & Num=  ,700, 2 ,720, 2 , 0 , 0 , 0 ,,
     1.3     1.3
    88.5   100.8
     1.3     1.3
    88.5   100.8
Pier Skew, UpSta & Num, DnSta & Num=  ,730, 2 ,750, 2 , 0 , 0 , 0 ,,
     1.3     1.3
    88.5   100.8
     1.3     1.3
    88.5   100.8
Abutment Skew #Up #Dn= , 2 , 2
  580.01     600
    99.8    79.8
  600.01     620
    99.8    79.8
Abutment Skew #Up #Dn= , 2 , 2
     740  760.01
    79.8    99.8
     760  780.01
    79.8    99.8
BR Coef=-1 , 1 , 1 ,1.25, 0 ,,,0.8,0,2,0,
WSPro=,,,, 1 ,,,, 0 ,,,, 0 ,,,,-1 ,-1 ,-1 , 0 , 0 , 0 , 0 , 0
BC Design=,, 0 ,, 0 ,,,,,,
BC Use User HTab Curves=0
BC User HTab FreeFlow(D)= 0

Type RM Length L Ch R = 1 ,57901   ,681.8,681.8,681.8
XS GIS Cut Line= 4
 2357503.4505629856755.8917374742356949.68207244856415.692664835
2356853.29233519856321.1929224352356335.43374684856020.683741604
#Sta/Elev= 30
       0  105.66    60.6   102.3    72.2   100.7    83.7   97.76   126.1   92.66
   141.5   94.28   160.7   92.82   176.1   93.66   259.5   91.08   526.6   92.28
   561.2   91.53   580.5   92.42   630.6   91.37     690  91.867  705.04    88.5
  745.24    88.5     760  91.859   854.9   92.32   919.9   94.21   950.3    98.5
   972.5  110.85   984.4  114.45   991.7  115.18  1018.1  116.03  1078.1  114.88
  1155.1  115.49    1233  114.47  1272.7  116.79  1318.2  117.22 1383.64  119.69
#Mann= 3 ,0,0
       0     .14       0     690    .055       0     760     .14       0
#XS Ineff= 2 , 0
       0 560.865   103.3 819.135       0  103.25
Permanent Ineff=
       F       F
Bank Sta=690,760
XS Rating Curve= 0 ,0
Exp/Cntr(USF)=0,0
Exp/Cntr=0.5,0.3

Type RM Length L Ch R = 1 ,55340   ,753,753,753
XS GIS Cut Line= 4
2359425.08758033856068.2085669432359287.30695591855768.152984876
2359004.09122794854909.320425999  2359030.116457854691.933218583
#Sta/Elev= 30
       0  117.16   59.38  111.25   95.49  109.57  124.37  106.37  138.81  103.36
  164.09   92.57  178.53      91  265.18   89.53  476.73   88.98  534.02   90.25
     585   89.29  597.41      85  632.39      85     645  89.042  728.75   90.76
  840.47   91.24  861.26   92.44  886.42   91.11  934.79   91.52  955.52   93.08
  996.98   91.81 1021.17   93.34 1107.54   93.93 1155.91   96.56 1173.19  100.98
  1180.1  101.69 1258.59  102.32 1337.78  108.34 1400.57  110.64 1453.44  110.72
#Mann= 3 ,-1,0
       0     .14       0     585    .055       0     645     .14       0
Bank Sta=585,645
XS Rating Curve= 0 ,0
Exp/Cntr(USF)=0,0
Exp/Cntr=0.3,0.1

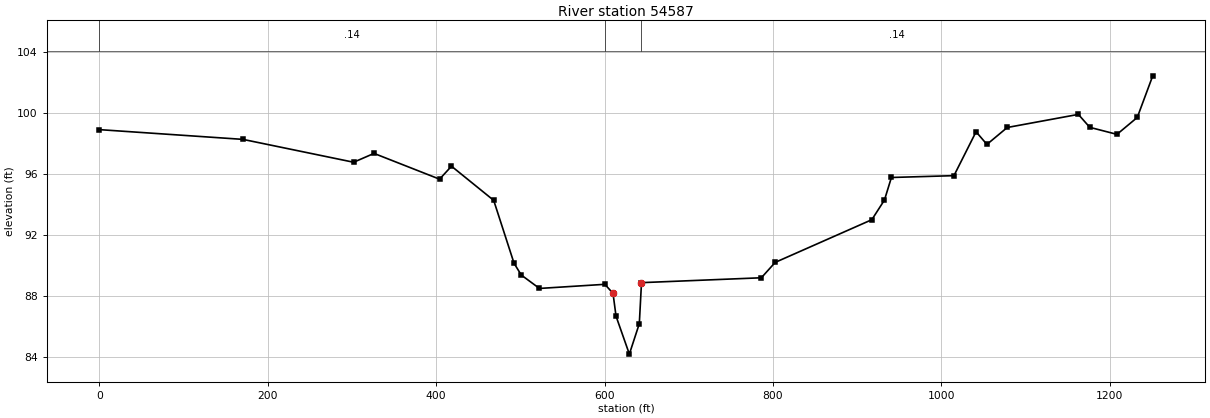
Type RM Length L Ch R = 1 ,54587   ,293.3,293.3,293.3
XS GIS Cut Line= 3
2360101.74353581855758.9676099142359783.31720382854970.556259074
2359588.89343381 854619.98111472
#Sta/Elev= 30
       0   98.92  170.56   98.28  302.03   96.78  326.26   97.36  404.11   95.67
  418.27   96.52  468.39   94.28  492.58   90.15  501.16   89.38  522.75    88.5
   600.4   88.77  610.11   88.18   613.7   86.68  629.52   84.19  641.35   86.19
  643.94   88.88  786.29    89.2  802.76   90.21  917.51   93.01  932.51    94.3
  940.77   95.78 1015.06    95.9 1041.32   98.78 1054.21   97.95 1078.34   99.06
 1162.81   99.92 1176.39   99.07 1208.67   98.61  1232.8   99.72 1251.17  102.45
#Mann= 3 ,-1,0
       0     .14       0   600.4    .055       0  643.94     .14       0
Bank Sta=610.11,643.94
XS Rating Curve= 0 ,0
Exp/Cntr(USF)=0,0
Exp/Cntr=0.3,0.1