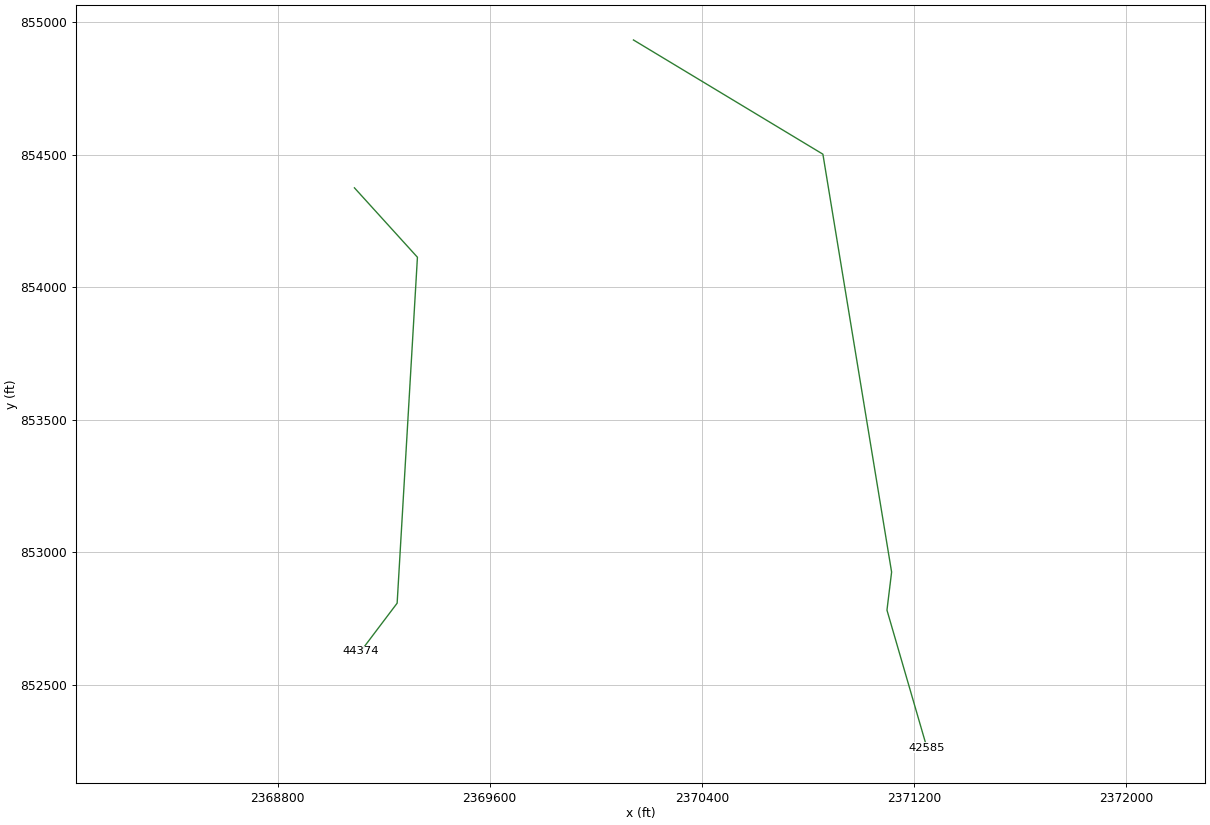
HEC-RAS study JefferiesCreek.prj: S-21-29 over Jeffries Creek

--- JefferiesCreek.g07 (geometry) --- (continued)

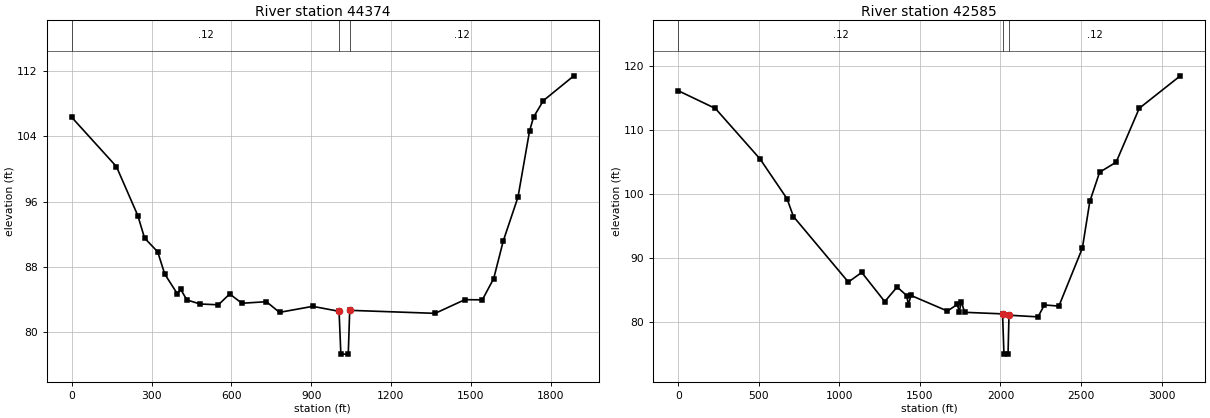
Type RM Length L Ch R = 1 ,44374   ,1788.9,1788.9,1788.9
XS GIS Cut Line= 4
 2369089.7965844 854375.053921282369327.40238801854113.284815615
2369250.88526481852808.4665042992369113.95988646852627.241738838
#Sta/Elev= 30
       0  106.34   167.9  100.29   248.2   94.28   273.7   91.51     323   89.82
   349.6   87.08   396.6   84.68   409.7    85.2   432.7   83.91     482   83.41
   551.1   83.31   593.8   84.64   639.8    83.5   731.8   83.69   781.1   82.38
     906   83.12    1005   82.51 1011.74   77.25 1039.57   77.25    1045   82.63
  1366.2   82.26  1477.9   83.94  1543.7   83.92  1586.4   86.54  1622.5   91.17
  1677.7   96.54  1721.2  104.66  1736.4  106.38  1773.4   108.4 1887.72  111.44
#Mann= 3 ,0,0
       0     .12       0    1005    .055       0    1045     .12       0
Bank Sta=1005,1045
XS Rating Curve= 0 ,0
Exp/Cntr=0.3,0.1

Type RM Length L Ch R = 1 ,42585   ,,,
XS GIS Cut Line= 5
2370142.22106211854932.8558101562370856.77733069854502.020412922
2371115.97911439 852925.793349872371098.46548036852782.181550792
2371249.08273305852263.777983389
#Sta/Elev= 30
       0  116.08   230.6  113.31   507.7  105.44   675.1   99.24   714.9   96.46
  1055.8   86.24  1138.9   87.74  1281.9   83.19  1358.4   85.47  1418.2   84.13
  1428.2   82.72  1444.8   84.15  1670.9   81.72  1732.6   82.76  1744.1   81.59
  1757.4    83.2  1777.3   81.52    2013   81.28 2021.63      75 2046.96      75
    2053   81.07  2232.9   80.81  2272.8   82.67  2362.6   82.49  2508.4   91.53
  2554.7   98.82  2615.5  103.37    2718  104.93  2861.5  113.34  3116.3   118.4
#Mann= 3 ,0,0
       0     .12       0    2013    .055       0    2053     .12       0
Bank Sta=2013,2053
XS Rating Curve= 0 ,0
Exp/Cntr=0.3,0.1
LCMann Table=0