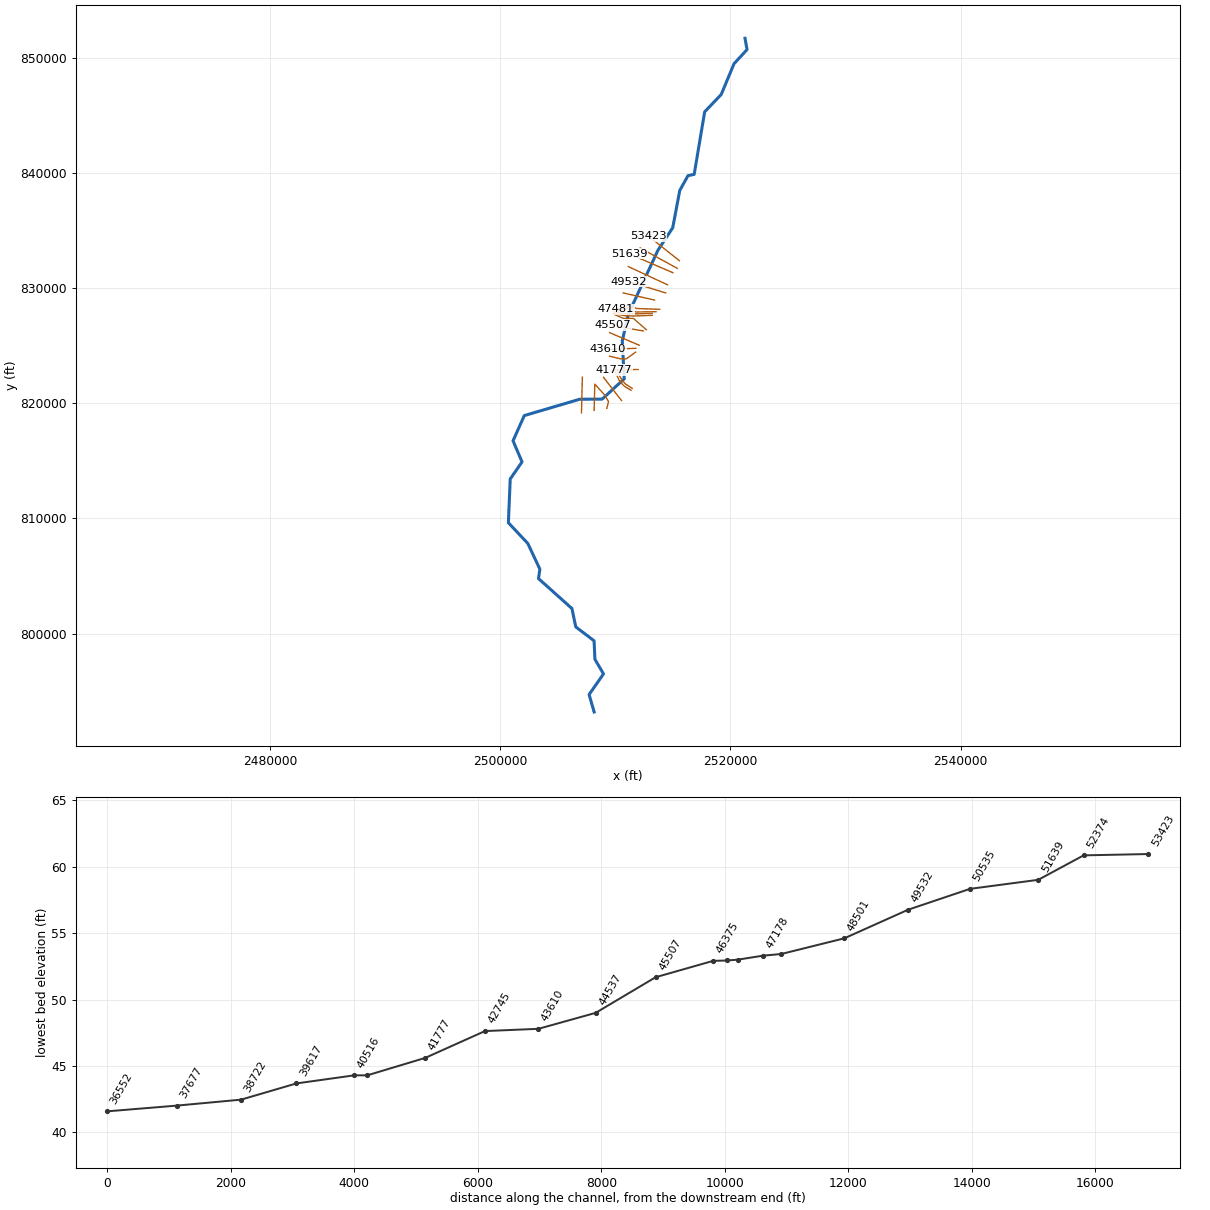
--- ReedyCreek.prj (project) ---

Proj Title=S-34-32 over Reedy Creek
Current Plan=p05
Default Exp/Contr=0.3,0.1
English Units
Geom File=g01
Geom File=g05
Geom File=g03
Geom File=g06
Flow File=f01
Flow File=f02
Flow File=f03
Plan File=p02
Plan File=p01
Plan File=p06
Plan File=p03
Plan File=p05
Y Axis Title=Elevation
X Axis Title(PF)=Main Channel Distance
X Axis Title(XS)=Station
BEGIN DESCRIPTION:
END DESCRIPTION:
DSS File=dss
DSS Export Rating Curves= 0
DSS Export Rating Curve Sorted= 0
DSS Export Volume Flow Curves= 0
DXF OffsetX= 0
DXF OffsetY= 0
DXF ScaleX= 1
DXF ScaleY= 10

--- ReedyCreek.p05 (plan) ---

Plan Title=Proposed Conditions
Program Version=6.60
Short Identifier=PROP
Geom File=g06
Flow File=f01
Subcritical Flow
K Sum by GR= 0
Std Step Tol= 0.01
Critical Tol= 0.01
Num of Std Step Trials= 20
Max Error Tol= 0.3
Flow Tol Ratio= 0.001
Split Flow NTrial= 30
Split Flow Tol= 0.02
Split Flow Ratio= 0.02
Log Output Level= 0
Friction Slope Method= 1
Unsteady Friction Slope Method= 2
Unsteady Bridges Friction Slope Method= 1
Parabolic Critical Depth
Global Vel Dist= 0 , 0 , 0
Global Log Level= 0
CheckData=True
Encroach Param=-1 ,0,0, 0
Flow Ratio Tolerance=0.1
Flow Ratio Min Ratio=0.5
Flow Ratio Max Ratio=4
Flow Ratio Max Iterations= 10
Computation Interval=1MIN
Output Interval=1HOUR
Instantaneous Interval=1HOUR
Mapping Interval=1HOUR
Computation Time Step Use Courant=        0
Computation Time Step Use Time Series=    0
Computation Time Step Count To Double=0
Computation Time Step Max Doubling=0
Computation Time Step Max Halving=0
Computation Time Step Residence Courant=0
Run HTab= 0
Run UNet= 0
Run Sediment= 0
Run PostProcess= 0
Run WQNet= 0
Run RASMapper= 0
UNET Theta= 1
UNET Theta Warmup= 1
UNET ZTol= 0.02
UNET ZSATol= 0.02
UNET MxIter= 20
UNET Max Iter WO Improvement= 0
UNET MaxInSteps= 0
UNET DtIC= 0
UNET DtMin= 0
UNET MaxCRTS= 20
UNET WFStab= 2
UNET SFStab= 1
UNET WFX= 1
UNET SFX= 1
UNET Gravity=32.17405
UNET 1D Methodology=Finite Difference
UNET DSS MLevel= 4
UNET Pardiso=0
UNET DZMax Abort= 100
UNET Use Existing IB Tables=-1
UNET Froude Reduction=False
UNET Froude Limit= 0.8
UNET Froude Power= 4
UNET D1 Cores= 0
UNET WindReference=Eulerian
UNET WindDragFormulation=Hsu (1988)
UNET D2 Coriolis=0
UNET D2 Cores= 0
UNET D2 Theta= 1
UNET D2 Theta Warmup= 1
UNET D2 Z Tol= 0.01
UNET D2 Volume Tol= 0.01
UNET D2 Max Iterations= 20
UNET D2 Advanced Convergence=0
UNET D2 WS Max Tol=0.15
UNET D2 WS RMS Tol=0.002
UNET D2 WS Stall Tol=1
UNET D2 Equation= 0
UNET D2 RampUpFraction=0.1
UNET D2 TimeSlices= 1
UNET D2 Turbulence Formulation=None
UNET D2 Eddy Viscosity=0.3
UNET D2 Transverse Eddy Viscosity=0.1
UNET D2 Smagorinsky Mixing=0.05
UNET D2 BCVolumeCheck=0
UNET D2 Cores=0
UNET D2 SolverType=PARDISO (Direct)
UNET D2 Minimum Iterations= 3
UNET D2 Maximum Iterations= 30
UNET D2 Restart Number= 10
UNET D2 Relaxation Coeff=1.3
UNET D2 SOR Precondition Iterations= 10
UNET D2 ILUT Maximum Fill= 8
UNET D2 ILUT Tolerance=1E-08
UNET D2 Convergence Tolerance=0.00001
PS Theta= 1
PS WS Tol= 0.01
PS Volume Tol= 0.01
PS Max Iterations= 20
PS Equation= 0
PS Advance Time Step=-1
PS Target Courant=0.9
PS Time Slices= 1
PS Iterate With 2D=0
PS Project Initial WSE from DS=-1
PS Ramp Up Initial WSE from US=-1
PS Cores=0
UNET D1D2 MaxIter= 0
UNET D1D2 ZTol=0.01
UNET D1D2 QTol=0.1
UNET D1D2 MinQTol=1
Write IC File= 0
Write IC File at Fixed DateTime=0
Write IC File at Sim End=0
Echo Input=False
Echo Parameters=False
Echo Output=False
Write Detailed= 0
HDF Write Warmup=0
HDF Write Time Slices=0
HDF Flush=0
HDF Compression= 1
HDF Chunk Size= 1
HDF Spatial Parts= 1
HDF Use Max Rows=0
HDF Fixed Rows= 1
Calibration Method= 0
Calibration Iterations= 20
Calibration Max Change=0.05
Calibration Tolerance=0.2
Calibration Maximum=1.5
Calibration Minimum=0.5
Calibration Optimization Method= 1
WQ AD Non Conservative
WQ ULTIMATE=-1
WQ Max Comp Step=1HOUR
WQ Output Interval=15MIN
WQ Output Selected Increments= 0
WQ Create Restart=0
WQ Fixed Restart=0
WQ System Summary=0
WQ Write To DSS=0
Sorting and Armoring Iterations= 10
XS Update Threshold= 0.02
Bed Roughness Predictor= 0
Processes Affected by Predictor=Sediment Only
Hydraulics Update Threshold= 0.02
Energy Slope Method= 1
Volume Change Method= 1
Sediment Retention Method= 0
Sediment TS Multiplier= 1
Warm Up Method= 0
XS Weighting Method= 0
Number of US Weighted Cross Sections= 1
Number of DS Weighted Cross Sections= 1
Upstream XS Weight=0
Main XS Weight=1
Downstream XS Weight=0
Number of DS XS's Weighted with US Boundary= 1
Upstream Boundary Weight= 1
Weight of XSs Associated with US Boundary= 0
Number of US XS's Weighted with DS Boundary= 1
Downstream Boundary Weight= 0.5
Weight of XSs Associated with DS Boundary= 0.5
Percentile Method= 0
Sediment Output Level= 3
Mass or Volume Output= 0
Output Increment Type= 1
Profile and TS Output Increment= 1
Transport Output Increment 1
XS Output Flag= 0
XS Output Increment= 10
Read HDF5 Sediment Hotstart= 0
Sediment Hotstart Type= 0
Write Gradation File= 0
Read Gradation Hotstart= 0
Write HDF5 File= 1
Write Binary Output= 1
Write DSS Sediment File= 0
DSS Sediment Output Type= 1
SV Curve= 0
Specific Gage Flag= 0
Subcell Erosion Methods= 0
Subcell Deposition Methods= 0
Advection Scheme= 1
Matrix Solver= 0
Implicit Weighting Factor= 1
Maximum Outer Loop Convergence Iterations= 5
Convergence Maximum Absolute= 0.001
Convergence RMSE= 0.0001
Grain Fractions Max Abs Error= 0.001
Max Subgrid Regions= 1
Max Subgrid Length Scale= 3.402823E+38
Initial Layer Thickness= 3
Min Layer Thickness= 0.1
Max Layer Thickness= 6
Number of Layers= 5

--- ReedyCreek.p01 (plan) ---

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Plan Title=Exisiting Conditions
Short Identifier=EX
Geom File=g01
Flow File=f01

--- ReedyCreek.p02 (plan) ---

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Plan Title=Natural Conditions
Short Identifier=NAT
Geom File=g03
Flow File=f01

--- ReedyCreek.p03 (plan) ---

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Plan Title=Sensitivity Analysis
Short Identifier=SENSITIVITY
Geom File=g01
Flow File=f02

--- ReedyCreek.p06 (plan) ---

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Plan Title=Duplicate Effective
Short Identifier=DE
Geom File=g05
Flow File=f03
BEGIN DESCRIPTION:
100Year Run
END DESCRIPTION:
UNET D2 Turbulence Formulation=Non-Conservative (original)
UNET D2 Smagorinsky Mixing=0

--- ReedyCreek.f01 (steady flow) ---

Flow Title=USGS Regression Equations
Program Version=6.60
BEGIN FILE DESCRIPTION:
Flow input from Streamstats
END FILE DESCRIPTION:
Number of Profiles= 6
Profile Names=2-Year,10-Year,25-Year,50-Year,100-Year,500-Year
River Rch & RM=Reedy Creek,Reach-1         ,53423
     332     905    1280    1630    1980    2870
River Rch & RM=Reedy Creek,Reach-1         ,40714
     355     964    1370    1740    2110    3050
Boundary for River Rch & Prof#=Reedy Creek,Reach-1         , 1
Up Type= 0
Dn Type= 3
Dn Slope=0.0006
Boundary for River Rch & Prof#=Reedy Creek,Reach-1         , 2
Up Type= 0
Dn Type= 3
Dn Slope=0.0006
Boundary for River Rch & Prof#=Reedy Creek,Reach-1         , 3
Up Type= 0
Dn Type= 3
Dn Slope=0.0006
Boundary for River Rch & Prof#=Reedy Creek,Reach-1         , 4
Up Type= 0
Dn Type= 3
Dn Slope=0.0006
Boundary for River Rch & Prof#=Reedy Creek,Reach-1         , 5
Up Type= 0
Dn Type= 3
Dn Slope=0.0006
Boundary for River Rch & Prof#=Reedy Creek,Reach-1         , 6
Up Type= 0
Dn Type= 3
Dn Slope=0.0006
DSS Import GetInterval= 0
DSS Import GetPeak= 0
DSS Import FillOption= 0

--- ReedyCreek.f02 (steady flow) ---

Flow Title=USGS Regression Equations_Sensitivity
Program Version=6.60
Number of Profiles= 3
Profile Names=-3ft,100-Year,+3ft
River Rch & RM=Reedy Creek,Reach-1         ,53423
    1980    1980    1980
River Rch & RM=Reedy Creek,Reach-1         ,40714
    2110    2110    2110
Boundary for River Rch & Prof#=Reedy Creek,Reach-1         , 1
Up Type= 0
Dn Type= 1
Dn Known WS=49.41
Boundary for River Rch & Prof#=Reedy Creek,Reach-1         , 2
Up Type= 0
Dn Type= 1
Dn Known WS=52.41
Boundary for River Rch & Prof#=Reedy Creek,Reach-1         , 3
Up Type= 0
Dn Type= 1
Dn Known WS=55.41
DSS Import GetInterval= 0
DSS Import GetPeak= 0
DSS Import FillOption= 0

--- ReedyCreek.f03 (steady flow) ---

Flow Title=100-year Single
Number of Profiles=1
Profile Names=100-year
River Rch & RM= Reedy Creek,Reach-1,74559
     312
River Rch & RM= Reedy Creek,Reach-1,70392
     474
River Rch & RM= Reedy Creek,Reach-1,68496
     579
River Rch & RM= Reedy Creek,Reach-1,65942
     962
River Rch & RM= Reedy Creek,Reach-1,64022
     968
River Rch & RM= Reedy Creek,Reach-1,63014
    1258
River Rch & RM= Reedy Creek,Reach-1,57566
    1343
River Rch & RM= Reedy Creek,Reach-1,54481
    1416
River Rch & RM= Reedy Creek,Reach-1,52390
    1488
River Rch & RM= Reedy Creek,Reach-1,49548
    1565
River Rch & RM= Reedy Creek,Reach-1,42761
    1633
River Rch & RM= Reedy Creek,Reach-1,39633
    1706
River Rch & RM= Reedy Creek,Reach-1,34982
    1771
River Rch & RM= Reedy Creek,Reach-1,31579
    1830
River Rch & RM= Reedy Creek,Reach-1,29680
    2327
River Rch & RM= Reedy Creek,Reach-1,28764
    2418
River Rch & RM= Reedy Creek,Reach-1,25260
    2470
River Rch & RM= Reedy Creek,Reach-1,24110
    2526
River Rch & RM= Reedy Creek,Reach-1,19959
    2569
River Rch & RM= Reedy Creek,Reach-1,17398
    2600
River Rch & RM= Reedy Creek,Reach-1,15172
    2692
River Rch & RM= Reedy Creek,Reach-1,12268
    2792
River Rch & RM= Reedy Creek,Reach-1,8528
    2845
Boundary for River Rch & Prof#=Reedy Creek,Reach-1,1
Up Type=0
Dn Type=3
Dn Slope=0.002

--- ReedyCreek.g06 (geometry) ---

Geom Title=Proposed Conditions
Program Version=6.60

River Reach=Reedy Creek     ,Reach-1
Reach XY= 30
      2521260.84       851701.35      2521441.03       850721.59
      2520303.61       849482.83      2519198.09        846818.3
       2517758.5       845314.57      2516847.41       839879.43
      2516310.21       839769.45      2515595.34       838483.54
      2514985.33       835246.65      2513705.89       833304.35
      2511145.41       827777.49      2510603.61       825423.42
      2510773.18       822124.61      2508857.86       820363.44
      2506904.01       820351.88      2502093.28       818932.63
      2501116.16        816741.5      2501898.65       814911.78
      2500873.08       813429.07      2500711.98       809627.98
        2502400.       807827.65      2503447.41       805594.48
      2503327.66       804778.55      2506231.81       802176.61
      2506562.37       800584.32      2508156.25       799372.75
      2508226.57       797766.14      2508973.64       796498.33
      2507721.67       794706.18      2508160.18       793193.65

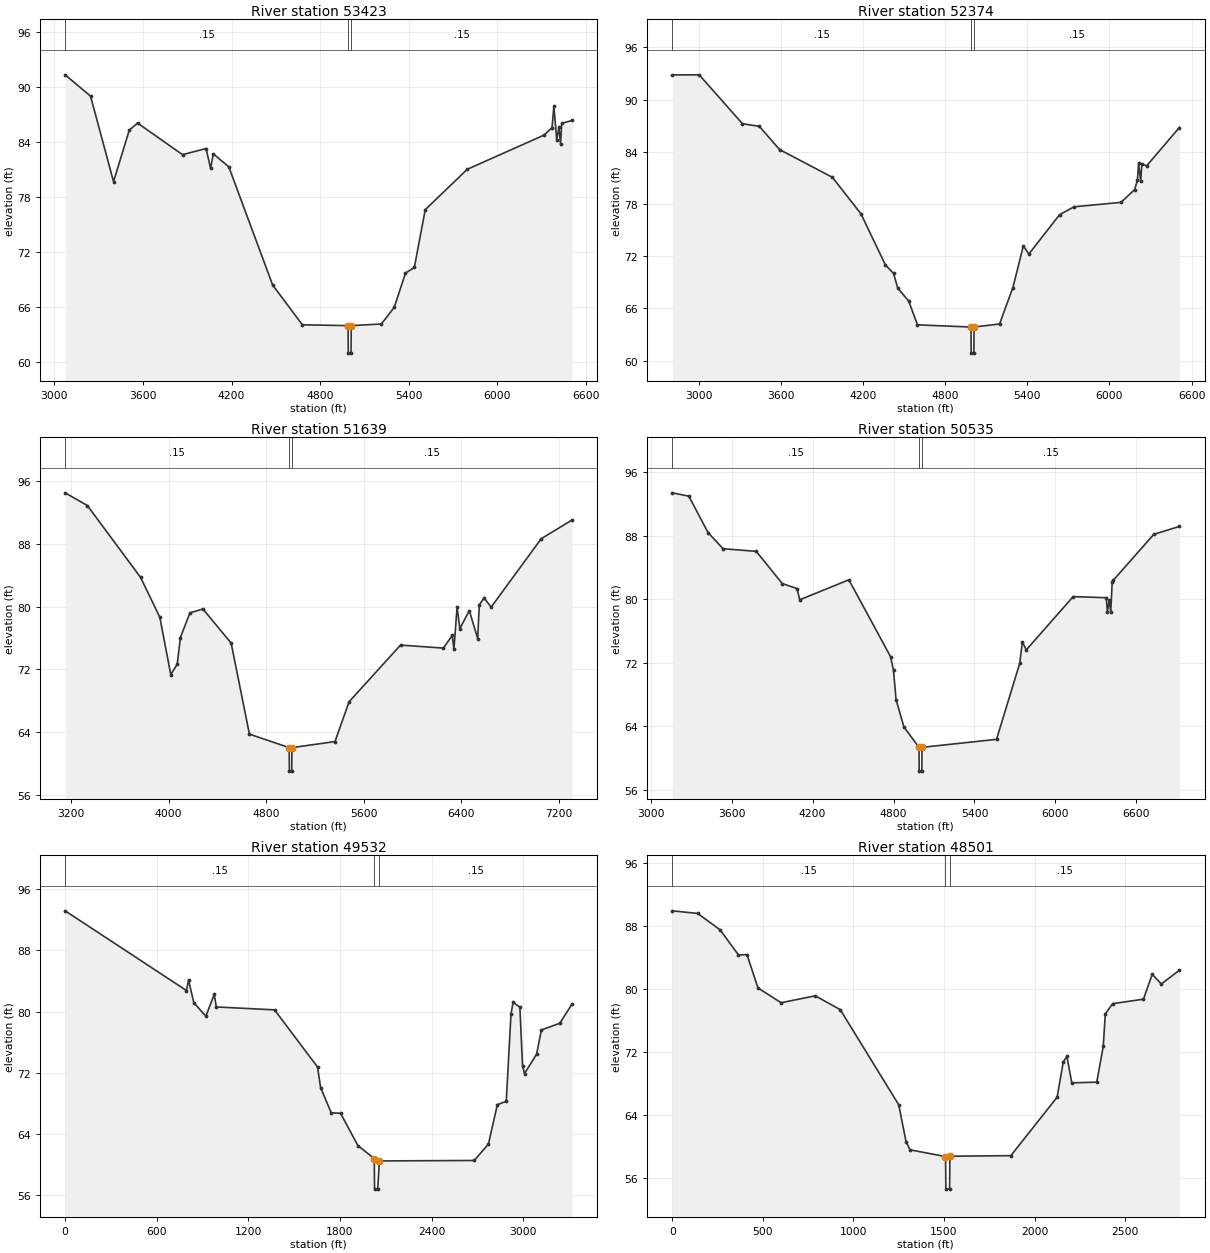
Type RM Length L Ch R = 1 ,53423   ,898.7,1048.6,1095.3
BEGIN DESCRIPTION:
Reedy Creek XS 45.0
END DESCRIPTION:
XS GIS Cut Line= 2
      2515559.88       832387.45      2512870.86       834522.25
#Sta/Elev= 30
  3073.2   91.31  3245.1   88.99  3400.9   79.66  3507.5   85.27  3563.6   86.05
  3868.3    82.6  4027.7   83.27  4058.2    81.1  4076.4   82.69  4181.3   81.28
  4478.6   68.38  4679.8   64.04  4989.3   63.95  4990.8   60.95  5009.2   60.95
  5010.7   63.95    5215   64.13  5302.1   65.95  5378.2   69.68  5438.3    70.3
  5511.9    76.6  5796.2      81  6317.2   84.74  6370.9   85.56  6383.1   87.88
  6402.5   84.22  6417.1   85.58  6428.2   83.78  6436.2   86.02  6506.6   86.33
#Mann= 3 ,-1,0
  3073.2     .15       0  4989.3     .05       0  5010.7     .15       0
Bank Sta=4989.3,5010.7
XS Rating Curve= 0 ,0
Exp/Cntr=0.3,0.1

Type RM Length L Ch R = 1 ,52374   ,636.3,735,770.9
BEGIN DESCRIPTION:
Reedy Creek XS 44.0
END DESCRIPTION:
XS GIS Cut Line= 2
       2515395.7       831710.04       2512152.4       833495.91
#Sta/Elev= 30
  2807.9   92.83  3003.9   92.84  3319.8   87.22  3443.2   86.92  3590.9   84.25
  3976.7   81.06  4184.9   76.87  4363.7   70.99  4423.5   70.01  4453.7   68.34
  4533.8   66.84    4598    64.1  4988.8   63.85  4990.3   60.85  5009.7   60.85
  5011.2   63.85  5197.5    64.2    5295   68.39  5371.1   73.18  5411.3   72.24
  5636.3   76.77  5741.5   77.67  6084.6   78.18  6183.9   79.65  6204.2   80.71
  6212.9   82.65  6228.2   80.64  6236.9   82.61  6271.3   82.37  6510.4   86.78
#Mann= 3 ,-1,0
  2807.9     .15       0  4988.8     .05       0  5011.2     .15       0
Bank Sta=4988.8,5011.2
XS Rating Curve= 0 ,0
Exp/Cntr=0.3,0.1

Type RM Length L Ch R = 1 ,51639   ,1115.1,1104.7,1085.4
BEGIN DESCRIPTION:
Reedy Creek XS 43.0
END DESCRIPTION:
XS GIS Cut Line= 2
      2515005.69       831340.56      2511187.66       832982.72
#Sta/Elev= 30
    3152   94.52    3334    92.9  3770.9   83.72  3928.4   78.64    4018   71.33
  4070.8   72.64  4096.9   76.06    4175    79.2  4281.6    79.7  4512.9   75.35
  4662.8   63.73  4988.8   62.01  4990.3   59.01  5009.7   59.01  5011.2   62.01
  5364.1   62.78  5480.2   67.87  5901.5   75.09  6253.1   74.71  6325.4   76.32
  6339.5   74.61  6365.1    79.9    6388    77.2  6465.6   79.49  6533.9   75.93
  6547.5   80.23  6586.3    81.1  6644.7   79.94  7054.7   88.66  7308.2   91.06
#Mann= 3 ,-1,0
    3152     .15       0  4988.8     .05       0  5011.2     .15       0
Bank Sta=4988.8,5011.2
XS Rating Curve= 0 ,0
Exp/Cntr=0.3,0.1

Type RM Length L Ch R = 1 ,50535   ,897.4,1002.3,1066.3
BEGIN DESCRIPTION:
Reedy Creek XS 42.0
END DESCRIPTION:
XS GIS Cut Line= 2
      2514533.48       830293.72      2511126.05       831874.28
#Sta/Elev= 30
  3161.5   93.43  3283.4   93.01  3425.7   88.42  3537.2   86.38  3782.8   86.05
  3975.6   81.99  4085.1   81.35  4105.2   79.94  4469.2   82.46    4778   72.77
    4800   71.03  4818.9   67.35  4877.3   63.89  4988.8   61.33  4990.3   58.33
  5009.7   58.33  5011.2   61.33  5563.4   62.34  5735.3   71.94  5755.1   74.63
  5783.8   73.62  6131.1   80.34  6376.1    80.2  6384.7   78.41  6397.9   79.89
  6409.6   78.41  6420.1   82.15  6429.8   82.43  6728.2   88.19  6917.7   89.19
#Mann= 3 ,-1,0
  3161.5     .15       0  4988.8     .05       0  5011.2     .15       0
Bank Sta=4988.8,5011.2
XS Rating Curve= 0 ,0
Exp/Cntr=0.3,0.1

Type RM Length L Ch R = 1 ,49532   ,1032.6,1031.5,1046
BEGIN DESCRIPTION:
Reedy Creek XS 41.0
END DESCRIPTION:
XS GIS Cut Line= 2
      2514367.48       829585.33      2511195.12       830566.97
#Sta/Elev= 30
       0   93.18   794.7   82.75   808.4   84.12   842.8   81.16   921.8   79.39
   976.7   82.24   990.4    80.6  1371.6   80.22  1653.2   72.74  1673.8   70.02
  1742.8   66.76  1804.3   66.68  1917.6   62.46  2025.1   60.76  2026.6   56.76
  2047.4   56.76  2058.4   60.45    2680   60.51  2772.7   62.66  2831.1   67.81
  2889.5   68.26  2920.4   79.63  2934.1   81.22  2978.8   80.58  2995.9   72.92
    3009   71.88  3088.2   74.42  3119.6   77.59  3239.8   78.46  3320.8   80.99
#Mann= 3 ,0,0
       0     .15       0  2025.1     .05       0  2058.4     .15       0
Bank Sta=2025.1,2058.4
XS Rating Curve= 0 ,0
Exp/Cntr=0.3,0.1

Type RM Length L Ch R = 1 ,48501   ,990.4,1020.1,1129.3
BEGIN DESCRIPTION:
Reedy Creek XS 40.0
END DESCRIPTION:
XS GIS Cut Line= 2
      2513409.76       828962.84      2510680.34       829585.34
#Sta/Elev= 30
       0   89.95   139.6   89.62   264.1   87.53     365   84.35   412.1   84.39
   472.7   80.16   600.6   78.28     789   79.16     927    77.4    1250   65.32
  1290.4   60.65  1312.4    59.6    1508   58.75  1508.6   58.61  1510.1   54.61
  1530.9   54.61  1532.6   58.79  1869.1   58.86  2124.8   66.29  2158.5   70.76
  2178.7   71.47  2205.6   68.11  2343.6   68.19  2379.3   72.73  2390.7   76.85
    2431   78.16  2601.2   78.73  2649.8   81.89  2700.2   80.66  2799.5    82.4
#Mann= 3 ,0,0
       0     .15       0    1508     .05       0  1532.6     .15       0
Bank Sta=1508,1532.6
XS Rating Curve= 0 ,0
Exp/Cntr=0.3,0.1

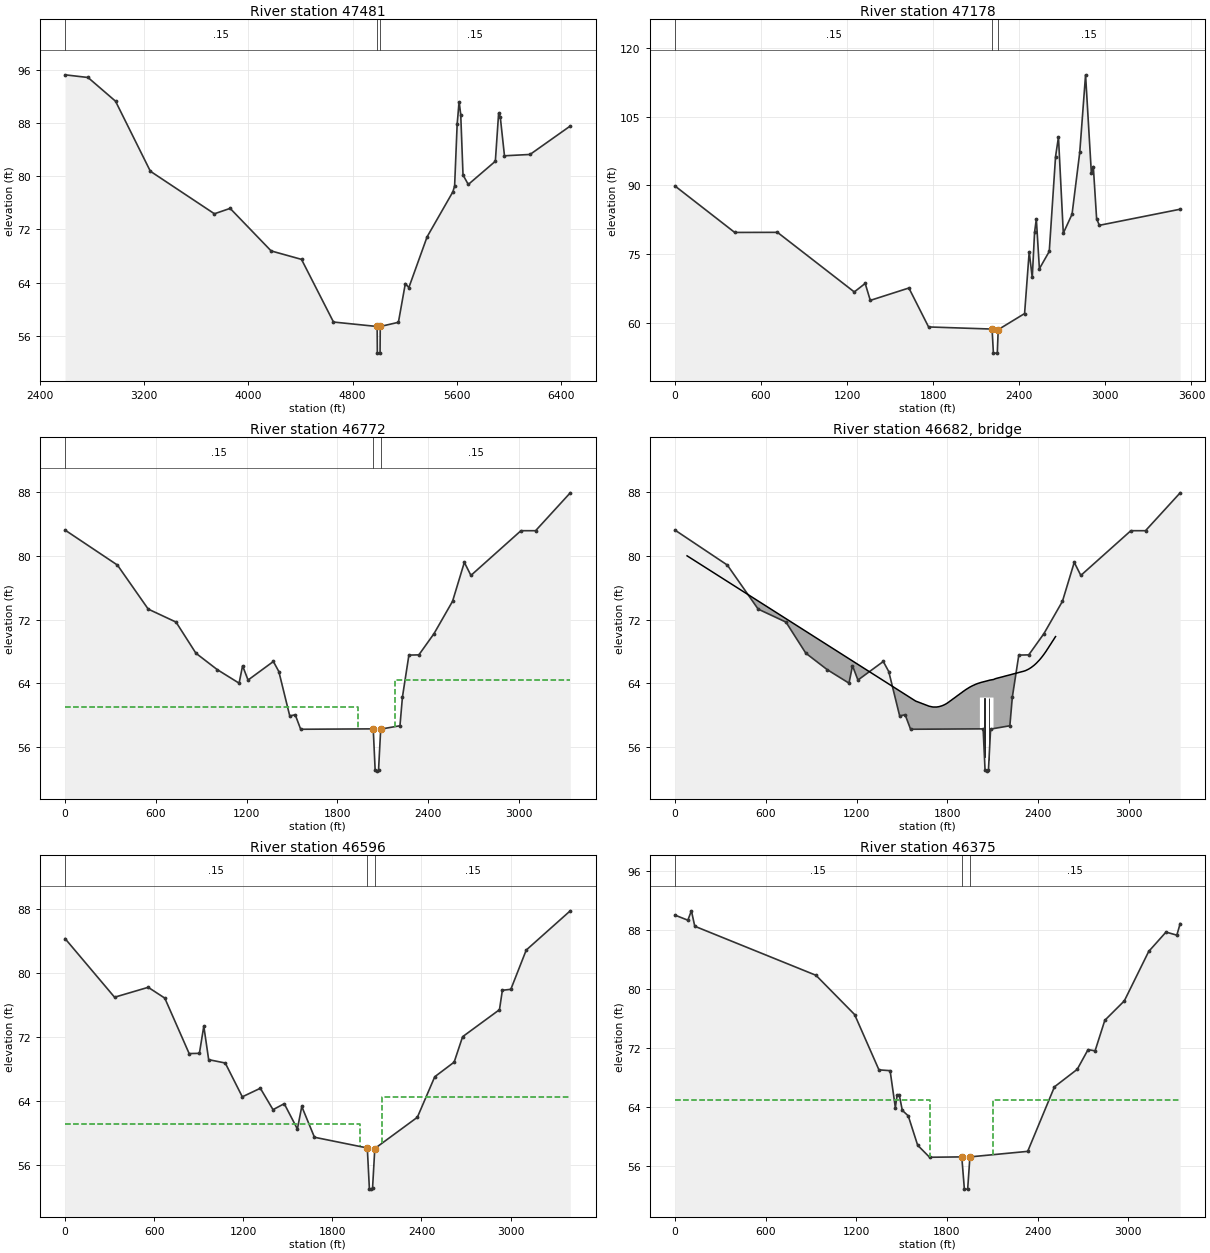
Type RM Length L Ch R = 1 ,47481   ,345.4,302.3,176.6
BEGIN DESCRIPTION:
Reedy Creek XS 39.0
END DESCRIPTION:
XS GIS Cut Line= 4
      2513852.66       828160.78      2511853.52       828232.61
      2511314.83       828460.06      2510057.84       828160.78
#Sta/Elev= 30
  2592.8   95.23    2769   94.83  2980.2   91.27  3247.5   80.75  3739.1   74.36
  3859.8   75.17  4174.5   68.78  4407.6   67.51    4653    58.1  4988.1   57.43
  4989.6   53.43  5010.4   53.43  5011.9   57.43  5151.3   58.06  5204.4   63.88
  5231.3   63.27  5371.5    70.9  5569.6   77.67  5582.7   78.56  5602.2   87.85
  5617.4   91.17  5629.6   89.26  5647.1   80.19  5687.5   78.76  5895.2   82.25
  5920.3   89.45  5932.8   88.94  5965.3   83.07  6161.6   83.27  6470.1   87.54
#Mann= 3 ,-1,0
  2592.8     .15       0  4988.1     .05       0  5011.9     .15       0
Bank Sta=4988.1,5011.9
XS Rating Curve= 0 ,0
Exp/Cntr=0.3,0.1

Type RM Length L Ch R = 1 ,47178   ,266.8,406.4,482.3
XS GIS Cut Line= 4
 2513535.9266087827956.3307230822511804.34717864827928.402022597
2511036.10972626 828251.782405932510106.39474182828029.145558214
#Sta/Elev= 30
       0   89.88   416.5   79.71   714.4   79.73  1249.9   66.69    1326   68.55
  1361.4   64.84  1630.5   67.55  1767.8   59.03  2210.458.56383  2219.6    53.3
 2246.77    53.3  2253.1 58.4404    2437   61.96  2469.1   75.48  2490.4   69.85
  2506.6   79.72  2518.8   82.66  2540.2   71.77    2609   75.56  2652.8    96.3
  2673.1  100.58  2706.8   79.54  2767.8    83.7  2821.5   97.25    2862   114.2
  2902.5   92.64    2916   94.13    2939    82.7  2958.2   81.27  3521.3   84.79
#Mann= 3 ,0,0
       0     .15       0  2210.4     .05       0  2253.1     .15       0
Bank Sta=2210.4,2253.1
XS Rating Curve= 0 ,0
Exp/Cntr(USF)=0,0
Exp/Cntr=0.5,0.3

Type RM Length L Ch R = 1 ,46772   ,179.4,175.7,167
XS GIS Cut Line= 4
 2513199.7504981827808.9292448992511801.02283972827767.550579636
2510875.60271857827770.0216672842509879.68710229827959.905697057
#Sta/Elev= 30
       0   83.23  346.15   78.84  549.63   73.32  733.43   71.69  864.71   67.79
 1005.83   65.73 1150.24   64.03 1173.22   66.21 1209.32   64.42  1376.7   66.75
  1412.8   65.49 1484.97   59.92 1521.06   60.07 1557.15   58.25 2036.63    58.3
 2049.35    53.1  2060.2      53 2071.63    53.1    2086   58.27 2213.27   58.69
 2229.67   62.29 2272.32   67.55 2338.17   67.58 2438.21   70.24 2560.82    74.3
 2638.74   79.18 2682.16   77.54 3012.79   83.15 3109.64   83.15 3338.62    87.9
#Mann= 3 ,0,0
       0     .15       0 2036.63     .05       0    2086     .15       0
#XS Ineff= 2 , 0
          1936.7   61.04  2183.7           64.49
Permanent Ineff=
       F       F
Bank Sta=2036.63,2086
XS Rating Curve= 0 ,0
Exp/Cntr(USF)=0,0
Exp/Cntr=0.5,0.3

Type RM Length L Ch R = 3 ,46682   ,,,
Node Name=Grady Rd Bridge
Bridge Culvert-0,0,0,0, 0
Deck Dist Width WeirC Skew NumUp NumDn MinLoCord MaxHiCord MaxSubmerge Is_Ogee
78.5,32.25,2.6,0, 81, 82, , , 0.98, 0, 2,2,,
      80  1590.2  1599.2  1603.2  1610.2  1614.2  1621.2  1625.2  1632.2  1643.2
  1650.2  1654.2  1661.2  1665.2  1675.2  1680.2  1702.2  1707.2  1729.2  1746.2
  1758.2  1761.2  1773.2  1787.2  1796.2  1810.2  1813.2  1828.2  1831.2  1851.2
  1869.2  1874.2  1887.2  1892.2  1905.2  1913.2  1920.2  1948.2  1967.2  1977.2
  1987.2  2002.2  2013.2 2015.19  2015.2  2015.2  2026.2  2067.2  2080.2  2105.2
  2105.2 2105.21  2117.2  2130.2  2167.2  2180.2  2217.2  2230.2  2267.2  2280.2
  2303.2  2316.2  2337.2  2356.2  2359.2  2371.2  2380.2  2389.2  2408.2  2417.2
  2428.2  2439.2  2453.2  2463.2  2464.2  2479.2  2480.2  2496.2  2497.2  2513.2
  2515.2
      80   61.79   61.72    61.7   61.64   61.62   61.56   61.54   61.48   61.41
   61.35   61.33   61.27   61.25   61.17   61.14   61.05   61.04   61.04   61.09
   61.16   61.17   61.26   61.39   61.49   61.67   61.72   61.92   61.97   62.24
    62.5   62.56   62.75   62.81      63    63.1    63.2   63.53   63.72    63.8
   63.89      64   64.06   64.08   64.08   64.08   64.14   64.34   64.41   64.49
   64.49   64.49   64.59   64.66   64.84   64.91   65.09   65.16   65.34   65.41
   65.52    65.6   65.79   66.02   66.07   66.24   66.39   66.55   66.93   67.13
   67.39   67.67   68.05   68.35   68.37   68.82   68.84   69.32   69.34   69.82
   69.87
                                                                                
                                                                                
                                                                                
                                                                                
                                           62.23   62.23   62.23   62.23   62.23
                                                                                
                                                                                
                                                                                
        
      80  1590.2  1599.2  1603.2  1610.2  1614.2  1621.2  1625.2  1632.2  1643.2
  1650.2  1654.2  1661.2  1665.2  1675.2  1680.2  1702.2  1707.2  1729.2  1746.2
  1758.2  1761.2  1773.2  1787.2  1796.2  1810.2  1813.2  1828.2  1831.2  1851.2
  1869.2  1874.2  1887.2  1892.2  1905.2  1913.2  1920.2  1948.2  1967.2  1977.2
  1987.2  2002.2  2013.2 2015.19  2015.2  2015.2  2026.2  2067.2  2080.2  2105.2
  2105.2 2105.21  2117.2  2130.2  2167.2  2180.2  2217.2  2230.2  2267.2  2280.2
  2303.2  2316.2  2337.2  2356.2  2359.2  2371.2  2380.2  2389.2  2408.2  2417.2
  2428.2  2439.2  2453.2  2463.2  2464.2  2479.2  2480.2  2496.2  2497.2  2513.2
  2515.2    3100
      80   61.79   61.72    61.7   61.64   61.62   61.56   61.54   61.48   61.41
   61.35   61.33   61.27   61.25   61.17   61.14   61.05   61.04   61.04   61.09
   61.16   61.17   61.26   61.39   61.49   61.67   61.72   61.92   61.97   62.24
    62.5   62.56   62.75   62.81      63    63.1    63.2   63.53   63.72    63.8
   63.89      64   64.06   64.08   64.08   64.08   64.14   64.34   64.41   64.49
   64.49   64.49   64.59   64.66   64.84   64.91   65.09   65.16   65.34   65.41
   65.52    65.6   65.79   66.02   66.07   66.24   66.39   66.55   66.93   67.13
   67.39   67.67   68.05   68.35   68.37   68.82   68.84   69.32   69.34   69.82
   69.87    82.6
                                                                                
                                                                                
                                                                                
                                                                                
                                           62.23   62.23   62.23   62.23   62.23
                                                                                
                                                                                
                                                                                
                
Pier Skew, UpSta & Num, DnSta & Num=  ,2045.2, 2 ,2045.2, 2 , 0 , 0 , 0 ,,
       2       2
       0      63
       2       2
       0      63
Pier Skew, UpSta & Num, DnSta & Num=  ,2075.2, 2 ,2075.2, 2 , 0 , 0 , 0 ,,
       2       2
       0      63
       2       2
       0      63
Abutment Skew #Up #Dn= , 3 , 3
  2015.2  2017.2  2037.2
    60.6    60.6    50.6
  2015.2  2017.2  2037.2
    60.6    60.6    50.6
Abutment Skew #Up #Dn= , 3 , 3
  2083.2  2103.2  2105.2
    50.6    60.6    60.6
  2083.2  2103.2  2105.2
    50.6    60.6    60.6
BR Coef=-1 ,-1 ,-1 ,0.9, 0 ,,,0.8,0,1.2,0,
WSPro=,,,, 1 ,,,, 0 ,,,, 0 ,,,,-1 ,-1 ,-1 , 0 , 0 , 0 , 0 , 0
BC Design=,, 0 ,, 0 ,,,,,,
BC HTab HWMax=70
BC HTab TWMax=70
BC Use User HTab Curves=0
BC User HTab FreeFlow(D)= 0

Type RM Length L Ch R = 1 ,46596   ,383.8,221.6,240.9
XS GIS Cut Line= 4
2513209.94240113827637.9214300222511620.24621303827581.322339733
2510862.31056917827601.0089798342509830.54002415827809.777424141
#Sta/Elev= 30
       0   84.29   333.4   76.95   559.9   78.19   671.5   76.84   835.7    69.9
   904.6   69.93   934.2   73.33     967   69.14  1078.6   68.72  1193.5   64.49
    1315   65.56  1400.3   62.88  1475.8   63.63  1564.4   60.46  1593.9   63.28
  1679.3   59.43 2035.12   58.09 2049.13   52.99  2059.4   52.94 2070.35   53.02
 2085.65   58.02  2372.2   61.93  2489.3      67  2619.9   68.83  2676.8   72.01
    2925   75.39  2944.6   77.82  3001.5   77.94  3105.2   82.85  3401.6   87.76
#Mann= 3 ,0,0
       0     .15       0 2035.12     .05       0 2085.65     .15       0
#XS Ineff= 2 , 0
          1983.1   61.04  2137.3           64.49
Permanent Ineff=
       F       F
Bank Sta=2035.12,2085.65
XS Rating Curve= 0 ,0
Exp/Cntr(USF)=0,0
Exp/Cntr=0.5,0.3

Type RM Length L Ch R = 1 ,46375   ,901.7,929.5,715.4
BEGIN DESCRIPTION:
Reedy Creek XS 38.0
END DESCRIPTION:
XS GIS Cut Line= 5
      2512691.68       826394.382511570.51752009827369.069651817
      2511435.84       827373.07      2510699.64       827373.07
2509795.84098941827770.546208584
#Sta/Elev= 30
       0   90.06    85.2   89.37     109   90.64   131.1   88.55   933.4    81.9
  1189.1   76.58  1350.2   69.08  1424.1   68.97  1458.8   63.97  1470.6   65.67
  1484.5   65.71  1504.8   63.59  1544.2   62.84  1606.5   58.86  1685.3   57.23
  1898.5   57.28  1915.7   52.91 1937.44   52.91  1952.3   57.28  2334.8   58.03
    2512   66.78  2662.5   69.15  2734.2   71.82  2780.8   71.66  2845.3    75.8
  2974.3   78.43  3135.6   85.13  3250.3   87.76    3322   87.34  3343.9   88.91
#Mann= 3 ,0,0
       0     .15       0  1898.5     .05       0  1952.3     .15       0
#XS Ineff= 2 , 0
         1690.97      65  2106.2              65
Permanent Ineff=
       F       F
Bank Sta=1898.5,1952.3
XS Rating Curve= 0 ,0
Exp/Cntr=0.5,0.3

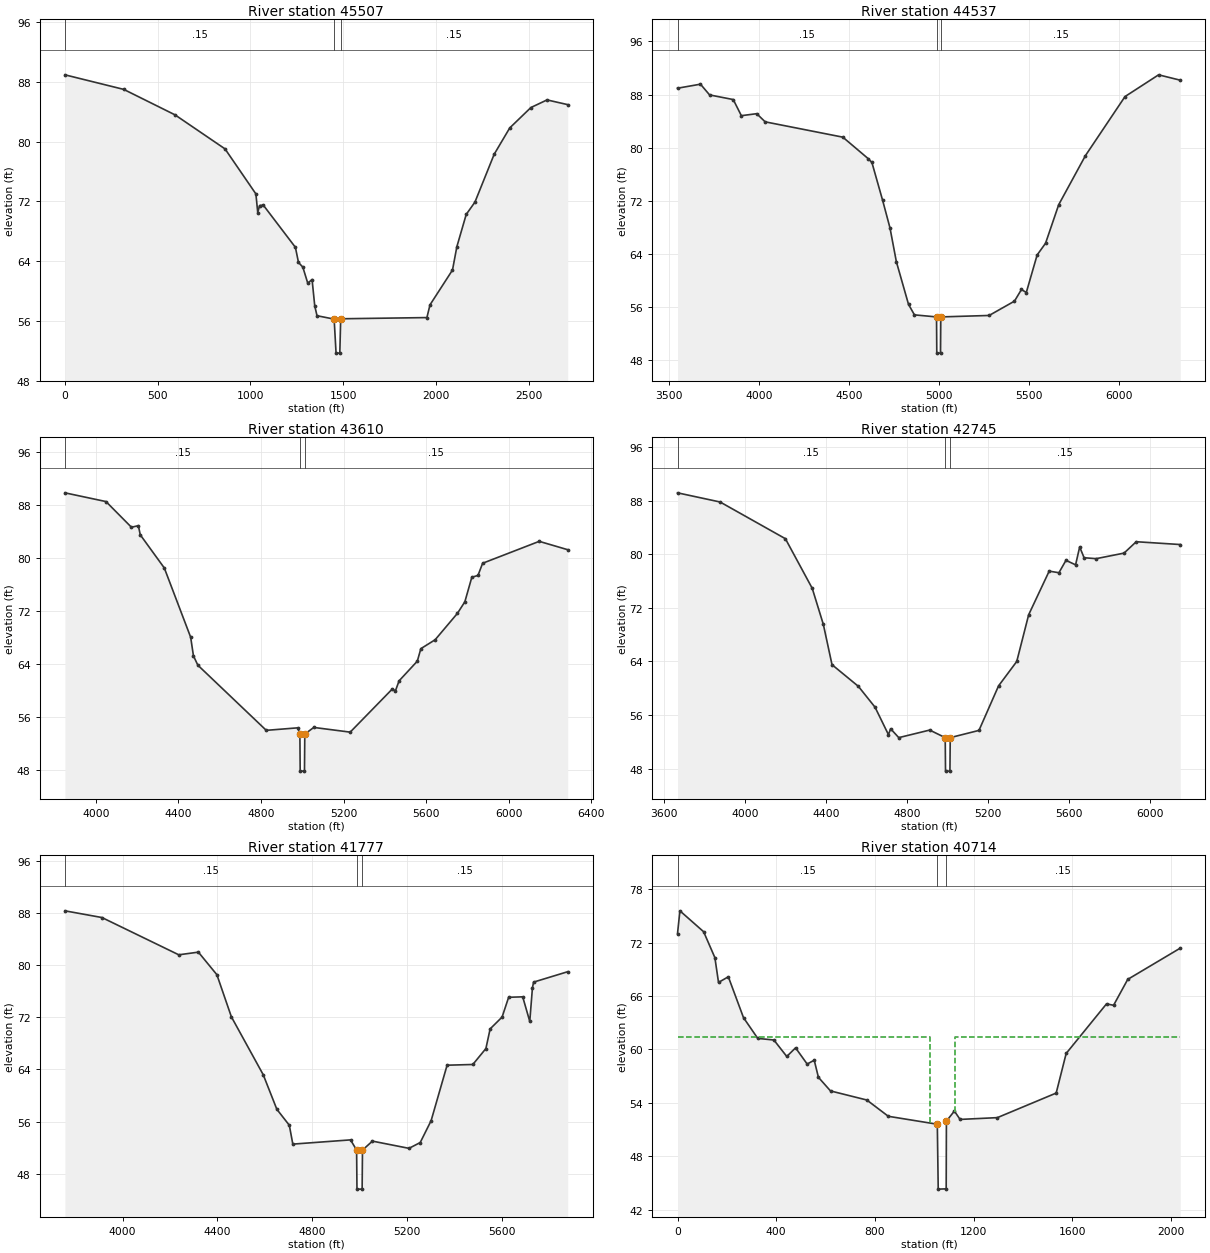
Type RM Length L Ch R = 1 ,45507   ,1071.1,970.3,886.3
BEGIN DESCRIPTION:
Reedy Creek XS 37.0
END DESCRIPTION:
XS GIS Cut Line= 4
 2512431.6558785826285.056985618 2511068.4751914826516.749847983
2510326.06921577826688.192349599 2509772.6358785826803.719364245
#Sta/Elev= 30
       0   88.95     317      87   593.4   83.59     863   79.03  1029.4      73
  1039.3   70.51  1049.3   71.44  1069.3    71.5  1242.3   65.85    1259   63.82
  1282.3    63.2  1308.9   61.05  1332.2   61.54  1346.6      58  1358.8   56.69
1451.16556.23442 1461.43   51.69 1481.69   51.68  1486.5   56.28  1951.1   56.44
  1967.9   58.15  2089.1   62.81  2112.7   65.94  2163.1   70.26    2210    71.9
  2313.9   78.32  2397.7   81.84  2511.7   84.57  2598.7   85.59    2710   84.96
#Mann= 3 ,0,0
       0     .15       01451.165     .05       0  1486.5     .15       0
Bank Sta=1451.165,1486.5
XS Rating Curve= 0 ,0
Exp/Cntr=0.3,0.1

Type RM Length L Ch R = 1 ,44537   ,701.7,926.5,1098.4
BEGIN DESCRIPTION:
Reedy Creek XS 36.0
END DESCRIPTION:
XS GIS Cut Line= 2
      2512076.75       825043.22      2509504.37       826134.53
#Sta/Elev= 30
  3548.6   88.95  3676.2   89.56  3726.8   87.94  3858.3   87.24  3903.4   84.81
  3988.7   85.11  4035.8   83.88  4467.4   81.57  4607.9   78.34    4629   77.75
  4688.8   72.02  4729.5   67.88    4765   62.78  4832.5   56.35  4865.3   54.77
  4988.1   54.46  4989.6      49  5010.4      49  5011.9   54.46  5280.6   54.68
  5421.4   56.84  5460.3    58.6  5487.1   58.14  5547.3    63.8  5594.1   65.57
  5667.3   71.39  5816.1    78.8  6035.7   87.69  6222.4   90.97  6342.9   90.16
#Mann= 3 ,-1,0
  3548.6     .15       0  4988.1     .05       0  5011.9     .15       0
Bank Sta=4988.1,5011.9
XS Rating Curve= 0 ,0
Exp/Cntr=0.3,0.1

Type RM Length L Ch R = 1 ,43610   ,815.2,865.4,800.2
BEGIN DESCRIPTION:
Reedy Creek XS 35.0
END DESCRIPTION:
XS GIS Cut Line= 2
      2511782.25       824774.71      2509348.51       824679.44
#Sta/Elev= 30
  3849.9   89.84  4048.8   88.52  4172.1   84.64  4205.7   84.88  4214.8    83.5
  4331.3   78.49    4459   68.03  4472.5   65.21  4493.9    63.8  4825.3   53.96
  4977.7   54.34  4988.1   53.39  4989.6    47.8  5010.4    47.8  5011.9   53.39
  5055.4    54.4  5231.9   53.69  5436.6   60.23  5450.6   59.89  5468.7   61.44
    5557   64.41  5574.2    66.3  5643.6   67.65  5751.3   71.63  5787.3   73.38
  5821.1   77.09  5850.9   77.36  5873.4    79.2  6147.6   82.51  6285.5   81.25
#Mann= 3 ,-1,0
  3849.9     .15       0  4988.1     .05       0  5011.9     .15       0
Bank Sta=4988.1,5011.9
XS Rating Curve= 0 ,0
Exp/Cntr=0.3,0.1

Type RM Length L Ch R = 1 ,42745   ,1015.9,968.1,1031.5
BEGIN DESCRIPTION:
Reedy Creek XS 34.0
END DESCRIPTION:
XS GIS Cut Line= 4
      2511764.94       824445.57      2510959.47       823865.29
      2510431.14       823865.29      2509495.72       824090.48
#Sta/Elev= 30
  3665.4   89.18  3875.8   87.81  4198.2   82.33  4330.8   74.92  4385.6   69.54
  4428.5   63.52  4558.6   60.29  4641.1   57.17  4707.3   53.07  4717.9   53.96
  4758.2   52.63  4910.9   53.76  4987.6   52.63  4989.1   47.63  5010.9   47.63
  5012.4   52.63  5154.3   53.71  5251.1   60.36  5340.9      64  5399.8   70.98
  5501.1   77.49  5549.2   77.25    5584    79.1  5631.5   78.43  5651.7    81.1
  5673.5   79.49  5733.1   79.35  5870.8   80.18  5931.1   81.88  6148.6   81.46
#Mann= 3 ,-1,0
  3665.4     .15       0  4987.6     .05       0  5012.4     .15       0
Bank Sta=4987.6,5012.4
XS Rating Curve= 0 ,0
Exp/Cntr=0.3,0.1

Type RM Length L Ch R = 1 ,41777   ,1216.4,937.5,420.5
BEGIN DESCRIPTION:
Reedy Creek XS 33.0
END DESCRIPTION:
XS GIS Cut Line= 2
      2511990.18       822938.55      2509868.12       822895.24
#Sta/Elev= 30
  3756.2   88.39  3912.4   87.36  4236.8   81.63  4319.6   82.04  4397.7   78.57
    4459   72.09  4593.3    63.2  4650.9   57.88  4703.5   55.43  4718.3   52.53
    4962   53.18  4987.6   51.61  4989.1   45.61  5010.9   45.61  5012.4   51.61
  5054.3   52.99  5208.7   51.88  5256.1   52.77  5302.1   56.13  5369.6   64.66
  5478.2   64.77  5533.4   67.22  5551.3   70.24  5601.8   72.06  5629.4    75.1
  5688.8   75.17  5718.6   71.39  5729.8   76.52  5734.6   77.43  5878.7   79.03
#Mann= 3 ,-1,0
  3756.2     .15       0  4987.6     .05       0  5012.4     .15       0
Bank Sta=4987.6,5012.4
XS Rating Curve= 0 ,0
Exp/Cntr=0.5,0.3

Type RM Length L Ch R = 1 ,40714   ,211.8,209.9,251.3
XS GIS Cut Line= 6
2511464.46417665821298.4905823742510912.86469984821651.568221624
2510673.66920778821898.2313974882510555.07701375822059.498374809
2510422.28351883822280.383258906 2510189.0723133822812.969948296
#Sta/Elev= 30
       0   73.01     9.7   75.56   105.9   73.21   151.5    70.3   166.2   67.52
     206   68.15   267.5   63.56   325.3   61.23   390.7   61.05   442.9    59.2
   478.6   60.17   525.6   58.35   554.2   58.78   571.2   56.86   620.2   55.33
   767.4   54.31   854.6   52.48  1053.2   51.59 1056.91    44.3  1089.2   44.33
  1090.1   51.94  1122.4   53.07  1145.5   52.13  1296.6   52.33  1535.1   55.09
  1575.6   59.54  1739.2   65.11  1767.8   64.95  1825.2   67.86  2038.2   71.37
#Mann= 3 ,0,0
       0     .15       0  1053.2     .05       0  1090.1     .15       0
#XS Ineff= 2 , 0
         1021.95   61.37 1123.93           61.37
Permanent Ineff=
       F       F
Bank Sta=1053.2,1090.1
XS Rating Curve= 0 ,0
Exp/Cntr(USF)=0,0
Exp/Cntr=0.5,0.3

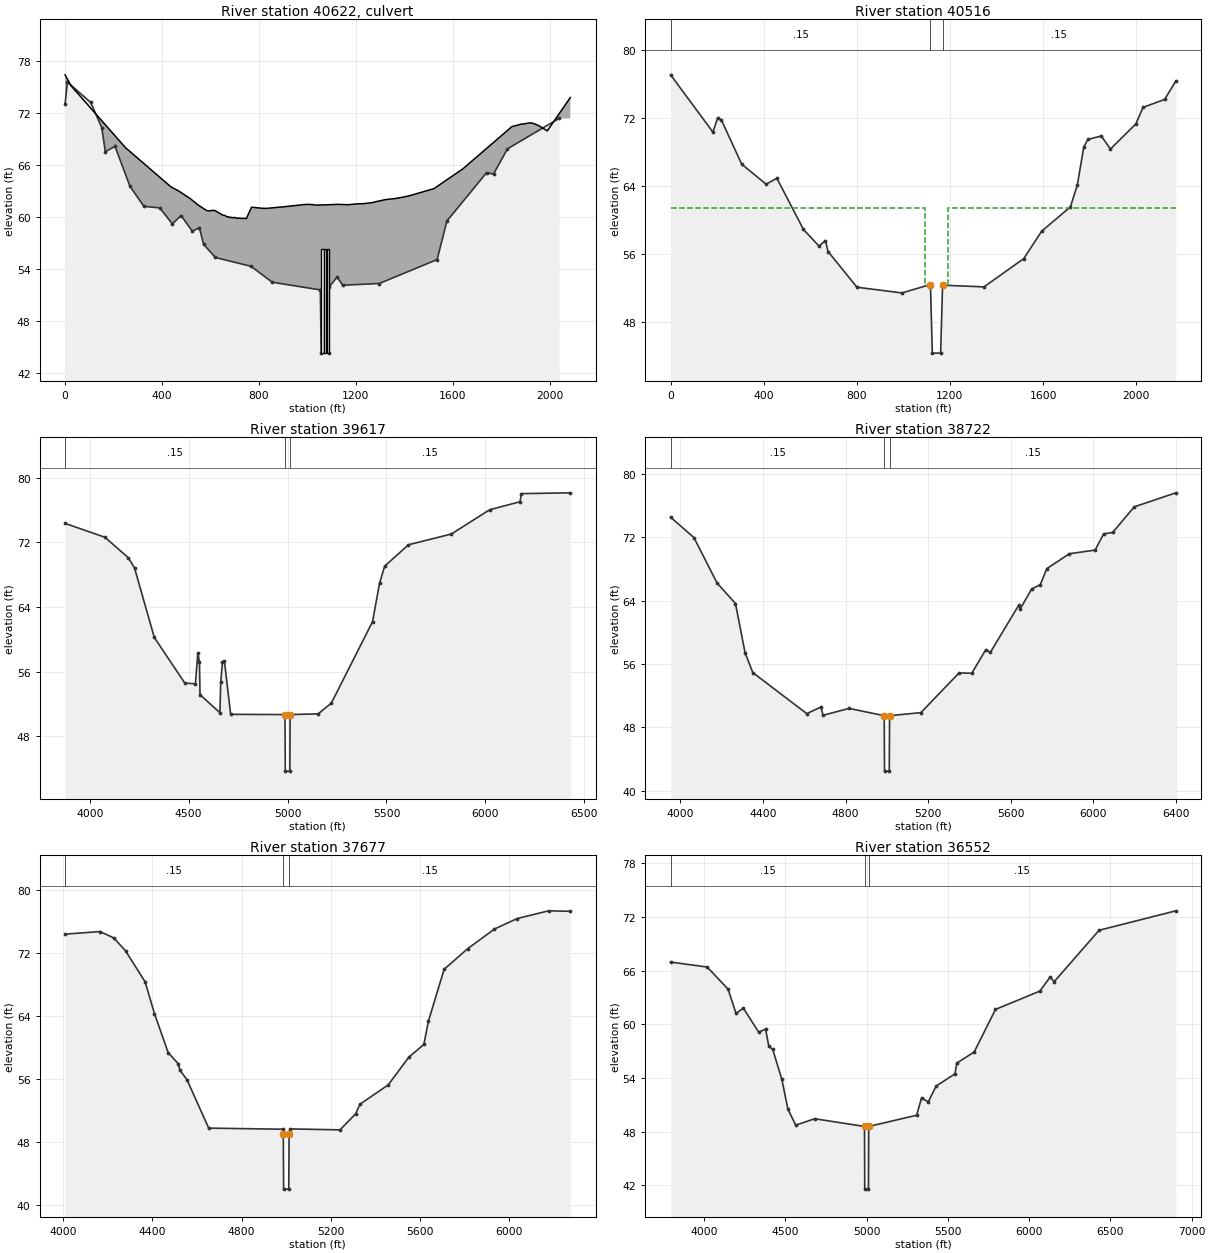
Type RM Length L Ch R = 2 ,40622   ,,,
Node Name=E Hwy 501
Bridge Culvert-0,0,0,0, 0
Deck Dist Width WeirC Skew NumUp NumDn MinLoCord MaxHiCord MaxSubmerge Is_Ogee
35.14436,125,2.6,0, 58, 58, , , 0.98, 0, 2,2,,
       0    24.6   248.6   437.2   468.2   515.9   546.8   582.6   588.4   596.2
   601.6   615.9   645.9   652.7   659.8   666.9   673.8   680.7   687.7   694.5
   701.6   708.8   715.5   731.8     736     748   769.4   808.3   828.3   872.1
   909.5   980.8   996.3    1021  1037.5  1110.8  1120.2  1169.3  1205.2  1230.9
  1265.1  1316.9    1340  1357.8  1399.2  1420.8  1522.5  1641.1  1844.2  1853.6
  1883.2  1893.1  1914.7  1925.3  1938.2  1954.9  1989.5  2084.6
    76.4   75.14   68.02   63.47   63.01   62.14   61.43   60.77   60.72    60.7
   60.74   60.77   60.31   60.19   60.19   60.03   60.04   59.94   59.96   59.91
   59.95   59.84   59.88   59.83   59.85   59.82   61.13   61.02   60.99    61.1
    61.2   61.42   61.46   61.43   61.37   61.44   61.46   61.42   61.52   61.54
   61.65   61.98   62.07   62.11   62.32   62.45   63.28   65.55   70.44    70.5
   70.72   70.74   70.85   70.85   70.73   70.53   69.93   73.78
                                                                                
                                                                                
                                                                                
                                                                                
                                                                                
                                                                
       0    90.6   314.6   503.2   534.2   581.9   612.8   648.6   654.4   662.2
   667.6   681.9   711.9   718.7   725.8   732.9   739.8   746.7   753.7   760.5
   767.6   774.8   781.5   797.8     802     814   835.4   874.3   894.3   938.1
   975.5  1046.8  1062.3    1087  1103.5  1176.8  1186.2  1235.3  1271.2  1296.9
  1331.1  1382.9    1406  1423.8  1465.2  1486.8  1588.5  1707.1  1910.2  1919.6
  1949.2  1959.1  1980.7  1991.3  2004.2  2020.9  2055.5  2150.6
    76.4   75.14   68.02   63.47   63.01   62.14   61.43   60.77   60.72    60.7
   60.74   60.77   60.31   60.19   60.19   60.03   60.04   59.94   59.96   59.91
   59.95   59.84   59.88   59.83   59.85   59.82   61.13   61.02   60.99    61.1
    61.2   61.42   61.46   61.43   61.37   61.44   61.46   61.42   61.52   61.54
   61.65   61.98   62.07   62.11   62.32   62.45   63.28   65.55   70.44    70.5
   70.72   70.74   70.85   70.85   70.73   70.53   69.93   73.78
                                                                                
                                                                                
                                                                                
                                                                                
                                                                                
                                                                
BR Coef=-1 , 0 , 0 ,, 0 ,,,0.8,0,,0,
WSPro=,,,, 1 ,,,, 0 ,,,, 0 ,,,,-1 ,-1 ,-1 , 0 , 0 , 0 , 0 , 0
Multiple Barrel Culv=2,12,10,125,0.012,0.4,1,8,1,44.33,44.31, 3,Culvert #1  , 0 ,36.5
 1062.09 1131.33 1072.94 1142.18 1083.79 1153.03
BC Culvert Barrel=1,Barrel1,0
BC Culvert Barrel=2,Barrel2,0
BC Culvert Barrel=3,Barrel3,0
Culvert Bottom n=0.012
BC Design=,, 0 ,, 0 ,,,,,,
BC Use User HTab Curves=0
BC User HTab FreeFlow(D)= 0

Type RM Length L Ch R = 1 ,40516   ,973,937.4,949.3
XS GIS Cut Line= 6
2511363.71132657821130.6975956672510803.37279908821472.763156935
2510713.57808985 821551.421353592510404.65907961821896.389186547
2510321.84894302822015.4728718372509995.67939475 822731.10899758
#Sta/Elev= 30
       0   77.03   181.6    70.3   202.9   72.01   218.3   71.71   305.7   66.51
   410.5   64.17   456.6   64.86   570.6   58.85   637.5   56.89   665.2   57.54
   676.5   56.25   800.7   52.05   993.9   51.38  1116.4   52.37 1124.31    44.3
 1160.05    44.3 1168.43   52.29  1346.4   52.09  1517.3   55.42  1593.8   58.63
  1717.6    61.5  1747.4   64.08  1775.1   68.56    1793   69.43  1850.3   69.84
  1889.6    68.3  1999.2   71.27  2029.1   73.19  2122.2   74.14  2170.6    76.3
#Mann= 3 ,0,0
       0     .15       0  1116.4     .05       0 1168.43     .15       0
#XS Ineff= 2 , 0
         1093.16   61.37 1191.19           61.37
Permanent Ineff=
       F       F
Bank Sta=1116.4,1168.43
XS Rating Curve= 0 ,0
Exp/Cntr(USF)=0,0
Exp/Cntr=0.5,0.3

Type RM Length L Ch R = 1 ,39617   ,935.3,895.5,881.4
BEGIN DESCRIPTION:
Reedy Creek XS 31.0
END DESCRIPTION:
XS GIS Cut Line= 2
      2510540.01       820232.47      2508975.24       822251.87
#Sta/Elev= 30
  3874.9   74.36  4076.3   72.64  4194.7   70.11  4226.4   68.82  4326.1   60.24
  4480.1    54.6  4534.1   54.49  4546.1   58.33  4554.5   57.24  4557.3   53.15
    4658   50.92    4662   54.71  4670.8   57.15  4680.4   57.35  4712.3   50.72
    4987   50.69  4988.5   43.69  5011.5   43.69    5013   50.69  5154.7   50.78
  5221.2    52.1  5429.8    62.2    5465   66.95  5491.2   69.07  5611.4   71.71
    5828   73.04  6021.5   76.04  6175.5   77.04  6182.2   78.04  6429.6   78.14
#Mann= 3 ,-1,0
  3874.9     .15       0    4987     .05       0    5013     .15       0
Bank Sta=4987,5013
XS Rating Curve= 0 ,0
Exp/Cntr=0.3,0.1

Type RM Length L Ch R = 1 ,38722   ,1226.8,1044.1,721.9
BEGIN DESCRIPTION:
Reedy Creek XS 30.0
END DESCRIPTION:
XS GIS Cut Line= 4
      2509260.72       819566.44      2509408.73       820147.93
      2509059.84       820739.98      2508277.46       821596.37
#Sta/Elev= 30
  3952.4   74.53  4065.4   71.96  4177.2   66.23  4266.6   63.63  4313.2   57.41
  4350.6   54.91    4612   49.73  4680.1   50.56  4690.7   49.52  4816.6   50.39
    4987   49.47  4988.5   42.47  5011.5   42.47    5013   49.47  5164.9   49.86
  5349.4   54.87  5411.3   54.83  5478.9    57.8  5500.9   57.45  5639.6   63.47
  5644.5    62.9  5700.8   65.45  5743.3   66.03  5774.5   68.04    5884   69.92
  6008.4   70.38  6049.7   72.42  6093.6   72.61  6198.1   75.84  6399.6   77.61
#Mann= 3 ,-1,0
  3952.4     .15       0    4987     .05       0    5013     .15       0
Bank Sta=4987,5013
XS Rating Curve= 0 ,0
Exp/Cntr=0.3,0.1

Type RM Length L Ch R = 1 ,37677   ,1108.8,1125.4,1120.5
BEGIN DESCRIPTION:
Reedy Creek XS 29.0
END DESCRIPTION:
XS GIS Cut Line= 2
      2508161.18       819386.75      2508214.05       821649.24
#Sta/Elev= 30
  4009.5   74.37  4166.1    74.7  4227.9   73.89  4280.3   72.26  4368.1   68.32
    4410   64.29  4471.5   59.33  4516.6   57.93    4523   57.17  4556.2   55.87
  4652.9   49.76  4983.8   49.62    4987   49.02  4988.5   42.02  5011.5   42.02
    5013   49.02  5017.5   49.66  5241.2   49.54  5311.1   51.58  5330.2   52.79
  5457.1   55.25  5549.1   58.75  5616.6   60.38  5637.2   63.35  5707.5   69.91
  5812.1   72.51  5932.9   75.02  6034.6   76.35  6175.4   77.33  6272.6   77.27
#Mann= 3 ,-1,0
  4009.5     .15       0    4987     .05       0    5013     .15       0
Bank Sta=4987,5013
XS Rating Curve= 0 ,0
Exp/Cntr=0.3,0.1

Type RM Length L Ch R = 1 ,36552   ,,,
BEGIN DESCRIPTION:
Reedy Creek XS 28.0
END DESCRIPTION:
XS GIS Cut Line= 2
      2507061.65       819164.66      2507135.66       822272.98
#Sta/Elev= 30
  3793.8   66.95  4019.1   66.39  4147.6   63.92  4196.2   61.21  4241.4    61.8
    4336   59.12    4378   59.46  4398.5   57.52  4422.1    57.2  4478.3   53.85
  4515.7   50.52  4563.8   48.73  4680.4   49.45    4987   48.59  4988.5   41.59
  5011.5   41.59    5013   48.59  5307.7   49.84    5338   51.77  5379.3   51.34
  5427.8    53.1  5543.9   54.47  5554.8   55.66  5661.8    56.9  5793.1   61.66
  6065.6    63.7  6129.8   65.28  6154.4   64.76  6430.6    70.5    6903   72.67
#Mann= 3 ,-1,0
  3793.8     .15       0    4987     .05       0    5013     .15       0
Bank Sta=4987,5013
XS Rating Curve= 0 ,0
Exp/Cntr=0.3,0.1
LCMann Table=0

Chan Stop Cuts=-1
Use User Specified Reach Order=0
Composite Channel Slope=5

--- ReedyCreek.g01 (geometry) ---

Geom Title=Existing Conditions
Program Version=6.60

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
River Reach=Reedy Creek     ,Reach-1