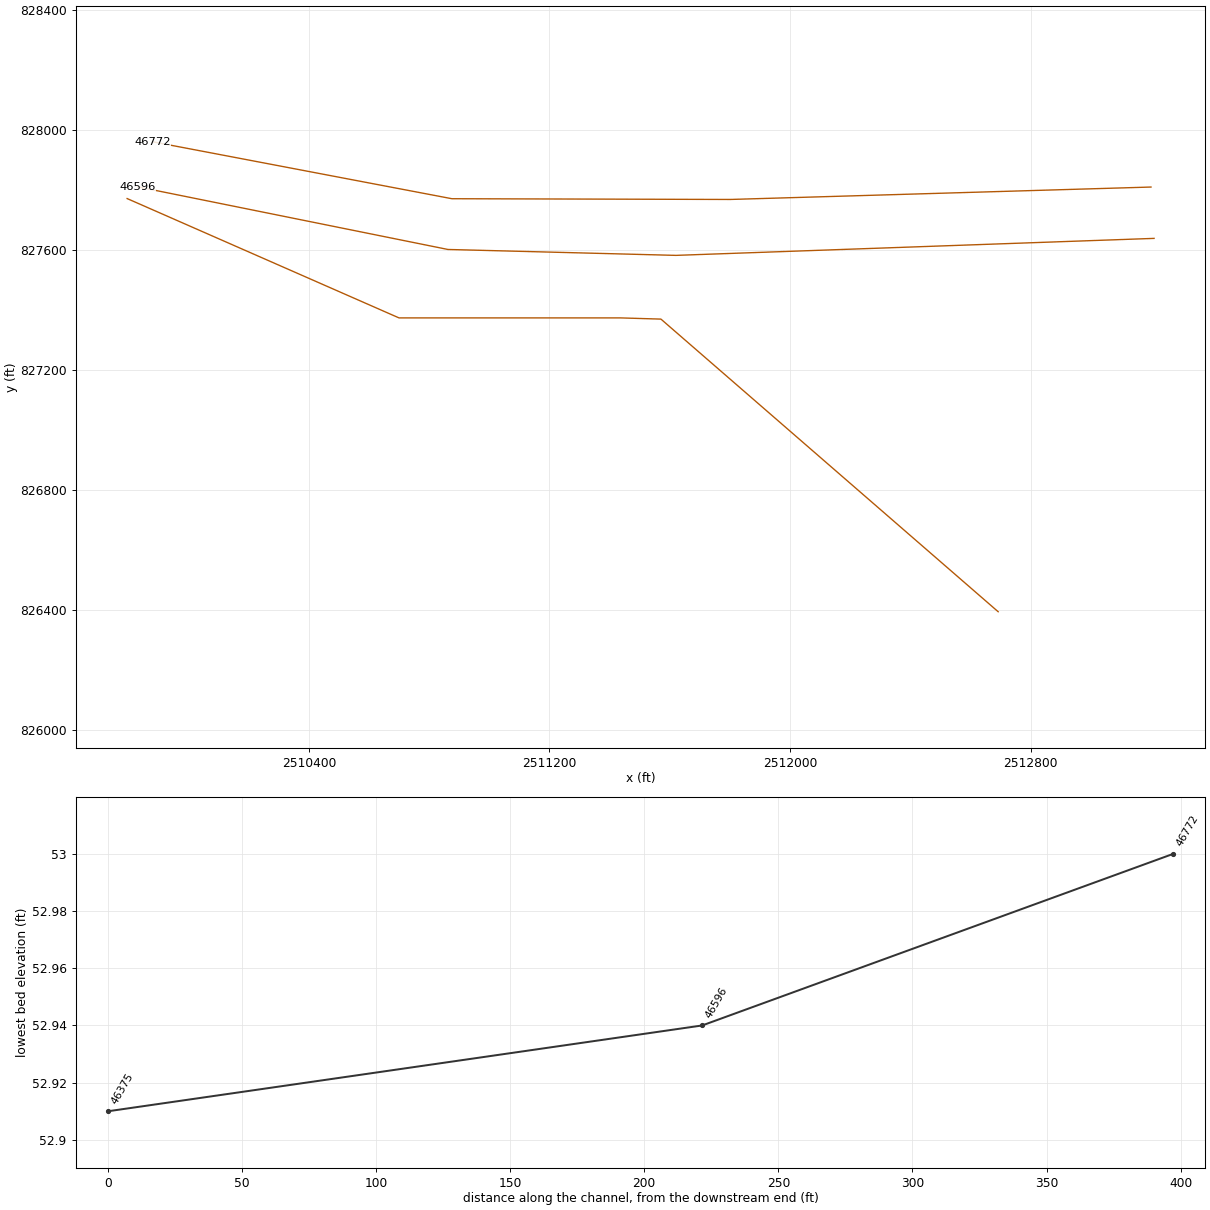
HEC-RAS study ReedyCreek.prj: S-34-32 over Reedy Creek

--- ReedyCreek.g01 (geometry) --- (continued)

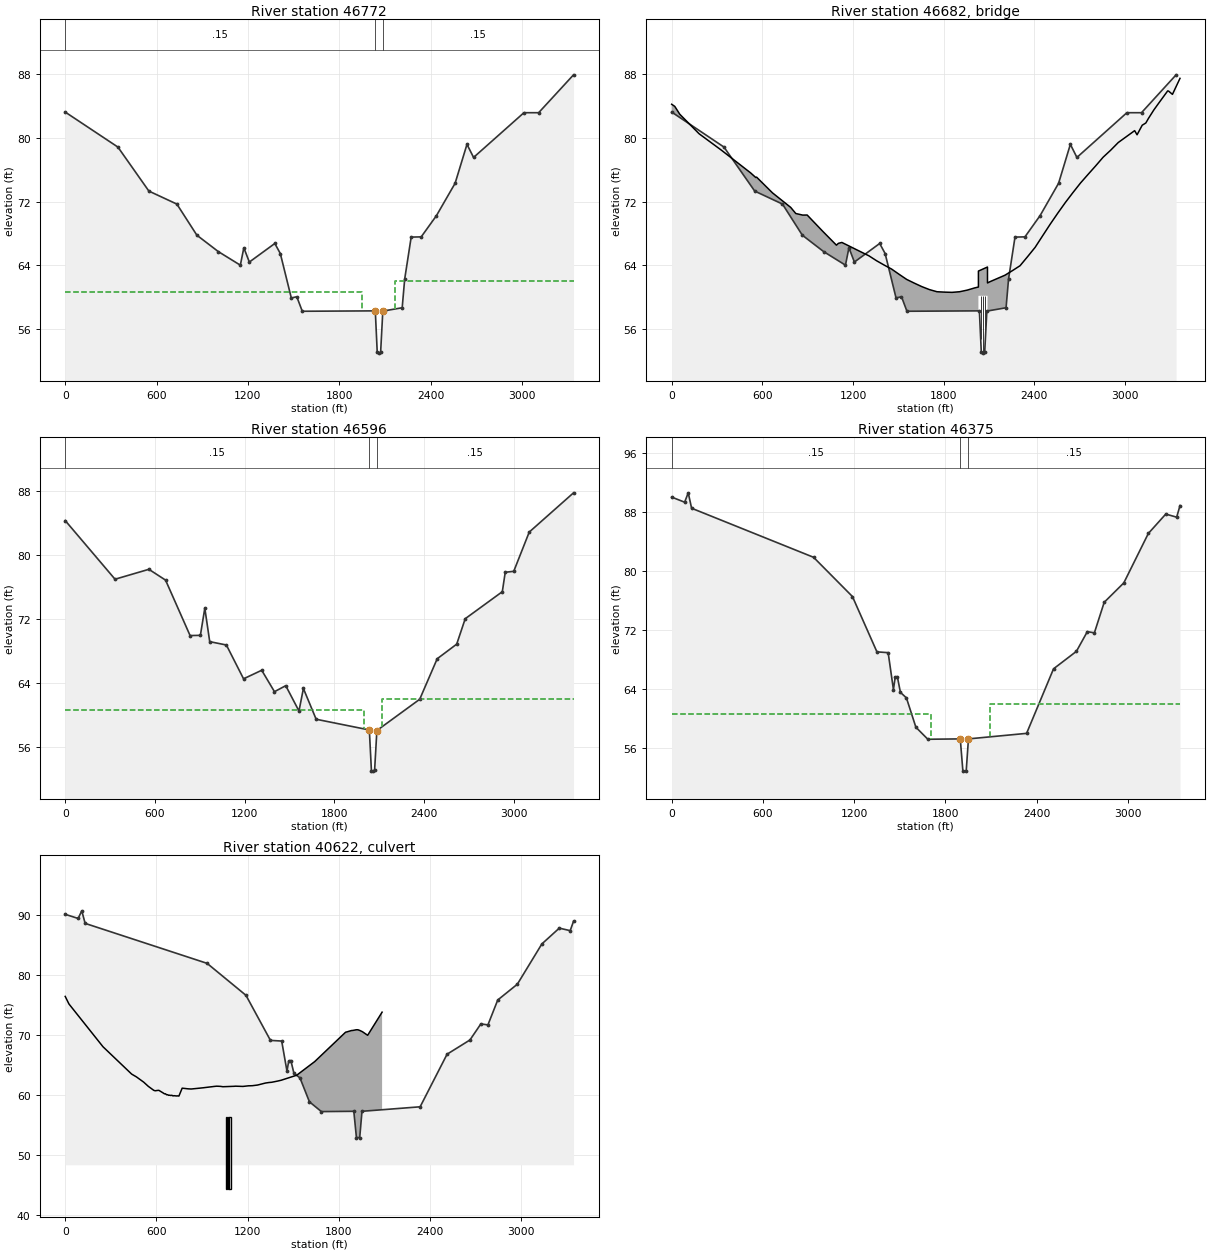
Type RM Length L Ch R = 1 ,46772   ,179.4,175.7,167
XS GIS Cut Line= 4
 2513199.7504981827808.9292448992511801.02283972827767.550579636
2510875.60271857827770.0216672842509879.68710229827959.905697057
#Sta/Elev= 30
       0   83.23  346.15   78.84  549.63   73.32  733.43   71.69  864.71   67.79
 1005.83   65.73 1150.24   64.03 1173.22   66.21 1209.32   64.42  1376.7   66.75
  1412.8   65.49 1484.97   59.92 1521.06   60.07 1557.15   58.25 2036.63    58.3
 2049.35    53.1  2060.2      53 2071.63    53.1    2086   58.27 2213.27   58.69
 2229.67   62.29 2272.32   67.55 2338.17   67.58 2438.21   70.24 2560.82    74.3
 2638.74   79.18 2682.16   77.54 3012.79   83.15 3109.64   83.15 3338.62    87.9
#Mann= 3 ,0,0
       0     .15       0 2036.63     .05       0    2086     .15       0
#XS Ineff= 2 , 0
          1951.7   60.63  2168.7              62
Permanent Ineff=
       F       F
Bank Sta=2036.63,2086
XS Rating Curve= 0 ,0
Exp/Cntr(USF)=0,0
Exp/Cntr=0.5,0.3

Type RM Length L Ch R = 3 ,46682   ,,,
Node Name=Grady Rd Bridge
Bridge Culvert-0,0,0,0, 0
Deck Dist Width WeirC Skew NumUp NumDn MinLoCord MaxHiCord MaxSubmerge Is_Ogee
78.5,33,2.6,0, 65, 65, , , 0.98, 0, 2,2,,
       0    20.6    53.5   181.4   329.1   384.9   522.7   556.2   562.1   667.1
   788.1   821.3   867.3   896.8  1001.8  1090.4  1103.6  1126.5  1305.7  1355.7
  1405.7  1455.7  1505.7  1555.7  1605.7  1655.7  1705.7  1755.7  1805.7  1855.7
  1905.7  1955.7  2005.7  2030.2  2030.2  2090.2  2090.2  2105.7  2205.7  2255.7
  2305.7  2355.7  2405.7  2455.7  2505.7  2555.7  2605.7  2655.7  2705.7  2755.7
  2805.7  2855.7  2905.7  2955.7  3064.3  3080.2  3114.3  3138.2  3154.5    3191
  3224.4  3282.7  3288.8  3314.4  3364.4
   84.21   83.94   82.96   80.51   78.45   77.63    75.6   75.03   75.07    73.1
   71.27   70.51   70.31   70.32   68.24   66.54   66.77   66.88    65.2   64.59
   64.05   63.54   62.88   62.24   61.78   61.34   60.97    60.7   60.65   60.62
    60.7    60.9   61.18   61.29   63.29    63.8    61.8   61.95   62.77   63.35
   63.96    65.1   66.27   67.73   69.18   70.56   71.89   73.13   74.33   75.41
   76.47   77.57   78.45   79.41    80.9   80.38   81.58   81.86    82.4   83.49
   84.37   85.88   85.86   85.45   87.46
                                                                                
                                                                                
                                                                                
                                   60.19   60.19
                                                                                
                                                                                
                                        
       0    20.6    53.5   181.4   329.1   384.9   522.7   556.2   562.1   667.1
   788.1   821.3   867.3   896.8  1001.8  1090.4  1103.6  1126.5  1305.7  1355.7
  1405.7  1455.7  1505.7  1555.7  1605.7  1655.7  1705.7  1755.7  1805.7  1855.7
  1905.7  1955.7  2005.7  2030.2  2030.2  2090.2  2090.2  2105.7  2205.7  2255.7
  2305.7  2355.7  2405.7  2455.7  2505.7  2555.7  2605.7  2655.7  2705.7  2755.7
  2805.7  2855.7  2905.7  2955.7  3064.3  3080.2  3114.3  3138.2  3154.5    3191
  3224.4  3282.7  3288.8  3314.4  3364.4
   84.21   83.94   82.96   80.51   78.45   77.63    75.6   75.03   75.07    73.1
   71.27   70.51   70.31   70.32   68.24   66.54   66.77   66.88    65.2   64.59
   64.05   63.54   62.88   62.24   61.78   61.34   60.97    60.7   60.65   60.62
    60.7    60.9   61.18   61.29   63.29    63.8    61.8   61.95   62.77   63.35
   63.96    65.1   66.27   67.73   69.18   70.56   71.89   73.13   74.33   75.41
   76.47   77.57   78.45   79.41    80.9   80.38   81.58   81.86    82.4   83.49
   84.37   85.88   85.86   85.45   87.46
                                                                                
                                                                                
                                                                                
                                   60.19   60.19
                                                                                
                                                                                
                                        
Pier Skew, UpSta & Num, DnSta & Num=  ,2045.2, 2 ,2045.2, 2 , 0 , 0 , 0 ,,
       1       1
       0      61
       1       1
       0      61
Pier Skew, UpSta & Num, DnSta & Num=  ,2060.2, 2 ,2060.2, 2 , 0 , 0 , 0 ,,
       1       1
       0      61
       1       1
       0      61
Pier Skew, UpSta & Num, DnSta & Num=  ,2075.2, 2 ,2075.2, 2 , 0 , 0 , 0 ,,
       1       1
       0      61
       1       1
       0      61
BR Coef=-1 ,-1 ,-1 ,0.9, 0 ,,,0.8,0,1.2,0,
WSPro=,,,, 1 ,,,, 0 ,,,, 0 ,,,,-1 ,-1 ,-1 , 0 , 0 , 0 , 0 , 0
BC Design=,, 0 ,, 0 ,,,,,,
BC HTab HWMax=70
BC HTab TWMax=70
BC Use User HTab Curves=0
BC User HTab FreeFlow(D)= 0

Type RM Length L Ch R = 1 ,46596   ,383.8,221.6,240.9
XS GIS Cut Line= 4
2513209.94240113827637.9214300222511620.24621303827581.322339733
2510862.31056917827601.0089798342509830.54002415827809.777424141
#Sta/Elev= 30
       0   84.29   333.4   76.95   559.9   78.19   671.5   76.84   835.7    69.9
   904.6   69.93   934.2   73.33     967   69.14  1078.6   68.72  1193.5   64.49
    1315   65.56  1400.3   62.88  1475.8   63.63  1564.4   60.46  1593.9   63.28
  1679.3   59.43 2035.12   58.09 2049.13   52.99  2059.4   52.94 2070.35   53.02
 2085.65   58.02  2372.2   61.93  2489.3      67  2619.9   68.83  2676.8   72.01
    2925   75.39  2944.6   77.82  3001.5   77.94  3105.2   82.85  3401.6   87.76
#Mann= 3 ,0,0
       0     .15       0 2035.12     .05       0 2085.65     .15       0
#XS Ineff= 2 , 0
          1998.1   60.63  2122.3              62
Permanent Ineff=
       F       F
Bank Sta=2035.12,2085.65
XS Rating Curve= 0 ,0
Exp/Cntr(USF)=0,0
Exp/Cntr=0.5,0.3

Type RM Length L Ch R = 1 ,46375   ,901.7,929.5,715.4
BEGIN DESCRIPTION:
Reedy Creek XS 38.0
END DESCRIPTION:
XS GIS Cut Line= 5
      2512691.68       826394.382511570.51752009827369.069651817
      2511435.84       827373.07      2510699.64       827373.07
2509795.84098941827770.546208584
#Sta/Elev= 30
       0   90.06    85.2   89.37     109   90.64   131.1   88.55   933.4    81.9
  1189.1   76.58  1350.2   69.08  1424.1   68.97  1458.8   63.97  1470.6   65.67
  1484.5   65.71  1504.8   63.59  1544.2   62.84  1606.5   58.86  1685.3   57.23
  1898.5   57.28  1915.7   52.91 1937.44   52.91  1952.3   57.28  2334.8   58.03
    2512   66.78  2662.5   69.15  2734.2   71.82  2780.8   71.66  2845.3    75.8
  2974.3   78.43  3135.6   85.13  3250.3   87.76    3322   87.34  3343.9   88.91
#Mann= 3 ,0,0
       0     .15       0  1898.5     .05       0  1952.3     .15       0
#XS Ineff= 2 , 0
         1705.97   60.63  2091.2              62
Permanent Ineff=
       F       F
Bank Sta=1898.5,1952.3
XS Rating Curve= 0 ,0
Exp/Cntr=0.5,0.3

Type RM Length L Ch R = 2 ,40622   ,,,
BEGIN DESCRIPTION:
Three Box Culvert, Structure Length=31.7 ft, Deck Width out-to-out=125 ft, Approaching roadway=77 ft, each barrel-width 10 ft and height 12 ft.
END DESCRIPTION:
Node Name=E Hwy 501
Bridge Culvert-0,0,0,0, 0
Deck Dist Width WeirC Skew NumUp NumDn MinLoCord MaxHiCord MaxSubmerge Is_Ogee
35.14436,125,2.6,0, 58, 58, , , 0.98, 0, 2,2,,
       0    24.6   248.6   437.2   468.2   515.9   546.8   582.6   588.4   596.2
   601.6   615.9   645.9   652.7   659.8   666.9   673.8   680.7   687.7   694.5
   701.6   708.8   715.5   731.8     736     748   769.4   808.3   828.3   872.1
   909.5   980.8   996.3    1021  1037.5  1110.8  1120.2  1169.3  1205.2  1230.9
  1265.1  1316.9    1340  1357.8  1399.2  1420.8  1522.5  1641.1  1844.2  1853.6
  1883.2  1893.1  1914.7  1925.3  1938.2  1954.9  1989.5  2084.6
    76.4   75.14   68.02   63.47   63.01   62.14   61.43   60.77   60.72    60.7
   60.74   60.77   60.31   60.19   60.19   60.03   60.04   59.94   59.96   59.91
   59.95   59.84   59.88   59.83   59.85   59.82   61.13   61.02   60.99    61.1
    61.2   61.42   61.46   61.43   61.37   61.44   61.46   61.42   61.52   61.54
   61.65   61.98   62.07   62.11   62.32   62.45   63.28   65.55   70.44    70.5
   70.72   70.74   70.85   70.85   70.73   70.53   69.93   73.78
                                                                                
                                                                                
                                                                                
                                                                                
                                                                                
                                                                
       0    90.6   314.6   503.2   534.2   581.9   612.8   648.6   654.4   662.2
   667.6   681.9   711.9   718.7   725.8   732.9   739.8   746.7   753.7   760.5
   767.6   774.8   781.5   797.8     802     814   835.4   874.3   894.3   938.1
   975.5  1046.8  1062.3    1087  1103.5  1176.8  1186.2  1235.3  1271.2  1296.9
  1331.1  1382.9    1406  1423.8  1465.2  1486.8  1588.5  1707.1  1910.2  1919.6
  1949.2  1959.1  1980.7  1991.3  2004.2  2020.9  2055.5  2150.6
    76.4   75.14   68.02   63.47   63.01   62.14   61.43   60.77   60.72    60.7
   60.74   60.77   60.31   60.19   60.19   60.03   60.04   59.94   59.96   59.91
   59.95   59.84   59.88   59.83   59.85   59.82   61.13   61.02   60.99    61.1
    61.2   61.42   61.46   61.43   61.37   61.44   61.46   61.42   61.52   61.54
   61.65   61.98   62.07   62.11   62.32   62.45   63.28   65.55   70.44    70.5
   70.72   70.74   70.85   70.85   70.73   70.53   69.93   73.78
                                                                                
                                                                                
                                                                                
                                                                                
                                                                                
                                                                
BR Coef=-1 , 0 , 0 ,, 0 ,,,0.8,0,,0,
WSPro=,,,, 1 ,,,, 0 ,,,, 0 ,,,,-1 ,-1 ,-1 , 0 , 0 , 0 , 0 , 0
Multiple Barrel Culv=2,12,10,125,0.012,0.4,1,8,1,44.33,44.31, 3,Culvert #1  , 0 ,36.5
 1062.09 1131.33 1072.94 1142.18 1083.79 1153.03
BC Culvert Barrel=1,Barrel1,0
BC Culvert Barrel=2,Barrel2,0
BC Culvert Barrel=3,Barrel3,0
Culvert Bottom n=0.012
BC Design=,, 0 ,, 0 ,,,,,,
BC Use User HTab Curves=0
BC User HTab FreeFlow(D)= 0

--- ReedyCreek.g03 (geometry) ---

Geom Title=Natural Conditions
Program Version=6.60

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
River Reach=Reedy Creek     ,Reach-1

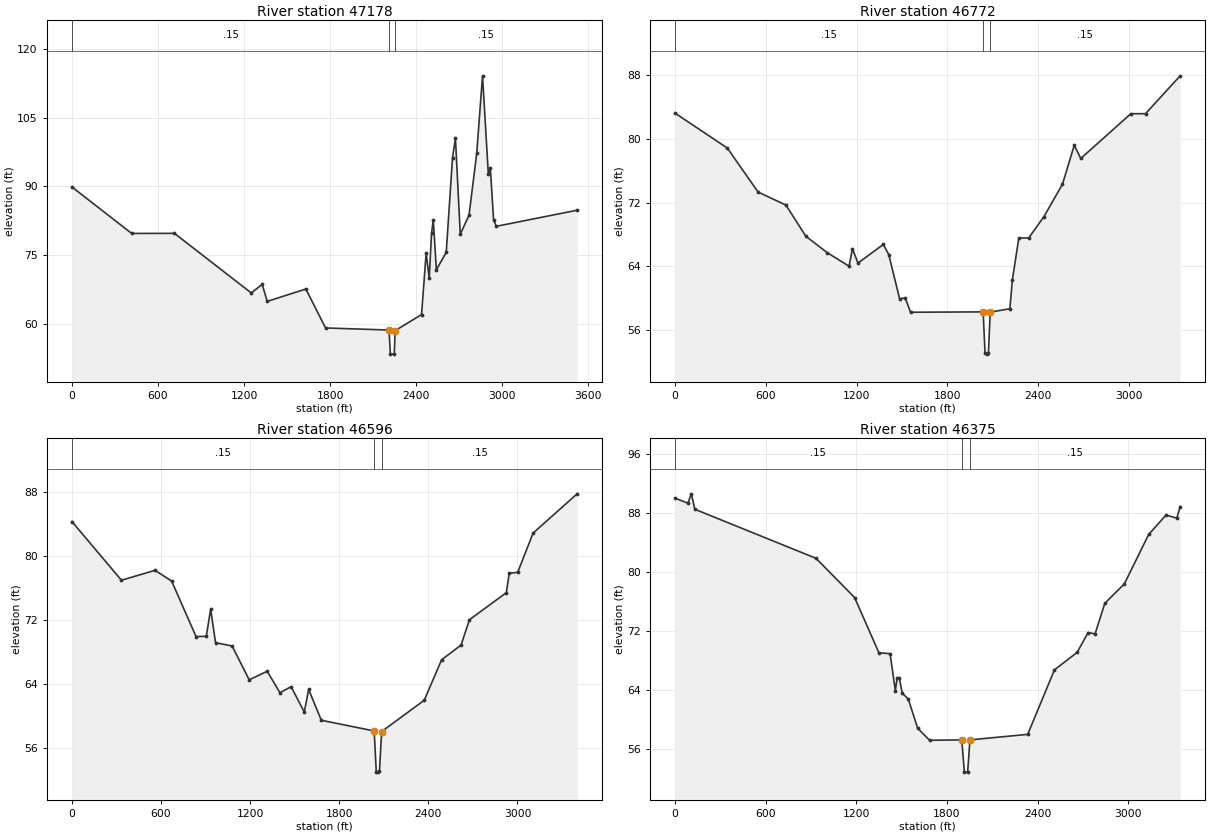
Type RM Length L Ch R = 1 ,47178   ,266.8,406.4,482.3
XS GIS Cut Line= 4
 2513535.9266087827956.3307230822511804.34717864827928.402022597
2511036.10972626 828251.782405932510106.39474182828029.145558214
#Sta/Elev= 30
       0   89.88   416.5   79.71   714.4   79.73  1249.9   66.69    1326   68.55
  1361.4   64.84  1630.5   67.55  1767.8   59.03  2210.458.56383  2219.6    53.3
 2246.77    53.3  2253.1 58.4404    2437   61.96  2469.1   75.48  2490.4   69.85
  2506.6   79.72  2518.8   82.66  2540.2   71.77    2609   75.56  2652.8    96.3
  2673.1  100.58  2706.8   79.54  2767.8    83.7  2821.5   97.25    2862   114.2
  2902.5   92.64    2916   94.13    2939    82.7  2958.2   81.27  3521.3   84.79
#Mann= 3 ,0,0
       0     .15       0  2210.4     .05       0  2253.1     .15       0
Bank Sta=2210.4,2253.1
XS Rating Curve= 0 ,0
Exp/Cntr(USF)=0,0
Exp/Cntr=0.3,0.1

Type RM Length L Ch R = 1 ,46772   ,179.4,175.7,167
XS GIS Cut Line= 4
 2513199.7504981827808.9292448992511801.02283972827767.550579636
2510875.60271857827770.0216672842509879.68710229827959.905697057
#Sta/Elev= 30
       0   83.23  346.15   78.84  549.63   73.32  733.43   71.69  864.71   67.79
 1005.83   65.73 1150.24   64.03 1173.22   66.21 1209.32   64.42  1376.7   66.75
  1412.8   65.49 1484.97   59.92 1521.06   60.07 1557.15   58.25 2036.63    58.3
 2049.35    53.1  2060.2      53 2071.63    53.1  2083.3   58.27 2213.27   58.69
 2229.67   62.29 2272.32   67.55 2338.17   67.58 2438.21   70.24 2560.82    74.3
 2638.74   79.18 2682.16   77.54 3012.79   83.15 3109.64   83.15 3338.62    87.9
#Mann= 3 ,0,0
       0     .15       0 2036.63     .05       0  2083.3     .15       0
Bank Sta=2036.63,2083.3
XS Rating Curve= 0 ,0
Exp/Cntr(USF)=0,0
Exp/Cntr=0.3,0.1

Type RM Length L Ch R = 1 ,46596   ,383.8,221.6,240.9
XS GIS Cut Line= 4
2513209.94240113827637.9214300222511620.24621303827581.322339733
2510862.31056917827601.0089798342509830.54002415827809.777424141
#Sta/Elev= 30
       0   84.29   333.4   76.95   559.9   78.19   671.5   76.84   835.7    69.9
   904.6   69.93   934.2   73.33     967   69.14  1078.6   68.72  1193.5   64.49
    1315   65.56  1400.3   62.88  1475.8   63.63  1564.4   60.46  1593.9   63.28
  1679.3   59.43 2035.12   58.09 2049.13   52.99  2059.4   52.94 2070.35   53.02
 2085.65   58.02  2372.2   61.93  2489.3      67  2619.9   68.83  2676.8   72.01
    2925   75.39  2944.6   77.82  3001.5   77.94  3105.2   82.85  3401.6   87.76
#Mann= 3 ,0,0
       0     .15       0 2035.12     .05       0 2085.65     .15       0
Bank Sta=2035.12,2085.65
XS Rating Curve= 0 ,0
Exp/Cntr(USF)=0,0
Exp/Cntr=0.3,0.1

Type RM Length L Ch R = 1 ,46375   ,901.7,929.5,715.4
BEGIN DESCRIPTION:
Reedy Creek XS 38.0
END DESCRIPTION:
XS GIS Cut Line= 5
      2512691.68       826394.382511570.51752009827369.069651817
      2511435.84       827373.07      2510699.64       827373.07
2509795.84098941827770.546208584
#Sta/Elev= 30
       0   90.06    85.2   89.37     109   90.64   131.1   88.55   933.4    81.9
  1189.1   76.58  1350.2   69.08  1424.1   68.97  1458.8   63.97  1470.6   65.67
  1484.5   65.71  1504.8   63.59  1544.2   62.84  1606.5   58.86  1685.3   57.23
  1898.5   57.28  1915.7   52.91 1937.44   52.91  1952.3   57.28  2334.8   58.03
    2512   66.78  2662.5   69.15  2734.2   71.82  2780.8   71.66  2845.3    75.8
  2974.3   78.43  3135.6   85.13  3250.3   87.76    3322   87.34  3343.9   88.91
#Mann= 3 ,0,0
       0     .15       0  1898.5     .05       0  1952.3     .15       0
Bank Sta=1898.5,1952.3
XS Rating Curve= 0 ,0
Exp/Cntr=0.3,0.1