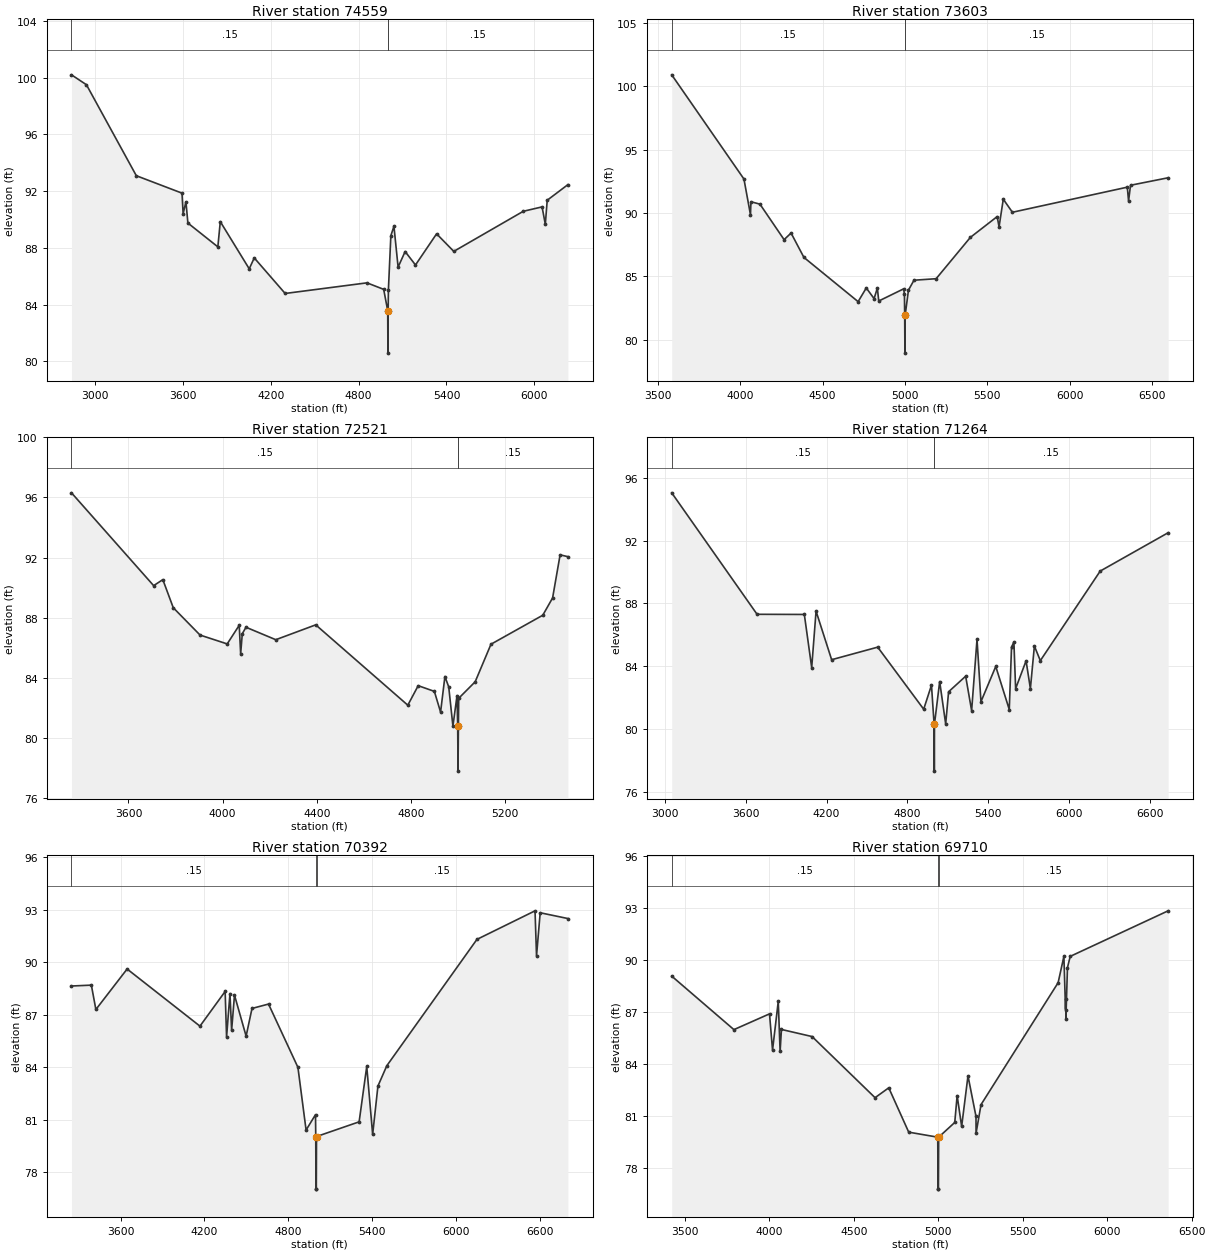
HEC-RAS study ReedyCreek.prj: S-34-32 over Reedy Creek

--- ReedyCreek.g03 (geometry) --- (continued)

Type RM Length L Ch R = 2 ,40622   ,,,
BEGIN DESCRIPTION:
Three Box Culvert, Structure Length=31.7 ft, Deck Width out-to-out=125 ft, Approaching roadway=77 ft, each barrel-width 10 ft and height 12 ft.
END DESCRIPTION:
Node Name=E Hwy 501
Bridge Culvert-0,0,0,0, 0
Deck Dist Width WeirC Skew NumUp NumDn MinLoCord MaxHiCord MaxSubmerge Is_Ogee
35.14436,125,2.6,0, 58, 58, , , 0.98, 0, 2,2,,
       0    24.6   248.6   437.2   468.2   515.9   546.8   582.6   588.4   596.2
   601.6   615.9   645.9   652.7   659.8   666.9   673.8   680.7   687.7   694.5
   701.6   708.8   715.5   731.8     736     748   769.4   808.3   828.3   872.1
   909.5   980.8   996.3    1021  1037.5  1110.8  1120.2  1169.3  1205.2  1230.9
  1265.1  1316.9    1340  1357.8  1399.2  1420.8  1522.5  1641.1  1844.2  1853.6
  1883.2  1893.1  1914.7  1925.3  1938.2  1954.9  1989.5  2084.6
    76.4   75.14   68.02   63.47   63.01   62.14   61.43   60.77   60.72    60.7
   60.74   60.77   60.31   60.19   60.19   60.03   60.04   59.94   59.96   59.91
   59.95   59.84   59.88   59.83   59.85   59.82   61.13   61.02   60.99    61.1
    61.2   61.42   61.46   61.43   61.37   61.44   61.46   61.42   61.52   61.54
   61.65   61.98   62.07   62.11   62.32   62.45   63.28   65.55   70.44    70.5
   70.72   70.74   70.85   70.85   70.73   70.53   69.93   73.78
                                                                                
                                                                                
                                                                                
                                                                                
                                                                                
                                                                
       0    90.6   314.6   503.2   534.2   581.9   612.8   648.6   654.4   662.2
   667.6   681.9   711.9   718.7   725.8   732.9   739.8   746.7   753.7   760.5
   767.6   774.8   781.5   797.8     802     814   835.4   874.3   894.3   938.1
   975.5  1046.8  1062.3    1087  1103.5  1176.8  1186.2  1235.3  1271.2  1296.9
  1331.1  1382.9    1406  1423.8  1465.2  1486.8  1588.5  1707.1  1910.2  1919.6
  1949.2  1959.1  1980.7  1991.3  2004.2  2020.9  2055.5  2150.6
    76.4   75.14   68.02   63.47   63.01   62.14   61.43   60.77   60.72    60.7
   60.74   60.77   60.31   60.19   60.19   60.03   60.04   59.94   59.96   59.91
   59.95   59.84   59.88   59.83   59.85   59.82   61.13   61.02   60.99    61.1
    61.2   61.42   61.46   61.43   61.37   61.44   61.46   61.42   61.52   61.54
   61.65   61.98   62.07   62.11   62.32   62.45   63.28   65.55   70.44    70.5
   70.72   70.74   70.85   70.85   70.73   70.53   69.93   73.78
                                                                                
                                                                                
                                                                                
                                                                                
                                                                                
                                                                
BR Coef=-1 , 0 , 0 ,, 0 ,,,0.8,0,,0,
WSPro=,,,, 1 ,,,, 0 ,,,, 0 ,,,,-1 ,-1 ,-1 , 0 , 0 , 0 , 0 , 0
Multiple Barrel Culv=2,12,10,125,0.012,0.4,1,8,1,44.33,44.31, 3,Culvert #1  , 0 ,36.5
 1062.09 1131.33 1072.94 1142.18 1083.79 1153.03
BC Culvert Barrel=1,Barrel1,0
BC Culvert Barrel=2,Barrel2,0
BC Culvert Barrel=3,Barrel3,0
Culvert Bottom n=0.012
BC Design=,, 0 ,, 0 ,,,,,,
BC Use User HTab Curves=0
BC User HTab FreeFlow(D)= 0

--- ReedyCreek.g05 (geometry) ---

Geom Title=Duplicate Effective
Program Version=6.60

River Reach=Reedy Creek     ,Reach-1

Type RM Length L Ch R = 1 ,74559   ,956,956,956
BEGIN DESCRIPTION:
Reedy Creek XS 67.0
END DESCRIPTION:
XS GIS Cut Line= 3
      2523316.18       851078.08       2520926.2       851698.13
      2520351.23       852419.65
#Sta/Elev= 30
  2837.9  100.21  2940.1   99.51  3280.9   93.09    3593   91.86  3600.7   90.41
  3619.9   91.25  3633.2   89.75  3837.9   88.07  3854.6   89.85  4052.3   86.52
  4086.7   87.29  4297.8   84.78  4856.9   85.53    4971   85.07  4998.5   83.57
  4999.9   80.57  5001.5   83.57  5003.2   85.04    5020   88.86  5041.1   89.52
  5069.5   86.64  5117.5   87.74  5188.3   86.79  5332.5   88.99  5449.9   87.75
  5924.8   90.58  6053.2   90.89  6075.3   89.66  6088.3   91.36  6229.6   92.46
#Mann= 3 ,-1,0
  2837.9     .15       0  4998.5     .05       0  5001.5     .15       0
Bank Sta=4998.5,5001.5
XS Rating Curve= 0 ,0
Exp/Cntr=0.3,0.1

Type RM Length L Ch R = 1 ,73603   ,1082,1082,1082
BEGIN DESCRIPTION:
Reedy Creek XS 66.0
END DESCRIPTION:
XS GIS Cut Line= 2
      2522820.11       850435.51      2519945.45       851348.64
#Sta/Elev= 30
    3583   100.9  4021.9   92.68  4061.6   89.86  4064.3   90.89  4119.1    90.7
  4265.8    87.9  4308.2   88.42  4386.2    86.5  4715.6   83.01  4765.1   84.09
  4812.6   83.25  4832.5   84.08  4840.9   83.06  4992.1   84.02  4996.9   83.61
  4998.5   81.95  4999.9   78.95  5001.5   81.95  5021.5   83.92    5055    84.7
  5189.6   84.82  5397.7   88.08  5560.6   89.72  5571.9   88.91  5597.6   91.09
    5653   90.06  6351.2   92.04  6358.8   90.95  6370.8   92.19  6599.2   92.78
#Mann= 3 ,-1,0
    3583     .15       0  4998.5     .05       0  5001.5     .15       0
Bank Sta=4998.5,5001.5
XS Rating Curve= 0 ,0
Exp/Cntr=0.3,0.1

Type RM Length L Ch R = 1 ,72521   ,1257,1257,1257
BEGIN DESCRIPTION:
Reedy Creek XS 65.0
END DESCRIPTION:
XS GIS Cut Line= 2
      2522233.89       849026.35      2520520.34       850255.14
#Sta/Elev= 30
    3358   96.31    3707   90.13    3746   90.53  3790.3   88.66  3904.1   86.84
  4019.4   86.25  4070.5   87.49  4076.6   85.59  4083.5   86.93  4099.3   87.36
  4225.8   86.53  4395.5   87.52  4786.6   82.17  4830.7   83.47  4899.4   83.09
  4925.8   81.71  4944.2   84.08  4960.4   83.39  4978.2   80.78  4995.7   82.81
  4998.5   80.78  4999.9   77.78  5001.5   80.78  5002.8   82.63  5072.8   83.73
  5139.9   86.23  5359.9   88.16  5401.6   89.31  5433.5   92.18  5466.6   92.06
#Mann= 3 ,-1,0
    3358     .15       0  4998.5     .05       0  5001.5     .15       0
Bank Sta=4998.5,5001.5
XS Rating Curve= 0 ,0
Exp/Cntr=0.3,0.1

Type RM Length L Ch R = 1 ,71264   ,872,872,872
BEGIN DESCRIPTION:
Reedy Creek XS 64.0
END DESCRIPTION:
XS GIS Cut Line= 2
      2522190.05       848747.46      2518536.31        849240.1
#Sta/Elev= 30
  3049.9   95.04  3683.8   87.31  4034.8    87.3  4089.5   83.92  4121.9   87.51
  4237.6   84.42  4579.7   85.22  4921.3   81.27  4979.1    82.8  4998.5   80.33
  5000.1   77.33  5001.5   80.33    5040   83.03  5084.6   80.33  5106.2   82.38
    5233   83.37  5277.3   81.18  5317.3   85.71  5346.6   81.75  5456.5   83.99
  5556.9   81.25  5573.6   85.22  5591.2   85.55  5604.1   82.58  5681.7   84.35
  5713.7   82.58  5743.4   85.29  5787.5   84.36  6232.2   90.06  6736.7    92.5
#Mann= 3 ,-1,0
  3049.9     .15       0  4998.5     .05       0  5001.5     .15       0
Bank Sta=4998.5,5001.5
XS Rating Curve= 0 ,0
Exp/Cntr=0.3,0.1

Type RM Length L Ch R = 1 ,70392   ,682,682,682
BEGIN DESCRIPTION:
Reedy Creek XS 63.0
END DESCRIPTION:
XS GIS Cut Line= 2
      2521512.72       847433.72        2518331.       849014.32
#Sta/Elev= 30
  3249.1   88.64  3391.3   88.69  3423.7    87.3  3647.2   89.61  4168.5   86.35
  4348.8   88.33    4359   85.73  4383.3   88.21  4395.2   86.12  4415.7   88.12
  4498.9   85.78    4541   87.36  4659.3   87.61  4869.6      84  4928.1   80.42
  4995.5    81.3  4997.3   80.05  4998.8   77.05  5001.2   77.05  5002.7   80.05
  5307.7   80.89  5362.2   84.05  5404.5   80.17  5442.2   82.93  5505.8   84.09
  6150.8    91.3  6566.6   92.93  6577.3   90.36  6603.5   92.82  6801.8   92.49
#Mann= 3 ,-1,0
  3249.1     .15       0  4997.3     .05       0  5002.7     .15       0
Bank Sta=4997.3,5002.7
XS Rating Curve= 0 ,0
Exp/Cntr=0.3,0.1

Type RM Length L Ch R = 1 ,69710   ,1214,1214,1214
BEGIN DESCRIPTION:
Reedy Creek XS 62.0
END DESCRIPTION:
XS GIS Cut Line= 2
       2520917.4        847023.2      2518269.45       848295.85
#Sta/Elev= 30
  3422.8   89.09  3790.9      86  4001.5   86.91  4019.5   84.82  4053.3   87.63
  4064.3   84.74  4072.1   86.01  4253.5    85.6  4626.2   82.07  4707.3   82.64
  4825.4   80.08  4997.3   79.79  4998.8   76.79  5001.2   76.79  5002.7   79.79
  5097.9   80.64    5112   82.19  5138.7   80.41  5176.2   83.33  5223.6   80.99
    5224   80.02  5253.4   81.67  5709.7   88.71  5743.8   90.23  5753.4   87.16
  5755.2   87.77  5755.7   86.64  5764.9   89.58  5781.3   90.23  6360.7   92.86
#Mann= 3 ,-1,0
  3422.8     .15       0  4997.3     .05       0  5002.7     .15       0
Bank Sta=4997.3,5002.7
XS Rating Curve= 0 ,0
Exp/Cntr=0.3,0.1

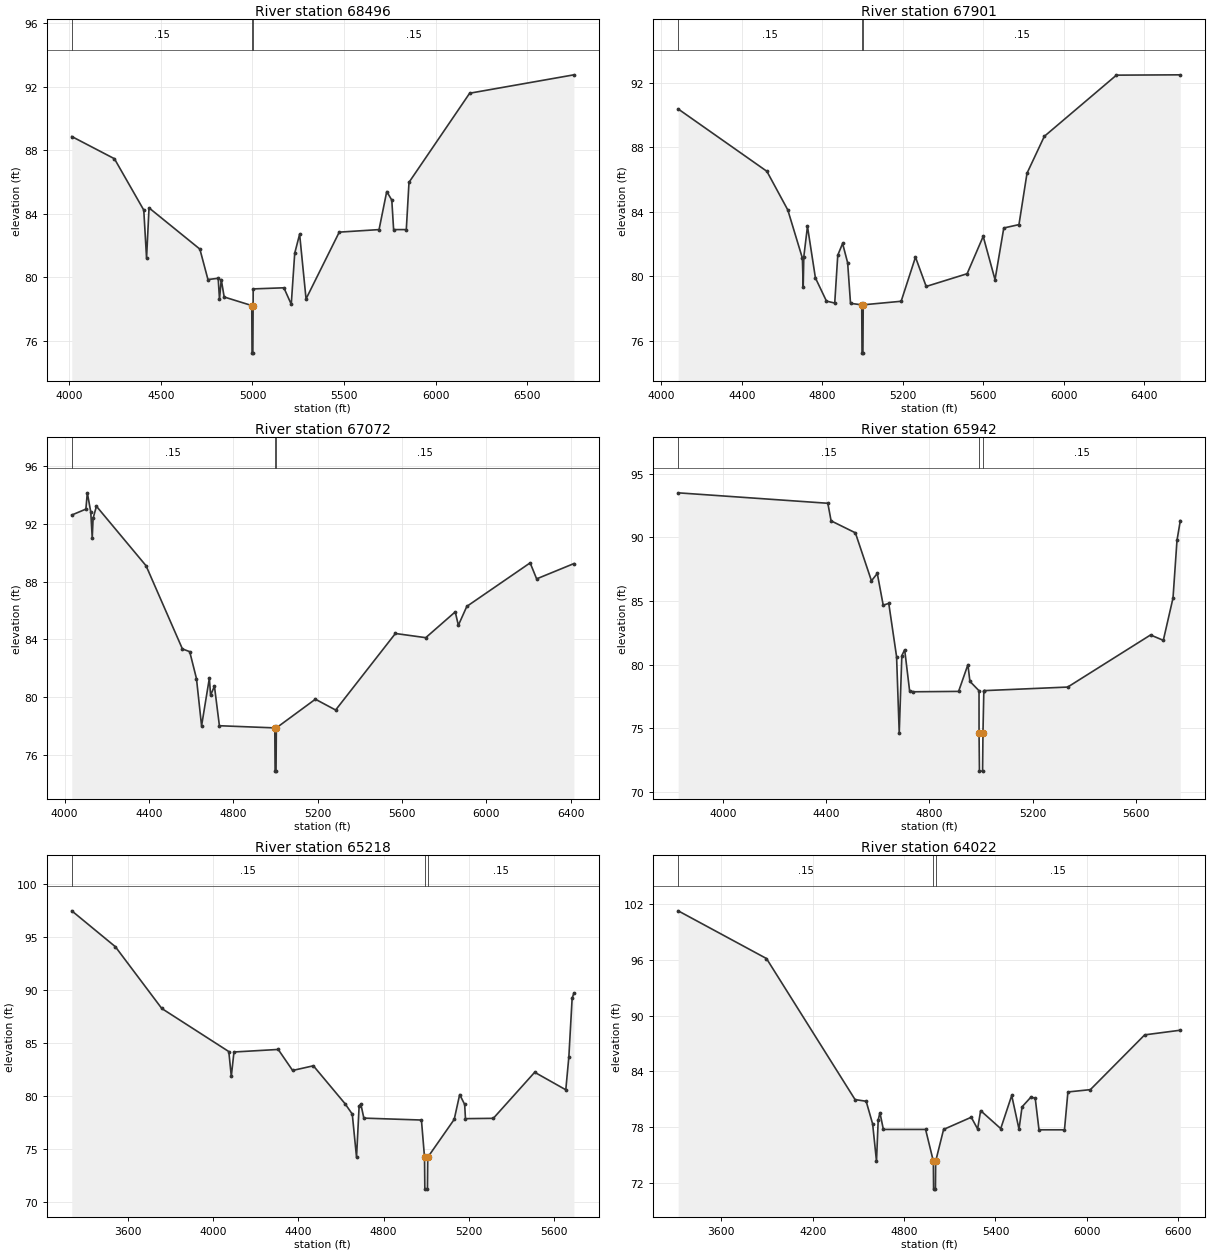
Type RM Length L Ch R = 1 ,68496   ,595,595,595
BEGIN DESCRIPTION:
Reedy Creek XS 61.0
END DESCRIPTION:
XS GIS Cut Line= 3
      2519111.04       845709.44      2519193.15       846325.27
      2518187.34       848193.21
#Sta/Elev= 30
  4013.1   88.87    4246   87.47  4406.4   84.23  4421.6    81.2  4435.1   84.37
  4712.8   81.77    4757   79.85  4812.8   79.93    4820   78.61  4829.6   79.85
  4845.6   78.75  4996.3   78.21  4997.8   75.21  5002.2   75.21  5003.7   78.21
  5004.1   79.26  5171.8   79.33    5212   78.29  5230.9   81.51  5257.7   82.71
  5292.8   78.63  5474.1   82.84  5691.6      83  5733.5    85.4  5761.2   84.86
  5771.1      83  5840.4      83  5855.1   85.98  6186.5    91.6  6755.9   92.76
#Mann= 3 ,-1,0
  4013.1     .15       0  4996.3     .05       0  5003.7     .15       0
Bank Sta=4996.3,5003.7
XS Rating Curve= 0 ,0
Exp/Cntr=0.3,0.1

Type RM Length L Ch R = 1 ,67901   ,829,829,829
BEGIN DESCRIPTION:
Reedy Creek XS 60.0
END DESCRIPTION:
XS GIS Cut Line= 2
      2519008.43       845524.68       2517715.2       847659.53
#Sta/Elev= 30
  4083.9   90.38  4524.8   86.51  4628.8   84.11  4701.3   81.12  4705.4   79.32
  4708.4    81.2  4726.6   83.09  4766.1   79.89    4821   78.45  4862.1   78.33
  4877.2    81.3  4901.2   82.03  4926.3   80.83  4940.6   78.31  4996.3   78.22
  4997.8   75.22  5002.2   75.22  5003.7   78.22  5192.3   78.44  5263.5   81.18
  5316.7   79.36  5520.2   80.15  5600.1   82.47  5658.9   79.78  5702.4   82.99
  5777.9    83.2  5817.9   86.39  5903.9   88.68  6262.3   92.48  6579.9    92.5
#Mann= 3 ,-1,0
  4083.9     .15       0  4996.3     .05       0  5003.7     .15       0
Bank Sta=4996.3,5003.7
XS Rating Curve= 0 ,0
Exp/Cntr=0.3,0.1

Type RM Length L Ch R = 1 ,67072   ,1130,1130,1130
BEGIN DESCRIPTION:
Reedy Creek XS 59.0
END DESCRIPTION:
XS GIS Cut Line= 2
      2518823.62       845216.84       2516750.4       846386.88
#Sta/Elev= 30
  4033.8   92.62  4100.7   93.03  4107.5   94.16  4123.8   92.84  4130.8   91.03
  4134.9   92.39  4150.7   93.23    4386    89.1  4558.3   83.33  4592.9   83.14
    4625   81.27  4649.2   77.99  4686.1    81.3  4691.9   80.12  4710.2   80.74
  4733.7      78  4996.3   77.85  4997.8   74.85  5002.2   74.85  5003.7   77.85
  5188.7   79.84  5284.8   79.09  5568.1    84.4    5712   84.11  5851.8    85.9
  5866.6   84.97  5906.7   86.28  6206.9    89.3  6237.7   88.19  6414.4   89.25
#Mann= 3 ,-1,0
  4033.8     .15       0  4996.3     .05       0  5003.7     .15       0
Bank Sta=4996.3,5003.7
XS Rating Curve= 0 ,0
Exp/Cntr=0.3,0.1

Type RM Length L Ch R = 1 ,65942   ,724,724,724
BEGIN DESCRIPTION:
Reedy Creek XS 58.0
END DESCRIPTION:
XS GIS Cut Line= 2
      2518946.79       844601.01       2517000.1        844660.6
#Sta/Elev= 30
  3825.4   93.49  4405.9   92.67  4418.5   91.29  4512.7   90.35  4575.1   86.58
  4597.7   87.16  4620.6   84.67  4642.2   84.81  4672.5   80.63  4682.8   74.64
  4692.9   80.71  4703.9   81.17  4722.9   77.97  4736.5   77.87  4913.1    77.9
  4949.2      80  4956.9   78.69  4992.3   77.95  4992.4   74.64  4993.9   71.64
  5006.1   71.64  5007.6   74.64  5010.9   77.92  5012.4   77.96  5336.3   78.24
  5657.5   82.33  5707.1   81.91  5744.7   85.23  5760.1   89.75    5773   91.31
#Mann= 3 ,-1,0
  3825.4     .15       0  4992.4     .05       0  5007.6     .15       0
Bank Sta=4992.4,5007.6
XS Rating Curve= 0 ,0
Exp/Cntr=0.3,0.1

Type RM Length L Ch R = 1 ,65218   ,1196,1196,1196
BEGIN DESCRIPTION:
Reedy Creek XS 57.0
END DESCRIPTION:
XS GIS Cut Line= 2
      2519152.07       843184.66      2517041.76       844239.81
#Sta/Elev= 30
  3334.9   97.47  3539.7   94.09  3757.8   88.27  4072.8   84.21  4084.5   81.87
    4097   84.17  4304.9   84.41  4372.6   82.43  4470.1   82.87  4618.5   79.31
  4652.9   78.32  4672.9   74.25  4685.1   79.08  4693.2   79.26  4707.3   77.94
  4977.9   77.76  4992.4   74.25  4993.9   71.25  5006.1   71.25  5007.6   74.25
  5131.9   77.82  5157.6   80.16    5181   79.23  5184.8   77.89  5315.7   77.92
    5510   82.26  5656.2   80.61  5670.6   83.72    5686   89.23  5694.3   89.73
#Mann= 3 ,-1,0
  3334.9     .15       0  4992.4     .05       0  5007.6     .15       0
Bank Sta=4992.4,5007.6
XS Rating Curve= 0 ,0
Exp/Cntr=0.3,0.1

Type RM Length L Ch R = 1 ,64022   ,1008,1008,1008
BEGIN DESCRIPTION:
Reedy Creek XS 56.0
END DESCRIPTION:
XS GIS Cut Line= 3
      2519090.54       842671.47      2516976.24       842794.63
      2516093.59       842014.62
#Sta/Elev= 30
  3317.5  101.27  3897.1   96.14  4478.5   80.97  4551.3   80.79  4593.9   78.35
  4619.2   74.34  4630.4   78.78  4641.8   79.56  4664.3   77.76  4941.4   77.76
  4992.4   74.34  4993.9   71.34  5006.1   71.34  5007.6   74.34  5059.6   77.76
  5241.2   79.07  5282.9   77.81  5302.8   79.78  5434.6   77.85  5506.7   81.41
  5554.6   77.79  5574.7   80.19  5631.4   81.21  5660.8   81.14  5685.8   77.72
    5853   77.72  5875.6   81.79    6023   82.04  6379.5   87.93  6613.3   88.43
#Mann= 3 ,-1,0
  3317.5     .15       0  4992.4     .05       0  5007.6     .15       0
Bank Sta=4992.4,5007.6
XS Rating Curve= 0 ,0
Exp/Cntr=0.3,0.1

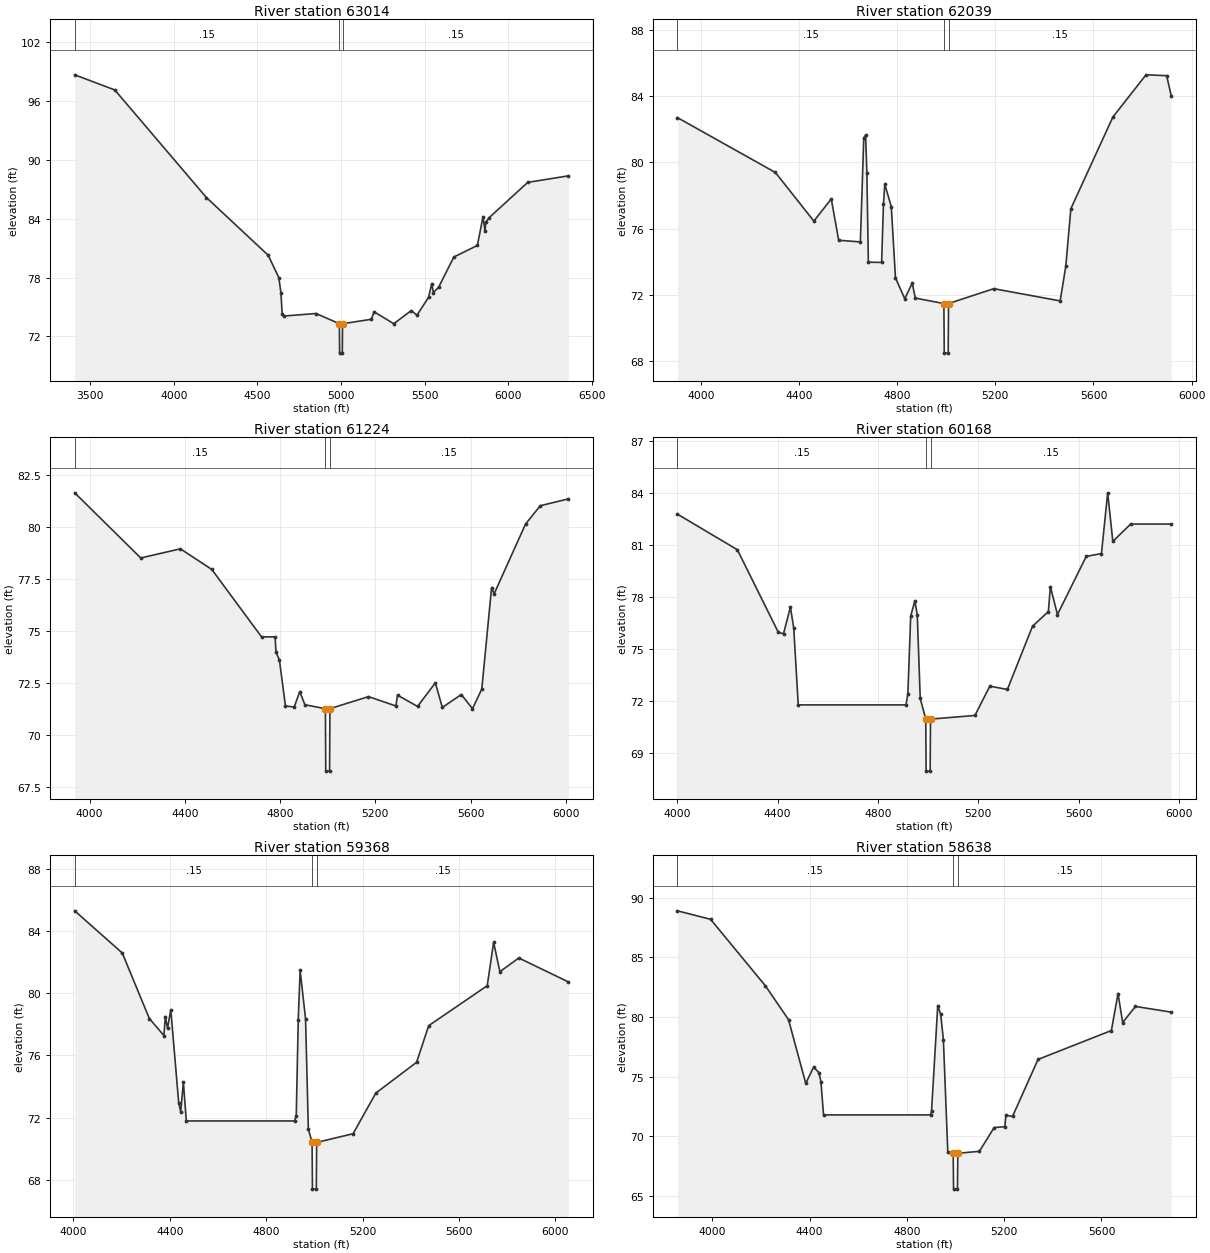
Type RM Length L Ch R = 1 ,63014   ,975,975,975
BEGIN DESCRIPTION:
Reedy Creek XS 55.0
END DESCRIPTION:
XS GIS Cut Line= 2
      2518926.26       841604.07      2515990.98       841932.49
#Sta/Elev= 30
  3407.4   98.68  3646.9   97.14    4195   86.17  4564.7   80.28  4628.4      78
  4640.8   76.47  4648.3    74.3  4656.5   74.08  4850.9   74.34  4990.5    73.3
    4992    70.3    5008    70.3  5009.5    73.3  5181.5   73.75  5198.5   74.51
  5315.9    73.3  5420.7   74.64  5454.8   74.17  5523.9   75.99  5543.4    77.4
  5552.7   76.48  5584.5   77.03  5675.2    80.1  5816.1   81.28  5849.8   84.22
  5861.9   82.72  5865.7   83.63  5885.5    84.1  6117.1   87.71    6361   88.38
#Mann= 3 ,-1,0
  3407.4     .15       0  4990.5     .05       0  5009.5     .15       0
Bank Sta=4990.5,5009.5
XS Rating Curve= 0 ,0
Exp/Cntr=0.3,0.1

Type RM Length L Ch R = 1 ,62039   ,815,815,815
BEGIN DESCRIPTION:
Reedy Creek XS 54.0
END DESCRIPTION:
XS GIS Cut Line= 2
      2518064.19       840906.15      2516052.52       840906.15
#Sta/Elev= 30
    3905   82.71  4304.1   79.39  4460.7   76.45  4531.7   77.79  4561.8   75.29
  4650.2   75.19  4664.1   81.48  4671.5   81.65  4676.7   79.37  4682.8   73.96
  4736.8   73.95  4744.3   77.48  4749.7   78.68  4776.2   77.32  4793.2   73.02
    4831   71.75  4861.3   72.69  4874.3   71.79  4990.5   71.46    4992   68.46
    5008   68.46  5009.5   71.46  5193.7   72.36  5464.2   71.62  5487.1   73.71
  5507.8    77.2  5679.2   82.75    5814    85.3  5898.2   85.25  5916.7   84.03
#Mann= 3 ,-1,0
    3905     .15       0  4990.5     .05       0  5009.5     .15       0
Bank Sta=4990.5,5009.5
XS Rating Curve= 0 ,0
Exp/Cntr=0.3,0.1

Type RM Length L Ch R = 1 ,61224   ,1056,1056,1056
BEGIN DESCRIPTION:
Reedy Creek XS 53.0
END DESCRIPTION:
XS GIS Cut Line= 2
      2517899.98       839715.57      2515970.38        840475.1
#Sta/Elev= 30
  3937.7   81.63    4215    78.5  4381.4   78.94  4513.3   77.95  4722.3   74.71
  4779.4   74.71    4783   73.97  4797.2   73.61  4822.7   71.39  4859.4   71.34
  4882.9   72.08  4904.3   71.45  4990.5   71.26    4992   68.26    5008   68.26
  5009.5   71.26  5171.5   71.84  5286.6   71.39  5293.3   71.91  5377.4   71.37
  5452.4    72.5  5481.6   71.32  5561.3   71.94  5608.2   71.26  5647.3    72.2
  5688.3   77.06  5699.2   76.78  5831.1   80.13  5892.9   81.01  6011.4   81.34
#Mann= 3 ,-1,0
  3937.7     .15       0  4990.5     .05       0  5009.5     .15       0
Bank Sta=4990.5,5009.5
XS Rating Curve= 0 ,0
Exp/Cntr=0.3,0.1

Type RM Length L Ch R = 1 ,60168   ,800,800,800
BEGIN DESCRIPTION:
Reedy Creek XS 52.0
END DESCRIPTION:
XS GIS Cut Line= 2
      2517140.44       839263.99      2515293.02       839941.38
#Sta/Elev= 30
    4001   82.79  4239.6   80.74  4402.8   75.98  4423.6   75.89  4451.1   77.43
  4464.4   76.22  4482.3   71.79  4911.8   71.79  4919.2   72.43  4930.5   76.91
    4947   77.79  4956.7   76.99  4968.5   72.16  4990.5   70.97    4992   67.97
    5008   67.97  5009.5   70.97  5186.4   71.18  5245.8   72.87  5315.8   72.68
  5416.1   76.33  5479.1   77.17  5487.1   78.61  5515.4      77  5629.9   80.35
  5690.7   80.52  5715.5   84.02    5736   81.22  5807.3   82.22  5968.7   82.22
#Mann= 3 ,-1,0
    4001     .15       0  4990.5     .05       0  5009.5     .15       0
Bank Sta=4990.5,5009.5
XS Rating Curve= 0 ,0
Exp/Cntr=0.3,0.1

Type RM Length L Ch R = 1 ,59368   ,730,730,730
BEGIN DESCRIPTION:
Reedy Creek XS 51.0
END DESCRIPTION:
XS GIS Cut Line= 2
      2516586.26       838217.08      2515087.76       839612.94
#Sta/Elev= 30
    4006   85.29  4203.2   82.58  4315.5   78.37  4375.8   77.28  4381.9    78.5
  4390.9   77.75  4404.5   78.93  4437.3   72.94  4445.6   72.38  4456.6   74.29
  4468.8   71.79  4918.3   71.79  4924.8   72.14  4933.1   78.27  4940.9   81.46
  4963.4   78.35    4975   71.27  4990.5   70.41    4992   67.41    5008   67.41
  5009.5   70.41  5160.5   70.97  5254.8   73.58    5424   75.56    5474   77.91
  5716.9   80.48  5743.4   83.27  5769.4   81.38  5847.9   82.26  6053.9   80.72
#Mann= 3 ,-1,0
    4006     .15       0  4990.5     .05       0  5009.5     .15       0
Bank Sta=4990.5,5009.5
XS Rating Curve= 0 ,0
Exp/Cntr=0.3,0.1

Type RM Length L Ch R = 1 ,58638   ,1072,1072,1072
BEGIN DESCRIPTION:
Reedy Creek XS 50.0
END DESCRIPTION:
XS GIS Cut Line= 2
      2516545.17       837786.05      2514697.74       838627.66
#Sta/Elev= 30
  3856.8   88.89    3993   88.18  4218.6    82.6  4313.4   79.77  4384.3   74.43
  4416.4   75.79  4438.7   75.33  4446.7   74.56  4457.4   71.79    4898   71.79
  4901.5   72.12    4927   80.95  4939.1   80.22  4950.2   78.09  4968.3   68.68
  4990.5   68.57    4992   65.57    5008   65.57  5009.5   68.57  5098.2   68.74
    5159   70.73  5202.5    70.8  5207.5   71.76  5234.4   71.66  5339.4   76.44
  5640.9   78.86  5668.2   81.96  5687.3   79.53  5739.8   80.88  5886.9    80.4
#Mann= 3 ,-1,0
  3856.8     .15       0  4990.5     .05       0  5009.5     .15       0
Bank Sta=4990.5,5009.5
XS Rating Curve= 0 ,0
Exp/Cntr=0.3,0.1

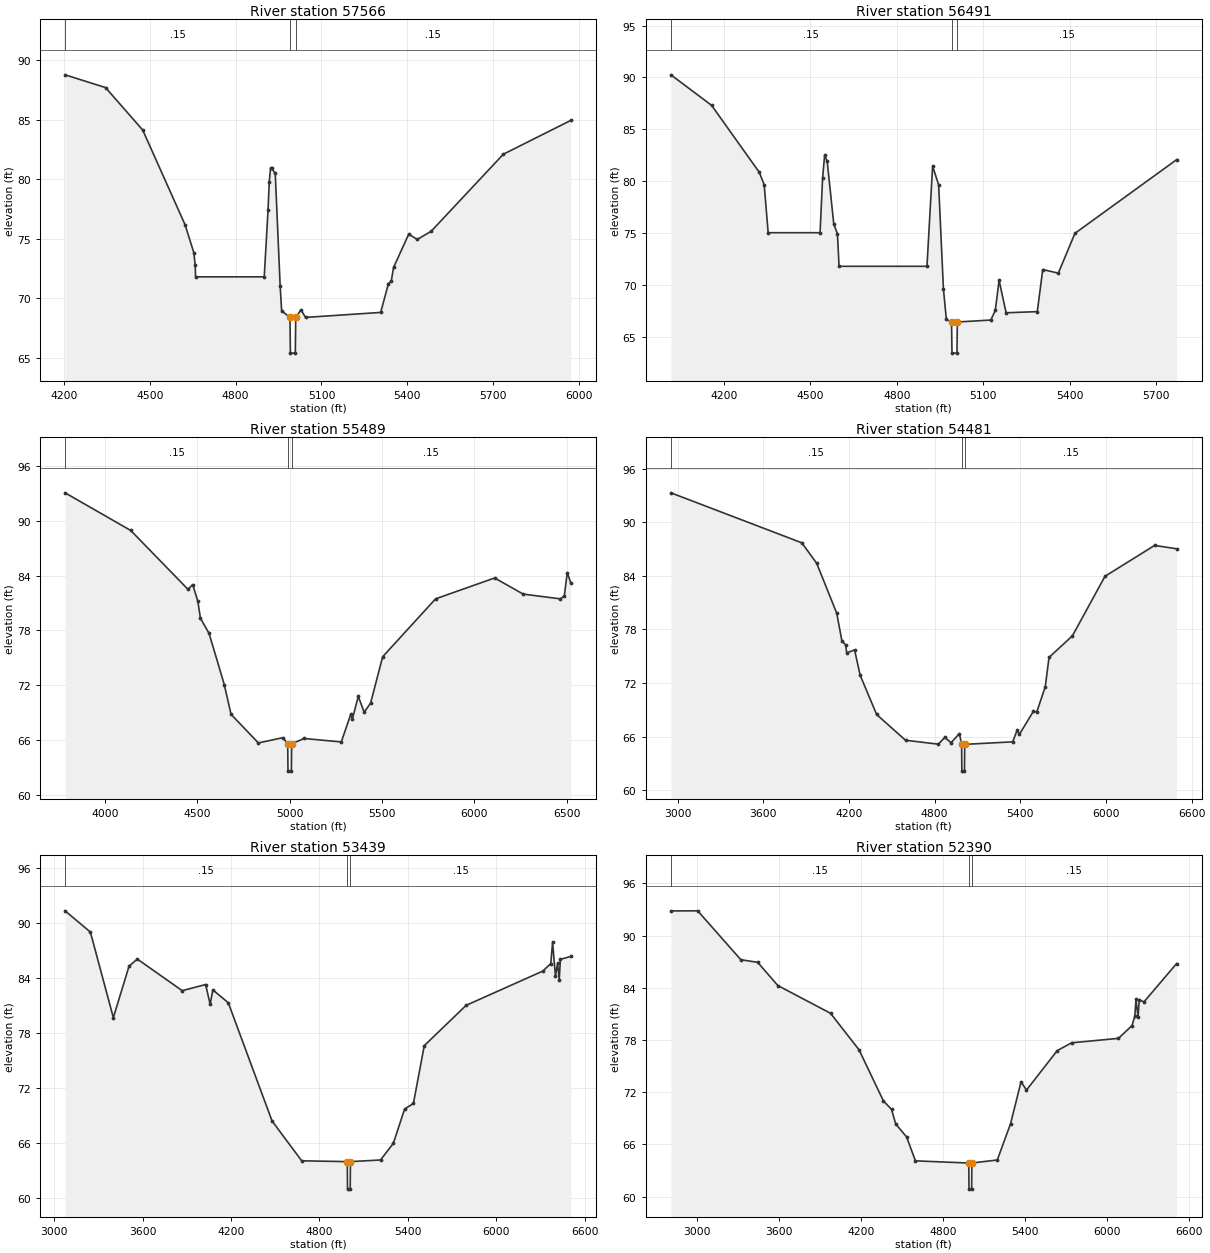
Type RM Length L Ch R = 1 ,57566   ,1075,1075,1075
BEGIN DESCRIPTION:
Reedy Creek XS 49.0
END DESCRIPTION:
XS GIS Cut Line= 2
      2516196.23       837088.13      2514451.43       837375.51
#Sta/Elev= 30
  4203.5   88.76    4345   87.69    4475   84.12    4623   76.17  4653.8   73.82
  4658.4   72.78  4659.9   71.79  4899.9   71.79  4913.3   77.42  4917.4   79.75
    4922   80.91  4925.6    80.9  4938.4   80.48  4955.6   71.02  4960.8   68.93
  4989.9   68.38  4991.4   65.38  5008.6   65.38  5010.1   68.38  5028.3   69.02
  5044.3   68.38  5307.2    68.8    5334   71.21  5344.1   71.43  5352.2   72.58
  5405.3   75.38  5434.7   74.93  5483.4   75.61    5736   82.09  5971.8   84.93
#Mann= 3 ,-1,0
  4203.5     .15       0  4989.9     .05       0  5010.1     .15       0
Bank Sta=4989.9,5010.1
XS Rating Curve= 0 ,0
Exp/Cntr=0.3,0.1

Type RM Length L Ch R = 1 ,56491   ,1002,1002,1002
BEGIN DESCRIPTION:
Reedy Creek XS 48.0
END DESCRIPTION:
XS GIS Cut Line= 2
      2516175.73       835815.44      2514574.54       836533.92
#Sta/Elev= 30
    4016   90.25  4157.1   87.31  4322.7   80.85  4339.7   79.65  4353.5   75.03
  4533.6   75.03  4542.4   80.29  4549.4   82.49  4558.3   81.92  4581.1   75.89
  4593.9   74.91  4599.5   71.79  4904.6   71.79  4924.2   81.44  4945.1   79.65
  4961.7   69.61  4971.9   66.68  4989.9   66.42  4991.4   63.42  5008.6   63.42
  5010.1   66.42  5126.2   66.61  5141.7   67.53  5154.9   70.44  5179.2   67.31
  5287.5   67.42  5306.4   71.48  5360.4   71.13  5418.2   74.97    5771   82.07
#Mann= 3 ,-1,0
    4016     .15       0  4989.9     .05       0  5010.1     .15       0
Bank Sta=4989.9,5010.1
XS Rating Curve= 0 ,0
Exp/Cntr=0.3,0.1

Type RM Length L Ch R = 1 ,55489   ,1008,1008,1008
BEGIN DESCRIPTION:
Reedy Creek XS 47.0
END DESCRIPTION:
XS GIS Cut Line= 2
      2516031.98       834665.96       2513753.5       836184.95
#Sta/Elev= 30
  3783.7    93.1  4139.3   88.97  4449.4   82.51  4474.7   83.04  4502.6    81.2
  4516.7   79.34  4563.4   77.68  4645.7   72.07  4682.5    68.8  4830.6   65.66
    4963   66.24  4989.3   65.57  4990.8   62.57  5009.2   62.57  5010.7   65.57
  5078.6   66.15  5279.5   65.77  5330.6    68.8  5339.8   68.32  5371.5   70.77
  5403.3   69.04    5438   70.02  5503.5   75.12  5790.1   81.47  6109.8   83.76
  6264.4   81.99  6465.5   81.47    6487   81.77  6503.2   84.34  6522.1   83.22
#Mann= 3 ,-1,0
  3783.7     .15       0  4989.3     .05       0  5010.7     .15       0
Bank Sta=4989.3,5010.7
XS Rating Curve= 0 ,0
Exp/Cntr=0.3,0.1

Type RM Length L Ch R = 1 ,54481   ,1042,1042,1042
BEGIN DESCRIPTION:
Reedy Creek XS 46.0
END DESCRIPTION:
XS GIS Cut Line= 2
      2516052.56        832982.7       2513548.2       835487.06
#Sta/Elev= 30
  2953.2   93.31  3869.9   87.71    3974   85.42  4114.8   79.81  4150.2   76.75
  4177.2   76.26  4184.4   75.38  4239.5   75.71  4278.4   72.88  4393.7   68.48
  4596.2   65.59  4826.1   65.15  4870.6    65.9  4915.4   65.32  4973.5   66.33
  4989.3   65.13  4990.8   62.13  5009.2   62.13  5010.7   65.13  5346.4   65.41
  5378.5   66.72  5394.4   66.26  5491.4   68.82  5515.5   68.75    5575   71.59
  5601.3   74.87  5764.9   77.28  5993.3   83.96    6341   87.42  6494.9   87.04
#Mann= 3 ,-1,0
  2953.2     .15       0  4989.3     .05       0  5010.7     .15       0
Bank Sta=4989.3,5010.7
XS Rating Curve= 0 ,0
Exp/Cntr=0.3,0.1

Type RM Length L Ch R = 1 ,53439   ,1049,1049,1049
BEGIN DESCRIPTION:
Reedy Creek XS 45.0
END DESCRIPTION:
XS GIS Cut Line= 2
      2515559.88       832387.45      2512870.86       834522.25
#Sta/Elev= 30
  3073.2   91.31  3245.1   88.99  3400.9   79.66  3507.5   85.27  3563.6   86.05
  3868.3    82.6  4027.7   83.27  4058.2    81.1  4076.4   82.69  4181.3   81.28
  4478.6   68.38  4679.8   64.04  4989.3   63.95  4990.8   60.95  5009.2   60.95
  5010.7   63.95    5215   64.13  5302.1   65.95  5378.2   69.68  5438.3    70.3
  5511.9    76.6  5796.2      81  6317.2   84.74  6370.9   85.56  6383.1   87.88
  6402.5   84.22  6417.1   85.58  6428.2   83.78  6436.2   86.02  6506.6   86.33
#Mann= 3 ,-1,0
  3073.2     .15       0  4989.3     .05       0  5010.7     .15       0
Bank Sta=4989.3,5010.7
XS Rating Curve= 0 ,0
Exp/Cntr=0.3,0.1

Type RM Length L Ch R = 1 ,52390   ,735,735,735
BEGIN DESCRIPTION:
Reedy Creek XS 44.0
END DESCRIPTION:
XS GIS Cut Line= 2
       2515395.7       831710.04       2512152.4       833495.91
#Sta/Elev= 30
  2807.9   92.83  3003.9   92.84  3319.8   87.22  3443.2   86.92  3590.9   84.25
  3976.7   81.06  4184.9   76.87  4363.7   70.99  4423.5   70.01  4453.7   68.34
  4533.8   66.84    4598    64.1  4988.8   63.85  4990.3   60.85  5009.7   60.85
  5011.2   63.85  5197.5    64.2    5295   68.39  5371.1   73.18  5411.3   72.24
  5636.3   76.77  5741.5   77.67  6084.6   78.18  6183.9   79.65  6204.2   80.71
  6212.9   82.65  6228.2   80.64  6236.9   82.61  6271.3   82.37  6510.4   86.78
#Mann= 3 ,-1,0
  2807.9     .15       0  4988.8     .05       0  5011.2     .15       0
Bank Sta=4988.8,5011.2
XS Rating Curve= 0 ,0
Exp/Cntr=0.3,0.1

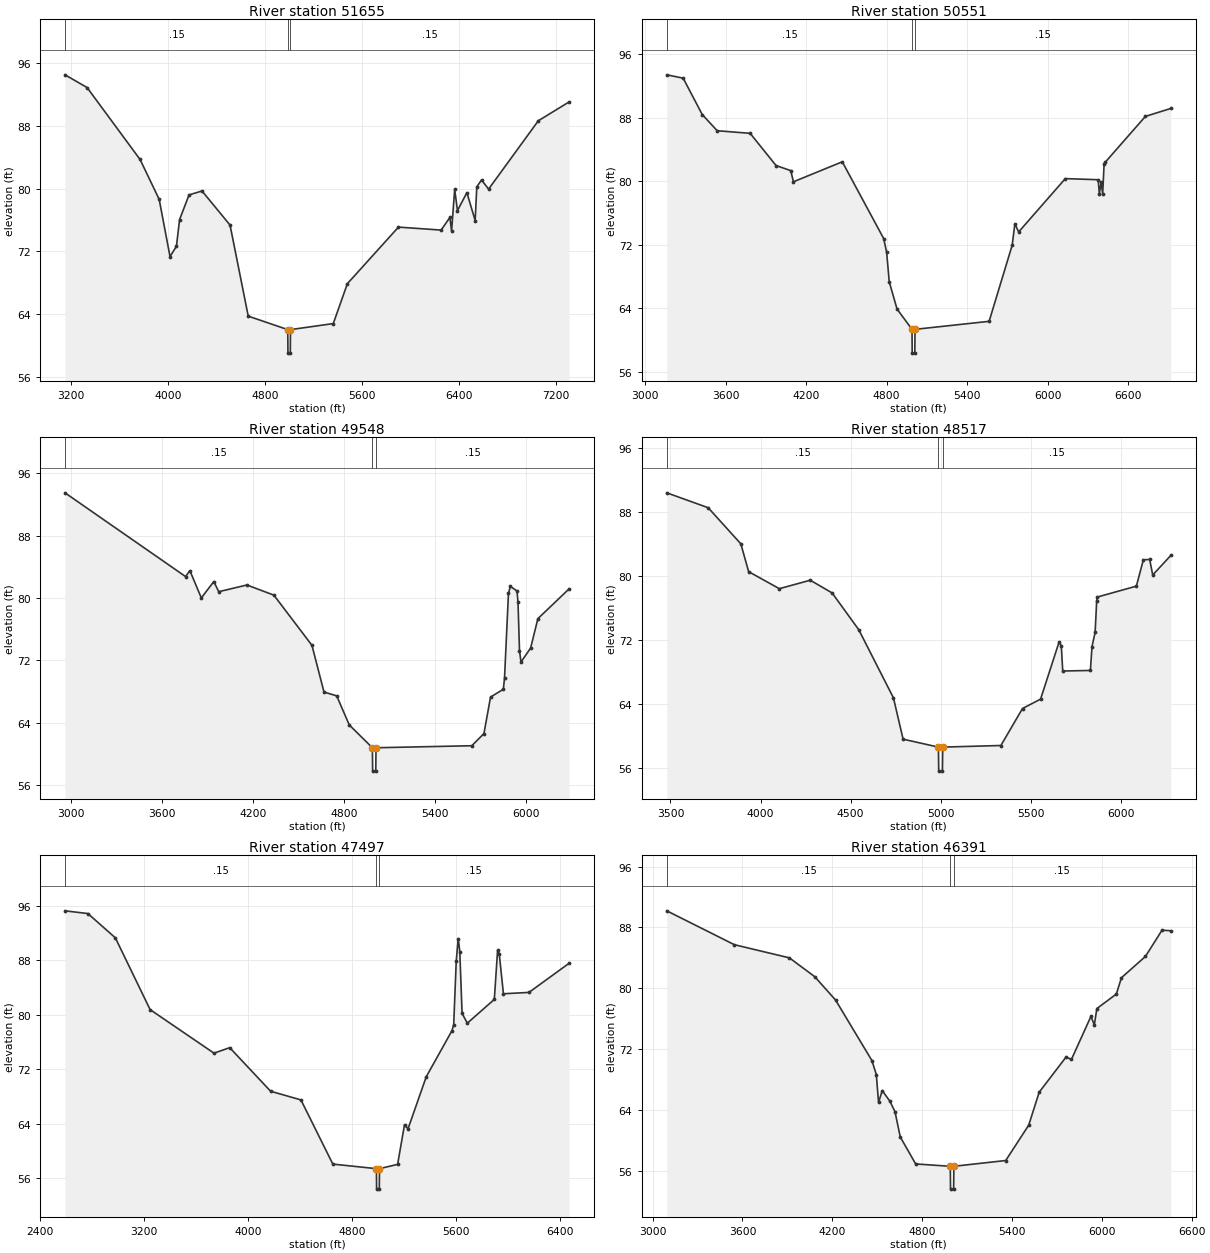
Type RM Length L Ch R = 1 ,51655   ,1104,1104,1104
BEGIN DESCRIPTION:
Reedy Creek XS 43.0
END DESCRIPTION:
XS GIS Cut Line= 2
      2515005.69       831340.56      2511187.66       832982.72
#Sta/Elev= 30
    3152   94.52    3334    92.9  3770.9   83.72  3928.4   78.64    4018   71.33
  4070.8   72.64  4096.9   76.06    4175    79.2  4281.6    79.7  4512.9   75.35
  4662.8   63.73  4988.8   62.01  4990.3   59.01  5009.7   59.01  5011.2   62.01
  5364.1   62.78  5480.2   67.87  5901.5   75.09  6253.1   74.71  6325.4   76.32
  6339.5   74.61  6365.1    79.9    6388    77.2  6465.6   79.49  6533.9   75.93
  6547.5   80.23  6586.3    81.1  6644.7   79.94  7054.7   88.66  7308.2   91.06
#Mann= 3 ,-1,0
    3152     .15       0  4988.8     .05       0  5011.2     .15       0
Bank Sta=4988.8,5011.2
XS Rating Curve= 0 ,0
Exp/Cntr=0.3,0.1

Type RM Length L Ch R = 1 ,50551   ,1003,1003,1003
BEGIN DESCRIPTION:
Reedy Creek XS 42.0
END DESCRIPTION:
XS GIS Cut Line= 2
      2514533.48       830293.72      2511126.05       831874.28
#Sta/Elev= 30
  3161.5   93.43  3283.4   93.01  3425.7   88.42  3537.2   86.38  3782.8   86.05
  3975.6   81.99  4085.1   81.35  4105.2   79.94  4469.2   82.46    4778   72.77
    4800   71.03  4818.9   67.35  4877.3   63.89  4988.8   61.33  4990.3   58.33
  5009.7   58.33  5011.2   61.33  5563.4   62.34  5735.3   71.94  5755.1   74.63
  5783.8   73.62  6131.1   80.34  6376.1    80.2  6384.7   78.41  6397.9   79.89
  6409.6   78.41  6420.1   82.15  6429.8   82.43  6728.2   88.19  6917.7   89.19
#Mann= 3 ,-1,0
  3161.5     .15       0  4988.8     .05       0  5011.2     .15       0
Bank Sta=4988.8,5011.2
XS Rating Curve= 0 ,0
Exp/Cntr=0.3,0.1

Type RM Length L Ch R = 1 ,49548   ,1031,1031,1031
BEGIN DESCRIPTION:
Reedy Creek XS 41.0
END DESCRIPTION:
XS GIS Cut Line= 2
      2514367.48       829585.33      2511195.12       830566.97
#Sta/Elev= 30
    2963   93.48  3757.5   82.73  3785.8   83.49  3861.1   79.99  3943.4   82.09
  3975.8   80.79  4161.5   81.65    4339   80.35  4589.8   73.91  4669.3   67.91
    4753   67.42  4835.7   63.69  4988.1   60.76  4989.6   57.76  5010.4   57.76
  5011.9   60.76    5643   61.02    5723   62.58  5766.4   67.26  5850.8   68.27
  5858.5   69.68  5884.5   80.57    5897   81.47  5940.9   80.88  5947.5   79.41
  5957.2   73.24  5966.9   71.76  6030.6   73.56  6078.3   77.33  6283.8   81.15
#Mann= 3 ,-1,0
    2963     .15       0  4988.1     .05       0  5011.9     .15       0
Bank Sta=4988.1,5011.9
XS Rating Curve= 0 ,0
Exp/Cntr=0.3,0.1

Type RM Length L Ch R = 1 ,48517   ,1020,1020,1020
BEGIN DESCRIPTION:
Reedy Creek XS 40.0
END DESCRIPTION:
XS GIS Cut Line= 2
      2513409.76       828962.84      2510680.34       829585.34
#Sta/Elev= 30
  3479.5   90.36  3709.3    88.5  3890.8   83.99    3934   80.52  4104.6   78.39
  4276.3   79.45  4397.8   77.86  4545.8   73.26  4738.3   64.76  4791.9    59.6
  4988.1   58.61  4989.6   55.61  5010.4   55.61  5011.9   58.61    5335   58.81
  5455.1   63.43  5555.4    64.6  5658.6   71.76  5670.6   71.22  5678.5   68.11
  5832.1   68.18  5841.1   71.17  5858.4   72.93  5867.1    76.9  5871.3   77.35
  6087.5   78.71  6126.2      82  6161.3   82.04  6178.3    80.1    6279   82.55
#Mann= 3 ,-1,0
  3479.5     .15       0  4988.1     .05       0  5011.9     .15       0
Bank Sta=4988.1,5011.9
XS Rating Curve= 0 ,0
Exp/Cntr=0.3,0.1

Type RM Length L Ch R = 1 ,47497   ,1106,1106,1106
BEGIN DESCRIPTION:
Reedy Creek XS 39.0
END DESCRIPTION:
XS GIS Cut Line= 4
      2513852.66       828160.78      2511853.52       828232.61
      2511314.83       828460.06      2510057.84       828160.78
#Sta/Elev= 30
  2592.8   95.23    2769   94.83  2980.2   91.27  3247.5   80.75  3739.1   74.36
  3859.8   75.17  4174.5   68.78  4407.6   67.51    4653    58.1  4988.1   57.43
  4989.6   54.43  5010.4   54.43  5011.9   57.43  5151.3   58.06  5204.4   63.88
  5231.3   63.27  5371.5    70.9  5569.6   77.67  5582.7   78.56  5602.2   87.85
  5617.4   91.17  5629.6   89.26  5647.1   80.19  5687.5   78.76  5895.2   82.25
  5920.3   89.45  5932.8   88.94  5965.3   83.07  6161.6   83.27  6470.1   87.54
#Mann= 3 ,-1,0
  2592.8     .15       0  4988.1     .05       0  5011.9     .15       0
Bank Sta=4988.1,5011.9
XS Rating Curve= 0 ,0
Exp/Cntr=0.3,0.1

Type RM Length L Ch R = 1 ,46391   ,930,930,930
BEGIN DESCRIPTION:
Reedy Creek XS 38.0
END DESCRIPTION:
XS GIS Cut Line= 4
      2512691.68       826394.38      2511435.84       827373.07
      2510699.64       827373.07       2509911.5       828048.62
#Sta/Elev= 30
  3094.7   90.18  3545.9   85.73  3913.5      84  4082.6   81.53  4221.8   78.46
  4464.4   70.51    4494   68.67    4509      65  4533.6   66.56    4585   65.15
  4618.6   63.79  4654.1   60.46  4756.7   56.92  4988.1   56.61  4989.6   53.61
  5010.4   53.61  5011.9   56.61  5358.3   57.37  5511.9   62.02  5581.8   66.35
    5761   70.96  5797.2   70.66  5927.4   76.31    5950   75.19    5967   77.34
  6096.9   79.24  6131.1   81.39    6291   84.18  6402.3   87.64  6461.1   87.56
#Mann= 3 ,-1,0
  3094.7     .15       0  4988.1     .05       0  5011.9     .15       0
Bank Sta=4988.1,5011.9
XS Rating Curve= 0 ,0
Exp/Cntr=0.3,0.1