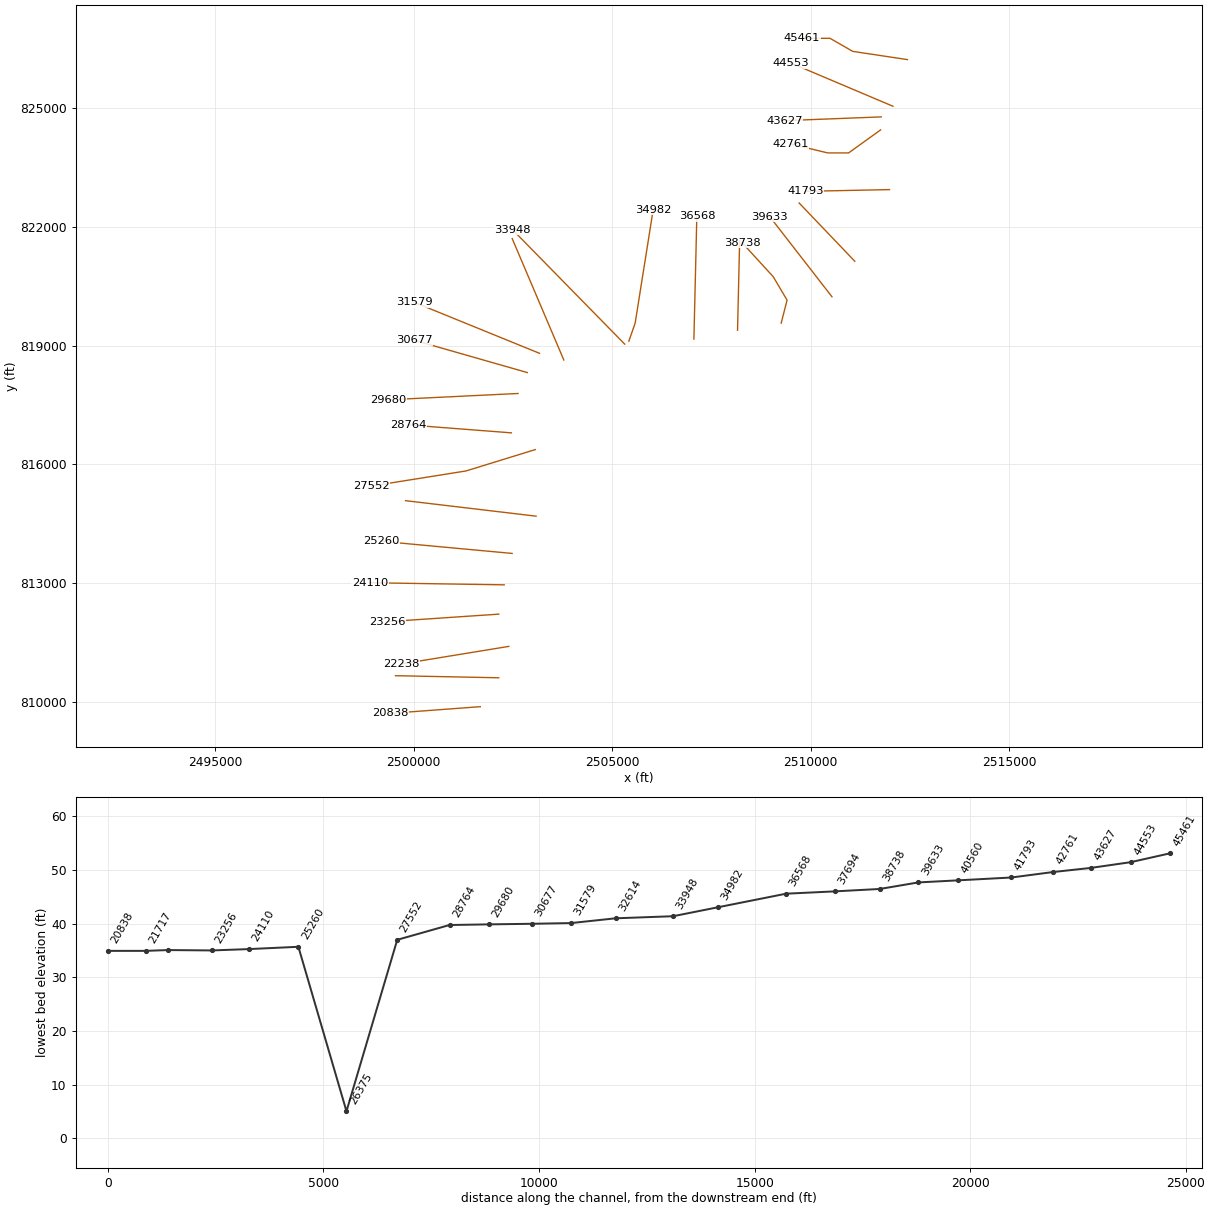
HEC-RAS study ReedyCreek.prj: S-34-32 over Reedy Creek

--- ReedyCreek.g05 (geometry) --- (continued)

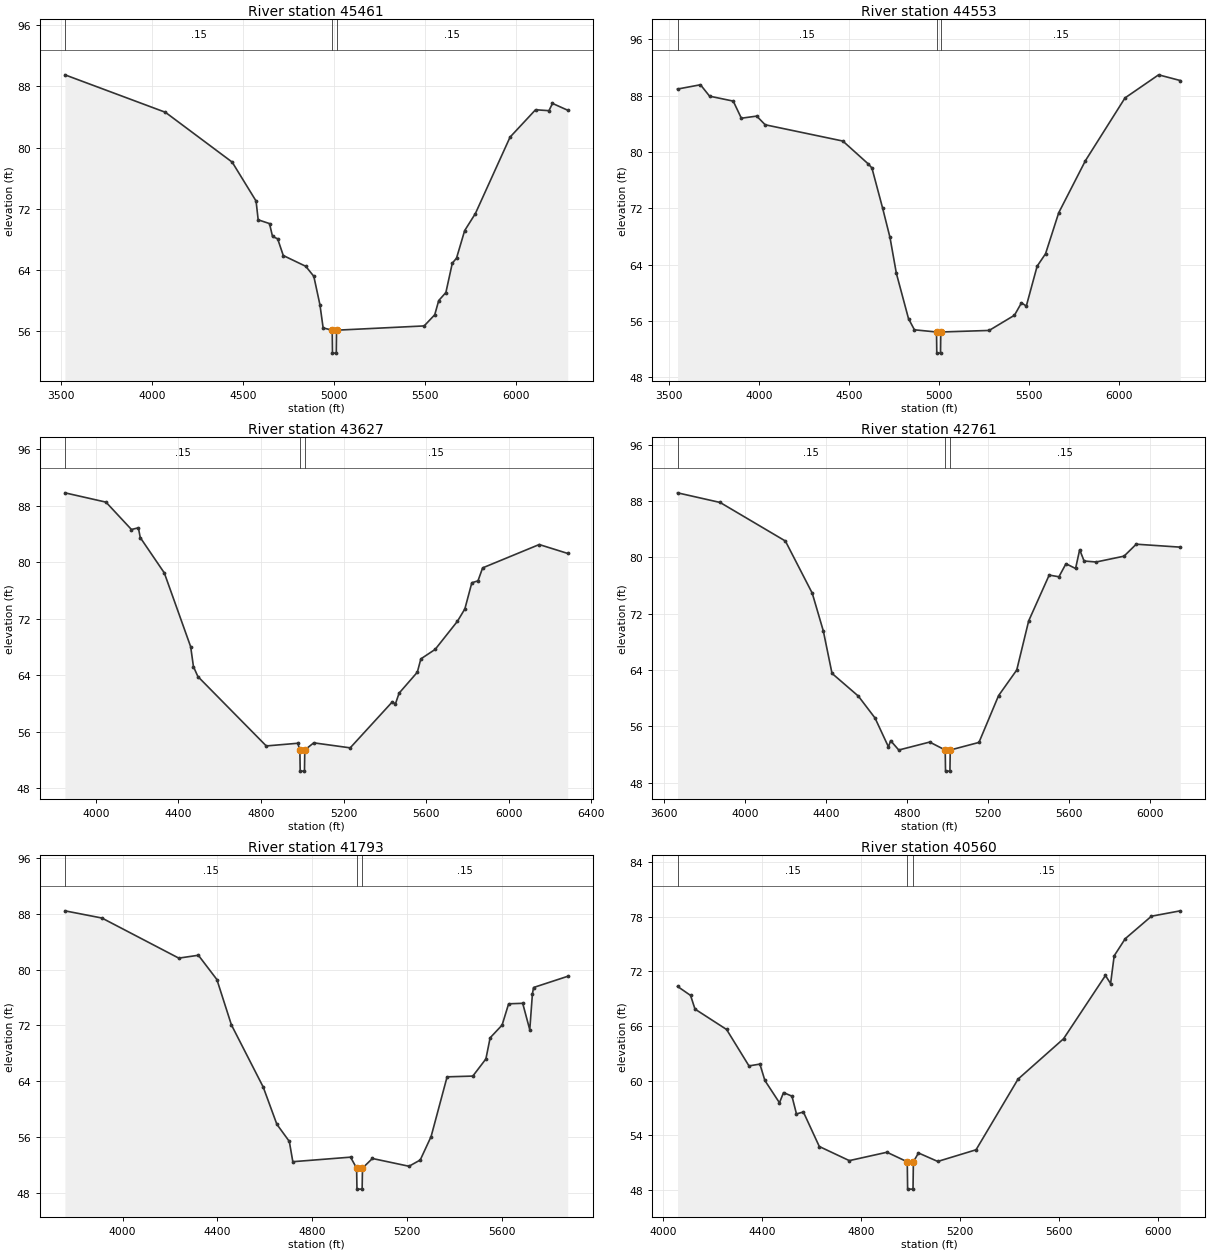
Type RM Length L Ch R = 1 ,45461   ,908,908,908
BEGIN DESCRIPTION:
Reedy Creek XS 37.0
END DESCRIPTION:
XS GIS Cut Line= 4
      2512440.57       826221.13       2511063.4         826429.
      2510491.77       826758.13      2509781.55       826758.13
#Sta/Elev= 30
  3519.4   89.51  4071.4   84.61  4438.4   78.09  4569.7      73  4581.3   70.54
  4643.5   70.05  4660.1   68.36  4688.2   68.06  4719.2   65.87  4842.7   64.46
    4887   63.15  4920.7   59.42  4938.2    56.4  4988.1    56.1  4989.6    53.1
  5010.4    53.1  5011.9    56.1  5493.4   56.66  5551.5   58.12  5573.4   59.98
  5612.7   61.03  5647.9   64.86  5671.2   65.53  5715.9   69.13  5774.8   71.36
  5965.3   81.36  6105.4   84.94  6179.1   84.82  6198.5   85.77    6282   84.88
#Mann= 3 ,-1,0
  3519.4     .15       0  4988.1     .05       0  5011.9     .15       0
Bank Sta=4988.1,5011.9
XS Rating Curve= 0 ,0
Exp/Cntr=0.3,0.1

Type RM Length L Ch R = 1 ,44553   ,926,926,926
BEGIN DESCRIPTION:
Reedy Creek XS 36.0
END DESCRIPTION:
XS GIS Cut Line= 2
      2512076.75       825043.22      2509504.37       826134.53
#Sta/Elev= 30
  3548.6   88.95  3676.2   89.56  3726.8   87.94  3858.3   87.24  3903.4   84.81
  3988.7   85.11  4035.8   83.88  4467.4   81.57  4607.9   78.34    4629   77.75
  4688.8   72.02  4729.5   67.88    4765   62.78  4832.5   56.35  4865.3   54.77
  4988.1   54.46  4989.6   51.46  5010.4   51.46  5011.9   54.46  5280.6   54.68
  5421.4   56.84  5460.3    58.6  5487.1   58.14  5547.3    63.8  5594.1   65.57
  5667.3   71.39  5816.1    78.8  6035.7   87.69  6222.4   90.97  6342.9   90.16
#Mann= 3 ,-1,0
  3548.6     .15       0  4988.1     .05       0  5011.9     .15       0
Bank Sta=4988.1,5011.9
XS Rating Curve= 0 ,0
Exp/Cntr=0.3,0.1

Type RM Length L Ch R = 1 ,43627   ,866,866,866
BEGIN DESCRIPTION:
Reedy Creek XS 35.0
END DESCRIPTION:
XS GIS Cut Line= 2
      2511782.25       824774.71      2509348.51       824679.44
#Sta/Elev= 30
  3849.9   89.84  4048.8   88.52  4172.1   84.64  4205.7   84.88  4214.8    83.5
  4331.3   78.49    4459   68.03  4472.5   65.21  4493.9    63.8  4825.3   53.96
  4977.7   54.34  4988.1   53.39  4989.6   50.39  5010.4   50.39  5011.9   53.39
  5055.4    54.4  5231.9   53.69  5436.6   60.23  5450.6   59.89  5468.7   61.44
    5557   64.41  5574.2    66.3  5643.6   67.65  5751.3   71.63  5787.3   73.38
  5821.1   77.09  5850.9   77.36  5873.4    79.2  6147.6   82.51  6285.5   81.25
#Mann= 3 ,-1,0
  3849.9     .15       0  4988.1     .05       0  5011.9     .15       0
Bank Sta=4988.1,5011.9
XS Rating Curve= 0 ,0
Exp/Cntr=0.3,0.1

Type RM Length L Ch R = 1 ,42761   ,968,968,968
BEGIN DESCRIPTION:
Reedy Creek XS 34.0
END DESCRIPTION:
XS GIS Cut Line= 4
      2511764.94       824445.57      2510959.47       823865.29
      2510431.14       823865.29      2509495.72       824090.48
#Sta/Elev= 30
  3665.4   89.18  3875.8   87.81  4198.2   82.33  4330.8   74.92  4385.6   69.54
  4428.5   63.52  4558.6   60.29  4641.1   57.17  4707.3   53.07  4717.9   53.96
  4758.2   52.63  4910.9   53.76  4987.6   52.63  4989.1   49.63  5010.9   49.63
  5012.4   52.63  5154.3   53.71  5251.1   60.36  5340.9      64  5399.8   70.98
  5501.1   77.49  5549.2   77.25    5584    79.1  5631.5   78.43  5651.7    81.1
  5673.5   79.49  5733.1   79.35  5870.8   80.18  5931.1   81.88  6148.6   81.46
#Mann= 3 ,-1,0
  3665.4     .15       0  4987.6     .05       0  5012.4     .15       0
Bank Sta=4987.6,5012.4
XS Rating Curve= 0 ,0
Exp/Cntr=0.3,0.1

Type RM Length L Ch R = 1 ,41793   ,1233,1233,1233
BEGIN DESCRIPTION:
Reedy Creek XS 33.0
END DESCRIPTION:
XS GIS Cut Line= 2
      2511990.18       822938.55      2509868.12       822895.24
#Sta/Elev= 30
  3756.2   88.39  3912.4   87.36  4236.8   81.63  4319.6   82.04  4397.7   78.57
    4459   72.09  4593.3    63.2  4650.9   57.88  4703.5   55.43  4718.3   52.53
    4962   53.18  4987.6   51.61  4989.1   48.61  5010.9   48.61  5012.4   51.61
  5054.3   52.99  5208.7   51.88  5256.1   52.77  5302.1   56.13  5369.6   64.66
  5478.2   64.77  5533.4   67.22  5551.3   70.24  5601.8   72.06  5629.4    75.1
  5688.8   75.17  5718.6   71.39  5729.8   76.52  5734.6   77.43  5878.7   79.03
#Mann= 3 ,-1,0
  3756.2     .15       0  4987.6     .05       0  5012.4     .15       0
Bank Sta=4987.6,5012.4
XS Rating Curve= 0 ,0
Exp/Cntr=0.3,0.1

Type RM Length L Ch R = 1 ,40560   ,927,927,927
BEGIN DESCRIPTION:
Reedy Creek XS 32.0
END DESCRIPTION:
XS GIS Cut Line= 2
       2511115.4       821128.33      2509712.28       822600.74
#Sta/Elev= 30
  4058.2   70.34    4111   69.35  4128.9   67.85  4256.7   65.61  4347.3   61.61
  4391.5   61.81  4411.6   60.01  4470.7   57.56    4487   58.68  4521.1   58.29
  4539.4   56.34  4567.4   56.55  4631.8   52.76  4753.2   51.21  4905.5   52.13
  4987.6   51.08  4989.1   48.08  5010.9   48.08  5012.4   51.08    5033   52.05
    5111   51.12  5265.9    52.4  5435.8   60.16  5619.9   64.59  5789.4   71.54
  5810.2   70.65  5824.7    73.7  5869.4   75.58  5975.5   78.05  6092.1   78.64
#Mann= 3 ,-1,0
  4058.2     .15       0  4987.6     .05       0  5012.4     .15       0
Bank Sta=4987.6,5012.4
XS Rating Curve= 0 ,0
Exp/Cntr=0.3,0.1

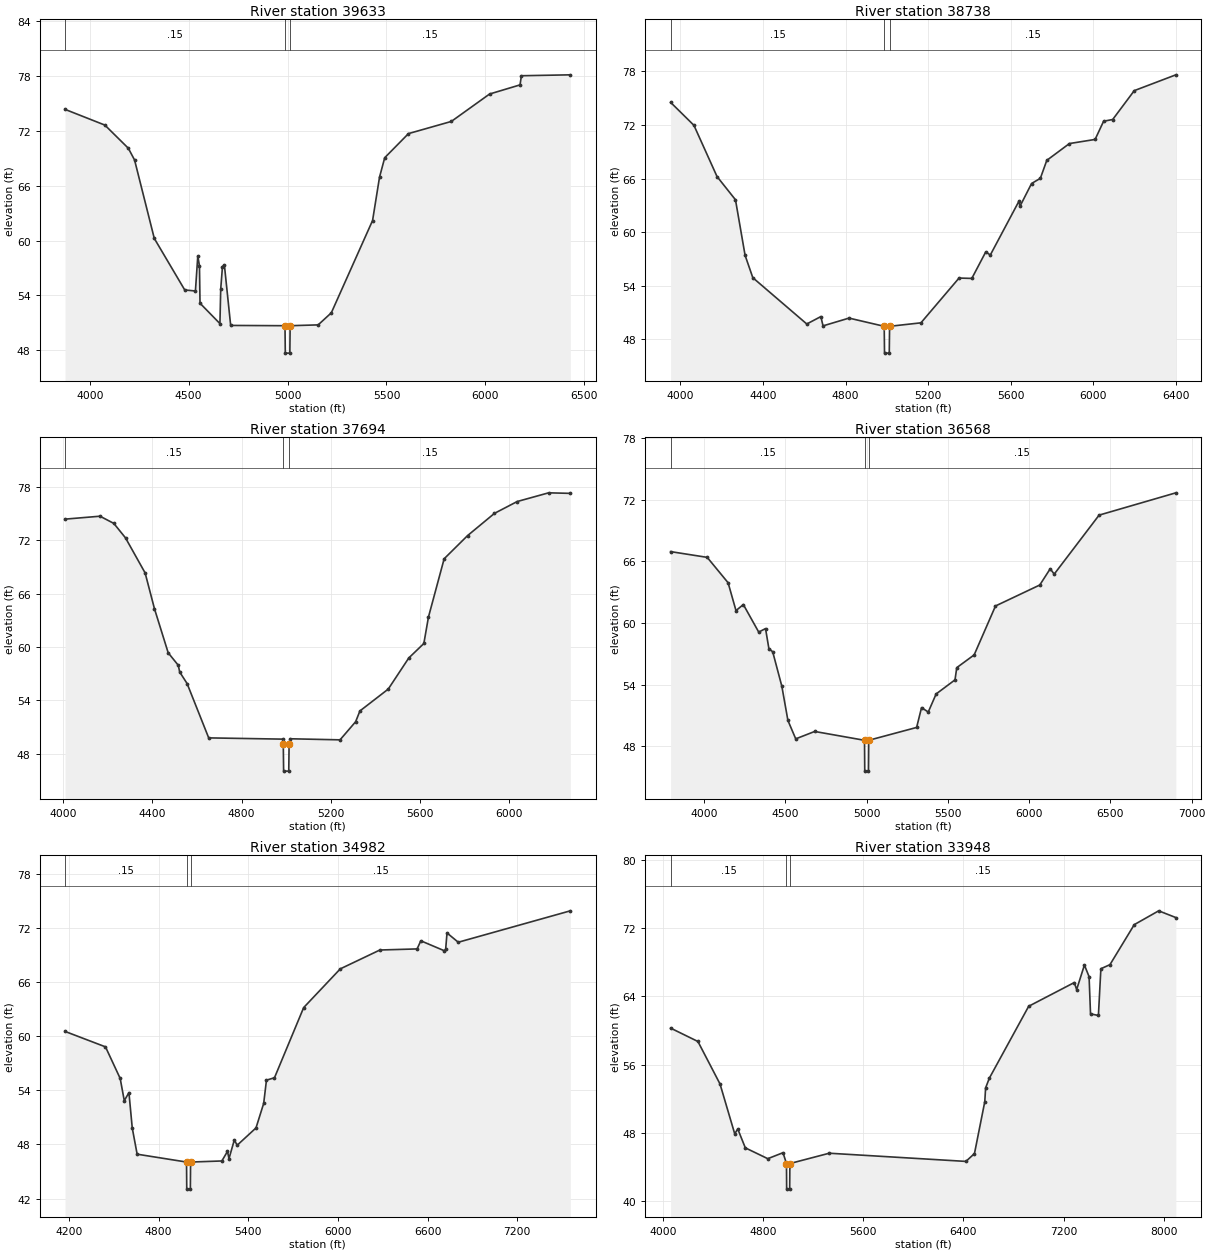
Type RM Length L Ch R = 1 ,39633   ,895,895,895
BEGIN DESCRIPTION:
Reedy Creek XS 31.0
END DESCRIPTION:
XS GIS Cut Line= 2
      2510540.01       820232.47      2508975.24       822251.87
#Sta/Elev= 30
  3874.9   74.36  4076.3   72.64  4194.7   70.11  4226.4   68.82  4326.1   60.24
  4480.1    54.6  4534.1   54.49  4546.1   58.33  4554.5   57.24  4557.3   53.15
    4658   50.92    4662   54.71  4670.8   57.15  4680.4   57.35  4712.3   50.72
    4987   50.69  4988.5   47.69  5011.5   47.69    5013   50.69  5154.7   50.78
  5221.2    52.1  5429.8    62.2    5465   66.95  5491.2   69.07  5611.4   71.71
    5828   73.04  6021.5   76.04  6175.5   77.04  6182.2   78.04  6429.6   78.14
#Mann= 3 ,-1,0
  3874.9     .15       0    4987     .05       0    5013     .15       0
Bank Sta=4987,5013
XS Rating Curve= 0 ,0
Exp/Cntr=0.3,0.1

Type RM Length L Ch R = 1 ,38738   ,1044,1044,1044
BEGIN DESCRIPTION:
Reedy Creek XS 30.0
END DESCRIPTION:
XS GIS Cut Line= 4
      2509260.72       819566.44      2509408.73       820147.93
      2509059.84       820739.98      2508277.46       821596.37
#Sta/Elev= 30
  3952.4   74.53  4065.4   71.96  4177.2   66.23  4266.6   63.63  4313.2   57.41
  4350.6   54.91    4612   49.73  4680.1   50.56  4690.7   49.52  4816.6   50.39
    4987   49.47  4988.5   46.47  5011.5   46.47    5013   49.47  5164.9   49.86
  5349.4   54.87  5411.3   54.83  5478.9    57.8  5500.9   57.45  5639.6   63.47
  5644.5    62.9  5700.8   65.45  5743.3   66.03  5774.5   68.04    5884   69.92
  6008.4   70.38  6049.7   72.42  6093.6   72.61  6198.1   75.84  6399.6   77.61
#Mann= 3 ,-1,0
  3952.4     .15       0    4987     .05       0    5013     .15       0
Bank Sta=4987,5013
XS Rating Curve= 0 ,0
Exp/Cntr=0.3,0.1

Type RM Length L Ch R = 1 ,37694   ,1126,1126,1126
BEGIN DESCRIPTION:
Reedy Creek XS 29.0
END DESCRIPTION:
XS GIS Cut Line= 2
      2508161.18       819386.75      2508214.05       821649.24
#Sta/Elev= 30
  4009.5   74.37  4166.1    74.7  4227.9   73.89  4280.3   72.26  4368.1   68.32
    4410   64.29  4471.5   59.33  4516.6   57.93    4523   57.17  4556.2   55.87
  4652.9   49.76  4983.8   49.62    4987   49.02  4988.5   46.02  5011.5   46.02
    5013   49.02  5017.5   49.66  5241.2   49.54  5311.1   51.58  5330.2   52.79
  5457.1   55.25  5549.1   58.75  5616.6   60.38  5637.2   63.35  5707.5   69.91
  5812.1   72.51  5932.9   75.02  6034.6   76.35  6175.4   77.33  6272.6   77.27
#Mann= 3 ,-1,0
  4009.5     .15       0    4987     .05       0    5013     .15       0
Bank Sta=4987,5013
XS Rating Curve= 0 ,0
Exp/Cntr=0.3,0.1

Type RM Length L Ch R = 1 ,36568   ,1586,1586,1586
BEGIN DESCRIPTION:
Reedy Creek XS 28.0
END DESCRIPTION:
XS GIS Cut Line= 2
      2507061.65       819164.66      2507135.66       822272.98
#Sta/Elev= 30
  3793.8   66.95  4019.1   66.39  4147.6   63.92  4196.2   61.21  4241.4    61.8
    4336   59.12    4378   59.46  4398.5   57.52  4422.1    57.2  4478.3   53.85
  4515.7   50.52  4563.8   48.73  4680.4   49.45    4987   48.59  4988.5   45.59
  5011.5   45.59    5013   48.59  5307.7   49.84    5338   51.77  5379.3   51.34
  5427.8    53.1  5543.9   54.47  5554.8   55.66  5661.8    56.9  5793.1   61.66
  6065.6    63.7  6129.8   65.28  6154.4   64.76  6430.6    70.5    6903   72.67
#Mann= 3 ,-1,0
  3793.8     .15       0    4987     .05       0    5013     .15       0
Bank Sta=4987,5013
XS Rating Curve= 0 ,0
Exp/Cntr=0.3,0.1

Type RM Length L Ch R = 1 ,34982   ,1034,1034,1034
BEGIN DESCRIPTION:
Reedy Creek XS 27.0
END DESCRIPTION:
XS GIS Cut Line= 3
       2505422.9       819111.79      2505581.51       819566.44
      2506036.12       822431.57
#Sta/Elev= 30
  4173.2   60.52  4443.9   58.81  4542.3   55.31  4569.7   52.85  4600.9   53.74
    4623   49.83  4655.8   46.92  4986.4   46.05  4987.9   43.05  5012.1   43.05
  5013.6   46.05  5222.9   46.17  5260.6   47.23  5270.7   46.43  5306.5    48.5
  5325.4   47.91  5451.5   49.83    5503   52.55  5521.5   55.12  5575.3   55.39
  5770.6   63.16  6015.7   67.45  6280.8   69.54  6530.1   69.66  6554.9   70.56
    6712   69.46  6721.2   69.61  6730.2   71.43  6805.6    70.4  7555.7   73.88
#Mann= 3 ,-1,0
  4173.2     .15       0  4986.4     .05       0  5013.6     .15       0
Bank Sta=4986.4,5013.6
XS Rating Curve= 0 ,0
Exp/Cntr=0.3,0.1

Type RM Length L Ch R = 1 ,33948   ,1334,1334,1334
BEGIN DESCRIPTION:
Reedy Creek XS 26.0
END DESCRIPTION:
XS GIS Cut Line= 2
      2505317.18       819037.83      2502494.34       821924.11
#Sta/Elev= 30
  4060.6   60.27  4278.9    58.7  4455.4   53.72  4572.8   47.88  4597.2   48.44
  4657.6   46.23    4837   44.96  4958.8   45.66  4986.4   44.39  4987.9   41.39
  5012.1   41.39  5013.6   44.39  5328.4    45.6  6420.1   44.64  6488.6   45.56
  6571.1   51.65  6577.6   53.26  6607.8   54.41  6921.8   62.83  7286.1   65.61
    7305   64.79  7367.1   67.66  7404.4    66.3  7415.9   61.94  7478.9   61.75
  7498.7   67.23  7571.3   67.71  7765.4    72.4  7960.6   74.02  8097.8   73.23
#Mann= 3 ,-1,0
  4060.6     .15       0  4986.4     .05       0  5013.6     .15       0
Bank Sta=4986.4,5013.6
XS Rating Curve= 0 ,0
Exp/Cntr=0.3,0.1

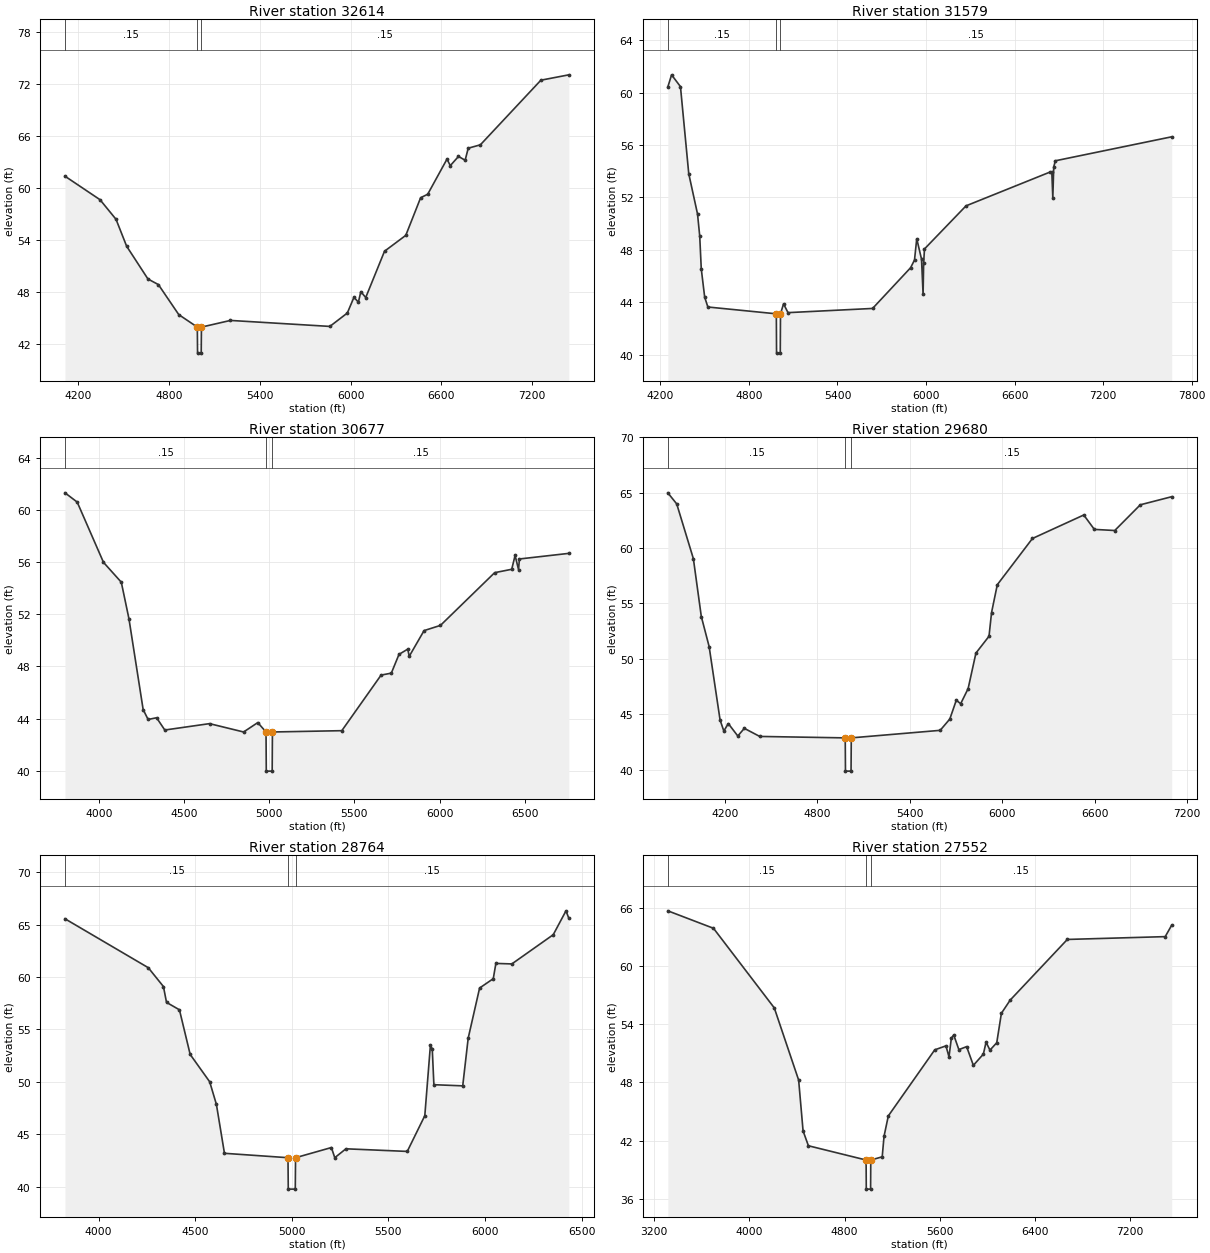
Type RM Length L Ch R = 1 ,32614   ,1035,1035,1035
BEGIN DESCRIPTION:
Reedy Creek XS 25.0
END DESCRIPTION:
XS GIS Cut Line= 2
      2503784.18        818636.1      2502483.76       821702.12
#Sta/Elev= 30
  4111.7    61.4  4343.3   58.69  4449.1   56.43  4519.1   53.33    4660   49.55
  4729.2    48.9  4863.8   45.44  4986.4      44  4987.9      41  5012.1      41
  5013.6      44  5205.3   44.77  5862.4   44.08  5977.7   45.62  6021.5   47.43
    6051   46.88  6067.2   48.09  6099.4   47.41  6223.7   52.75  6364.2   54.58
  6462.4   58.92  6509.1   59.32  6636.5   63.37  6658.5   62.62  6712.6   63.68
  6756.6   63.24  6776.9   64.63  6857.3   65.02  7257.1   72.47  7442.1   73.09
#Mann= 3 ,-1,0
  4111.7     .15       0  4986.4     .05       0  5013.6     .15       0
Bank Sta=4986.4,5013.6
XS Rating Curve= 0 ,0
Exp/Cntr=0.3,0.1

Type RM Length L Ch R = 1 ,31579   ,902,902,902
BEGIN DESCRIPTION:
Reedy Creek XS 24.0
END DESCRIPTION:
XS GIS Cut Line= 2
      2503171.02       818805.21      2500009.84       820095.06
#Sta/Elev= 30
  4250.6   60.42  4276.1   61.35  4336.3   60.45  4392.5    53.8  4451.9   50.73
  4466.7   49.06  4477.3   46.54  4500.4   44.38    4522   43.63  4985.9   43.11
  4987.4   40.11  5012.6   40.11  5014.1   43.11  5034.8   43.87    5065    43.2
  5638.1   43.52  5895.9   46.63  5922.2   47.22  5937.3   48.84  5969.7   47.28
  5980.3   44.59    5984   46.96  5989.7   48.06  6271.2   51.35  6842.8   53.94
  6852.5   53.94  6859.3   51.95  6865.5   54.32  6876.6   54.79  7664.8   56.62
#Mann= 3 ,-1,0
  4250.6     .15       0  4985.9     .05       0  5014.1     .15       0
Bank Sta=4985.9,5014.1
XS Rating Curve= 0 ,0
Exp/Cntr=0.3,0.1

Type RM Length L Ch R = 1 ,30677   ,997,997,997
BEGIN DESCRIPTION:
Reedy Creek XS 23.0
END DESCRIPTION:
XS GIS Cut Line= 2
      2502864.36        818318.9      2500020.38       819132.98
#Sta/Elev= 30
  3800.9   61.31  3872.6    60.6    4027   55.98  4131.5   54.46  4176.4   51.66
  4259.8    44.7  4288.8   43.94  4338.7   44.07  4386.9   43.13  4649.4   43.62
  4849.5   42.98  4932.8    43.7  4981.2   42.98  4982.7   39.98  5017.3   39.98
  5018.8   42.98  5426.1   43.08  5656.7   47.34  5716.8   47.49  5761.9   48.93
  5813.3   49.33  5821.9   48.78    5909   50.75  6005.3   51.15  6323.4   55.19
  6423.6   55.45  6443.4   56.51  6463.8   55.42  6468.7   56.24  6759.1   56.67
#Mann= 3 ,-1,0
  3800.9     .15       0  4981.2     .05       0  5018.8     .15       0
Bank Sta=4981.2,5018.8
XS Rating Curve= 0 ,0
Exp/Cntr=0.3,0.1

Type RM Length L Ch R = 1 ,29680   ,916,916,916
BEGIN DESCRIPTION:
Reedy Creek XS 22.0
END DESCRIPTION:
XS GIS Cut Line= 2
      2502631.83       817790.27      2499364.87       817631.68
#Sta/Elev= 30
  3828.7   64.98  3886.5   63.98  3994.6   59.04  4046.1   53.82  4096.9   51.11
    4168   44.48  4192.3   43.49  4221.4   44.16    4283   43.04  4325.3   43.73
  4425.3      43  4980.4   42.87  4981.9   39.87  5018.1   39.87  5019.6   42.87
  5596.7   43.55  5659.2   44.57  5701.4   46.27  5729.6   45.95    5778   47.31
  5828.7   50.52  5913.7   52.04  5930.2   54.18  5967.5   56.69  6195.6   60.86
  6528.7   62.98  6597.4   61.68  6729.9   61.58  6895.8    63.9  7099.5   64.63
#Mann= 3 ,-1,0
  3828.7     .15       0  4980.4     .05       0  5019.6     .15       0
Bank Sta=4980.4,5019.6
XS Rating Curve= 0 ,0
Exp/Cntr=0.3,0.1

Type RM Length L Ch R = 1 ,28764   ,1212,1212,1212
BEGIN DESCRIPTION:
Reedy Creek XS 21.0
END DESCRIPTION:
XS GIS Cut Line= 2
      2502462.63       816796.46      2499861.78       816997.34
#Sta/Elev= 30
  3825.9   65.56  4257.1   60.89  4335.6   59.09  4351.5   57.58  4418.4   56.87
    4474   52.61    4575      50  4609.8   47.84  4651.5   43.17  4980.4   42.75
  4981.9   39.75  5018.1   39.75  5019.6   42.75  5205.1   43.72  5222.6   42.75
  5280.3    43.6  5597.9   43.35  5688.7   46.76  5717.9   53.53  5727.4    53.1
  5735.7   49.72    5885   49.61  5913.3   54.16  5972.4   58.95  6043.1   59.84
  6056.7    61.3  6139.3   61.25  6353.6   64.04  6419.6   66.32  6434.5    65.6
#Mann= 3 ,-1,0
  3825.9     .15       0  4980.4     .05       0  5019.6     .15       0
Bank Sta=4980.4,5019.6
XS Rating Curve= 0 ,0
Exp/Cntr=0.3,0.1

Type RM Length L Ch R = 1 ,27552   ,1177,1177,1177
BEGIN DESCRIPTION:
Reedy Creek XS 20.0
END DESCRIPTION:
XS GIS Cut Line= 3
      2503065.26       816373.56      2501320.81       815834.37
      2498942.04       815453.76
#Sta/Elev= 30
  3313.8   65.68  3697.7   63.88  4208.8   55.67  4413.4   48.23  4450.6   42.99
  4495.4   41.46  4980.4   39.99  4981.9   36.99  5018.1   36.99  5019.6   39.99
  5115.7   40.32  5131.1   42.44  5167.1   44.54  5557.4   51.35  5651.6   51.76
    5677   50.62  5696.9   52.56  5716.9   52.88    5760   51.37  5825.2   51.68
  5881.8   49.75    5966   50.91  5988.5   52.14  6021.4   51.32  6078.3   52.08
  6117.5   55.12  6191.5   56.48  6671.6   62.73  7494.3   63.02  7548.7    64.2
#Mann= 3 ,-1,0
  3313.8     .15       0  4980.4     .05       0  5019.6     .15       0
Bank Sta=4980.4,5019.6
XS Rating Curve= 0 ,0
Exp/Cntr=0.3,0.1

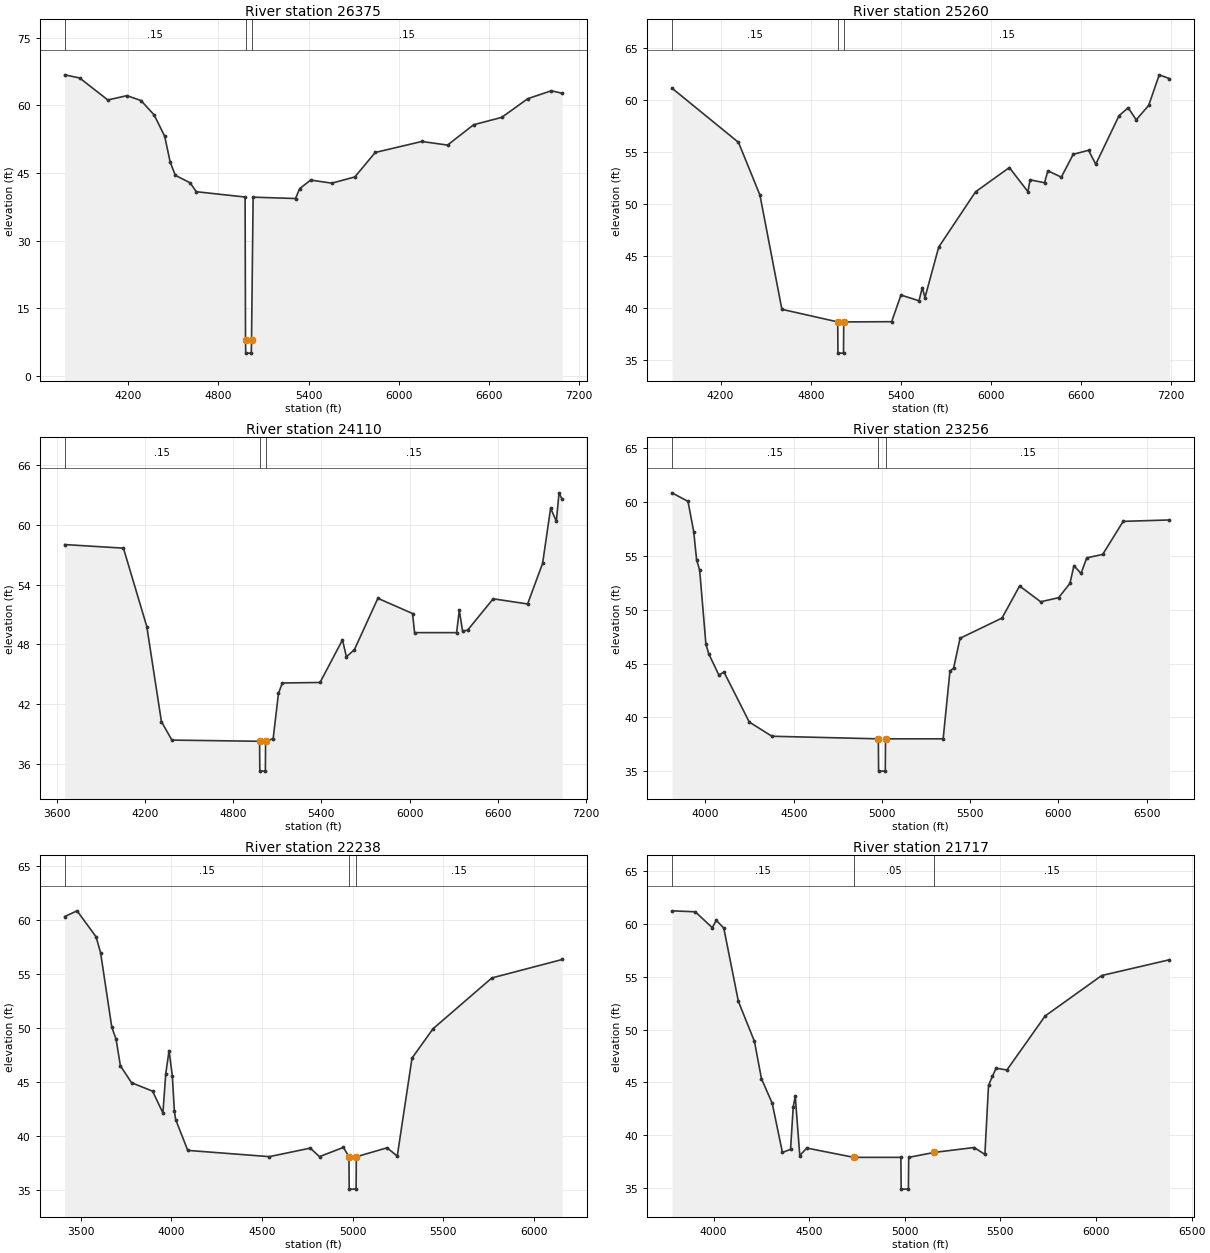
Type RM Length L Ch R = 1 ,26375   ,1115,1115,1115
BEGIN DESCRIPTION:
Reedy Creek XS 19.0
END DESCRIPTION:
XS GIS Cut Line= 2
       2503086.4       814692.54      2499798.39       815083.72
#Sta/Elev= 30
  3776.4   66.79  3876.3   66.09  4063.7   61.21  4190.4   62.17  4284.1   61.09
  4371.9   57.89  4441.8   53.19  4478.6   47.43  4513.1   44.49  4611.1   42.83
  4652.7   40.85  4977.2   39.67    4980    8.03  4981.5    5.03  5018.5    5.03
    5020    8.03  5030.6   39.64  5312.7   39.34  5340.2   41.53  5413.3   43.43
  5554.2   42.75  5707.6   44.13  5843.2   49.56  6153.4      52  6324.5    51.2
    6498   55.71  6685.2   57.35  6858.6    61.5  7014.8   63.25  7087.6    62.7
#Mann= 3 ,-1,0
  3776.4     .15       0    4980     .05       0    5020     .15       0
Bank Sta=4980,5020
XS Rating Curve= 0 ,0
Exp/Cntr=0.3,0.1

Type RM Length L Ch R = 1 ,25260   ,1150,1150,1150
BEGIN DESCRIPTION:
Reedy Creek XS 18.0
END DESCRIPTION:
XS GIS Cut Line= 2
      2502483.76        813751.6      2499185.18        814058.2
#Sta/Elev= 30
  3876.3   61.15  4319.3   55.94    4462   50.88  4608.2    39.9    4980   38.69
  4981.5   35.69  5018.5   35.69    5020   38.69    5339   38.71  5401.2   41.27
  5521.1   40.72  5543.3   41.99    5561   41.03  5652.5   45.88  5897.7   51.19
  6122.7   53.52  6246.2   51.21    6261   52.34  6357.1   52.06  6379.1   53.21
  6468.9    52.6  6547.9   54.79  6650.2   55.18  6698.1   53.84  6852.9    58.5
  6913.9   59.27  6967.4   58.11  7050.4   59.49  7120.8   62.43  7189.1   62.07
#Mann= 3 ,-1,0
  3876.3     .15       0    4980     .05       0    5020     .15       0
Bank Sta=4980,5020
XS Rating Curve= 0 ,0
Exp/Cntr=0.3,0.1

Type RM Length L Ch R = 1 ,24110   ,854,854,854
BEGIN DESCRIPTION:
Reedy Creek XS 17.0
END DESCRIPTION:
XS GIS Cut Line= 2
      2502282.86       812958.66      2498899.77       813011.52
#Sta/Elev= 30
    3654   58.03  4053.7   57.67  4212.5   49.79    4312   40.24  4383.2   38.38
  4979.6   38.26  4981.1   35.26  5018.9   35.26  5020.4   38.26  5071.7   38.52
    5108   43.07  5134.1   44.12  5390.7   44.17  5543.2   48.45    5570   46.75
  5624.4   47.47    5784   52.63  6019.9    51.1  6033.6   49.18  6319.5   49.18
  6337.6   51.42  6360.2   49.34  6394.2   49.43  6568.2   52.58  6802.2   52.06
  6904.2   56.14  6958.7   61.68  6997.8   60.38    7016   63.23  7037.5   62.56
#Mann= 3 ,-1,0
    3654     .15       0  4979.6     .05       0  5020.4     .15       0
Bank Sta=4979.6,5020.4
XS Rating Curve= 0 ,0
Exp/Cntr=0.3,0.1

Type RM Length L Ch R = 1 ,23256   ,1018,1018,1018
BEGIN DESCRIPTION:
Reedy Creek XS 16.0
END DESCRIPTION:
XS GIS Cut Line= 2
      2502145.46       812218.59       2499333.2       812028.29
#Sta/Elev= 30
  3810.4   60.86  3901.2   60.07  3933.7   57.25  3949.8   54.66  3967.5   53.66
  4002.6   46.81  4019.2   45.89  4076.4   43.93  4104.9   44.22  4248.4   39.57
  4376.8   38.25  4979.6   38.01  4981.1   35.01  5018.9   35.01  5020.4   38.01
  5346.8   38.01  5385.2    44.3  5406.2   44.58  5442.5   47.35  5680.3   49.23
  5779.8   52.21  5899.4   50.74  6000.9   51.12    6065   52.45  6087.9    54.1
  6127.8   53.37  6160.3   54.82  6250.6   55.14  6366.6   58.21  6629.1   58.34
#Mann= 3 ,-1,0
  3810.4     .15       0  4979.6     .05       0  5020.4     .15       0
Bank Sta=4979.6,5020.4
XS Rating Curve= 0 ,0
Exp/Cntr=0.3,0.1

Type RM Length L Ch R = 1 ,22238   ,521,521,521
BEGIN DESCRIPTION:
Reedy Creek XS 15.0
END DESCRIPTION:
XS GIS Cut Line= 2
      2502399.18       811404.51      2499692.67       810960.47
#Sta/Elev= 30
  3412.5   60.34  3480.9   60.87  3585.7   58.46  3610.7   56.97  3672.2   50.09
  3695.9   48.98  3719.7   46.51  3781.2   44.94    3897   44.16  3954.1   42.14
  3969.8   45.78    3988   47.92  4005.9   45.59  4017.3   42.33  4024.2   41.53
  4091.1   38.67  4541.1   38.09  4766.2   38.88  4817.3   38.09  4949.3   38.95
  4979.6   38.08  4981.1   35.08  5018.9   35.08  5020.4   38.08  5189.7   38.91
  5245.9   38.14  5327.3   47.22    5443   49.94  5767.4   54.65  6155.2   56.36
#Mann= 3 ,-1,0
  3412.5     .15       0  4979.6     .05       0  5020.4     .15       0
Bank Sta=4979.6,5020.4
XS Rating Curve= 0 ,0
Exp/Cntr=0.3,0.1

Type RM Length L Ch R = 1 ,21717   ,879,879,879
BEGIN DESCRIPTION:
Reedy Creek XS 14.0
END DESCRIPTION:
XS GIS Cut Line= 2
      2502145.45       810611.58      2499544.59       810664.44
#Sta/Elev= 30
  3782.7   61.21  3904.5   61.12  3993.4   59.62  4014.6   60.31  4053.7   59.58
  4129.8   52.67    4214   48.88  4250.6   45.36  4306.8   43.04  4360.3   38.39
  4402.8   38.69  4416.7   42.69  4427.3   43.72    4451    38.1  4487.4   38.81
  4733.7   37.93  4979.6   37.93  4981.1   34.93  5018.9   34.93  5020.4   37.93
  5155.2    38.4  5362.7   38.86  5418.8   38.21  5437.8   44.72  5458.2   45.59
  5477.4   46.35    5534   46.18  5733.8   51.28  6029.5    55.1  6384.1   56.59
#Mann= 3 ,-1,0
  3782.7     .15       0  4733.7     .05       0  5155.2     .15       0
Bank Sta=4733.7,5155.2
XS Rating Curve= 0 ,0
Exp/Cntr=0.3,0.1

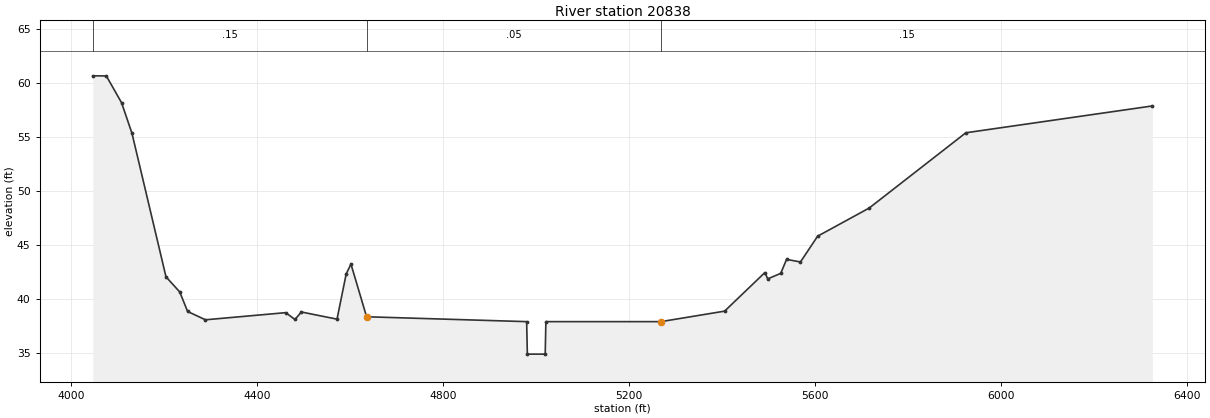
Type RM Length L Ch R = 1 ,20838   ,879,879,879
BEGIN DESCRIPTION:
Reedy Creek XS 13.0
END DESCRIPTION:
XS GIS Cut Line= 2
      2501680.27       809882.08      2499407.16       809712.92
#Sta/Elev= 30
    4046   60.63  4075.2   60.62    4108   58.14  4130.4   55.31  4203.5   42.07
  4233.1   40.67    4250   38.87  4288.4    38.1  4460.9   38.76  4480.9   38.13
  4494.7   38.82  4571.4   38.16  4591.2   42.35  4601.4   43.24    4635   38.38
  4979.3   37.93  4980.8   34.93  5019.2   34.93  5020.7   37.93  5268.1   37.93
  5405.1    38.9  5491.7   42.46  5497.9   41.88  5525.9   42.39  5538.4   43.68
  5568.3   43.44  5605.2   45.82  5716.1   48.42    5924   55.37  6325.4   57.85
#Mann= 3 ,-1,0
    4046     .15       0    4635     .05       0  5268.1     .15       0
Bank Sta=4635,5268.1
XS Rating Curve= 0 ,0
Exp/Cntr=0.3,0.1