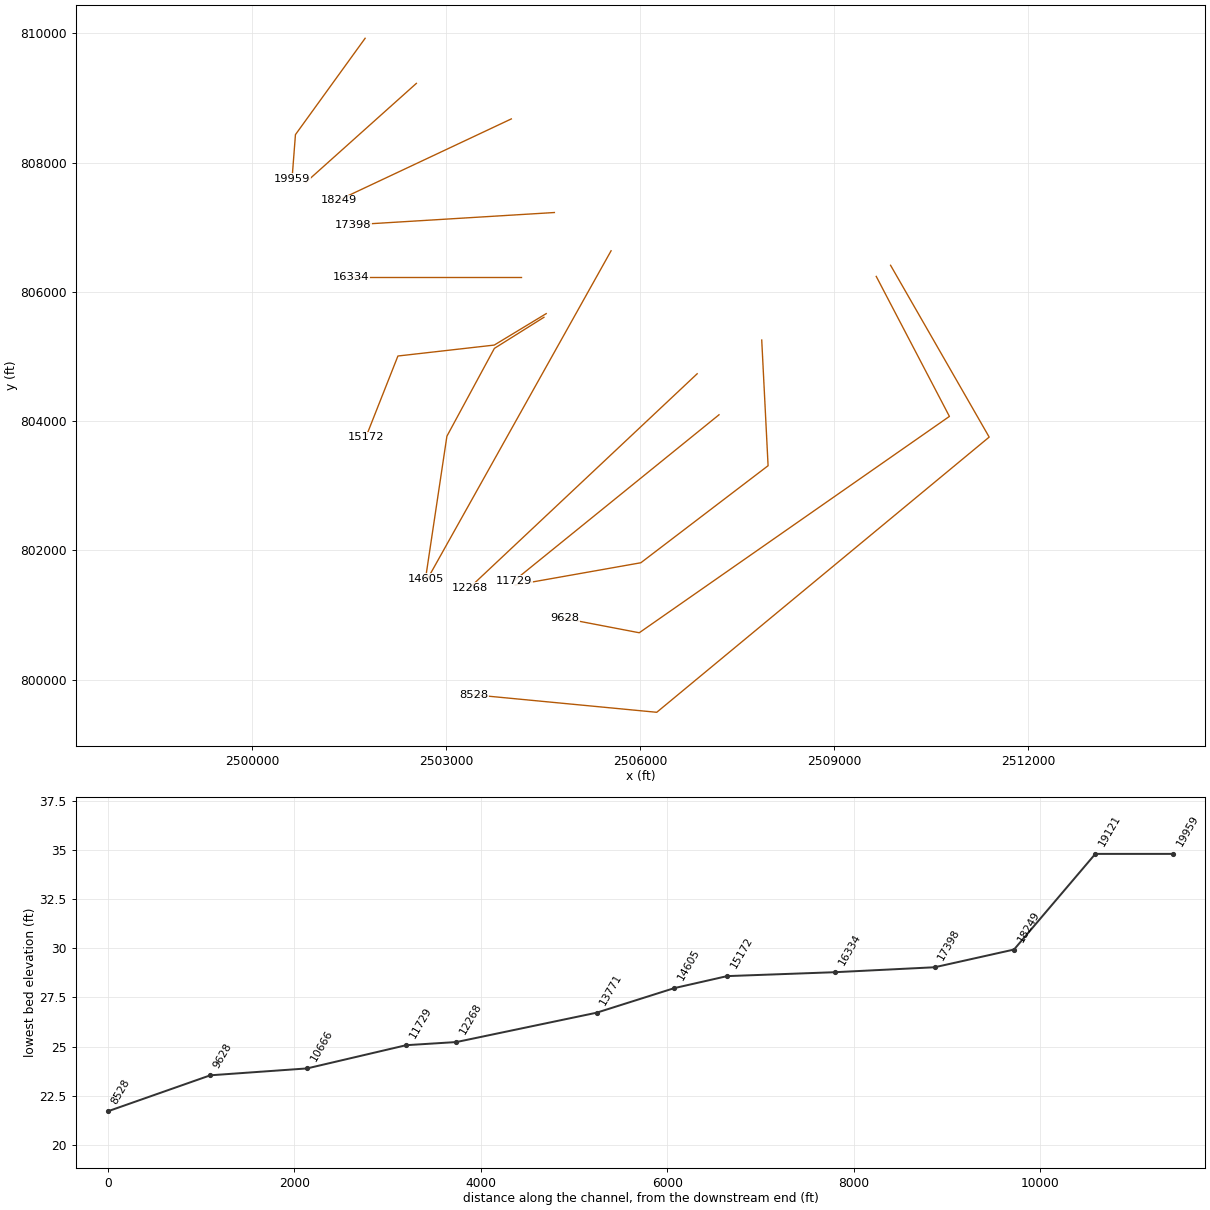
HEC-RAS study ReedyCreek.prj: S-34-32 over Reedy Creek

--- ReedyCreek.g05 (geometry) --- (continued)

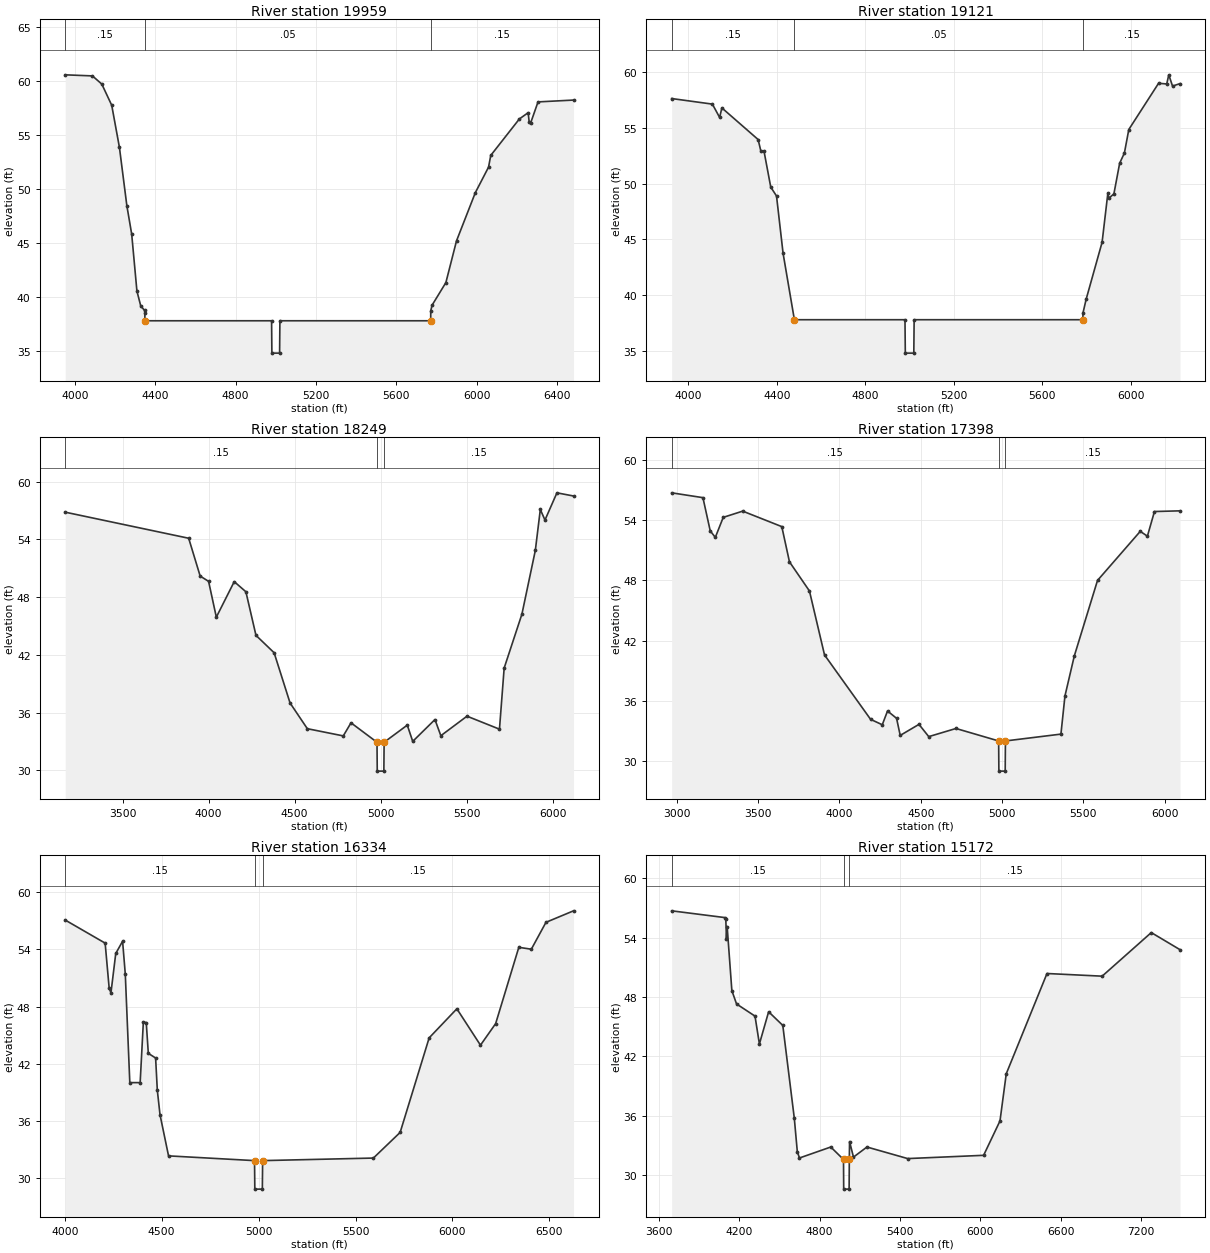
Type RM Length L Ch R = 1 ,19959   ,838,838,838
BEGIN DESCRIPTION:
Reedy Creek XS 12.0
END DESCRIPTION:
XS GIS Cut Line= 3
      2501743.68       809924.33      2500665.32       808433.65
      2500612.45       807746.42
#Sta/Elev= 30
  3952.5   60.59    4088   60.49  4134.6   59.73  4183.9   57.77  4222.2   53.87
  4259.2   48.46  4283.3   45.82  4309.3   40.54  4328.3   39.17  4347.2   38.75
  4348.8   38.51    4349   37.79  4979.3   37.79  4980.8   34.79  5019.2   34.79
  5020.7   37.79    5771   37.79  5771.2   38.71  5777.7   39.23  5846.5   41.33
  5899.4    45.2  5993.1   49.67  6058.7   52.03  6069.8   53.12  6212.1    56.5
  6255.8   57.08  6261.1    56.2  6268.5   56.14  6304.9   58.08  6481.6   58.25
#Mann= 3 ,-1,0
  3952.5     .15       0    4349     .05       0    5771     .15       0
Bank Sta=4349,5771
XS Rating Curve= 0 ,0
Exp/Cntr=0.3,0.1

Type RM Length L Ch R = 1 ,19121   ,872,872,872
BEGIN DESCRIPTION:
Reedy Creek XS 11.0
END DESCRIPTION:
XS GIS Cut Line= 2
      2502536.62       809226.56      2500823.88       807693.56
#Sta/Elev= 30
  3924.3   57.65  4108.4   57.15  4141.2   55.95  4151.3   56.81  4315.2   53.97
  4327.4   52.95  4341.6   52.95  4372.3    49.7  4398.4    48.9  4428.1   43.75
  4479.2   37.79  4979.3   37.79  4980.8   34.79  5019.2   34.79  5020.7   37.79
  5783.4   37.79  5784.4   38.41  5798.4   39.62  5870.6   44.74  5896.8   49.17
    5901    48.7    5924   49.09    5950   51.84  5971.5   52.76  5991.4   54.87
    6126   59.02  6162.9   58.96  6172.2   59.78  6189.1   58.77  6222.9   58.99
#Mann= 3 ,-1,0
  3924.3     .15       0  4479.2     .05       0  5783.4     .15       0
Bank Sta=4479.2,5783.4
XS Rating Curve= 0 ,0
Exp/Cntr=0.3,0.1

Type RM Length L Ch R = 1 ,18249   ,851,851,851
BEGIN DESCRIPTION:
Reedy Creek XS 10.0
END DESCRIPTION:
XS GIS Cut Line= 2
      2504006.24       808676.83      2501331.35       807418.68
#Sta/Elev= 30
  3166.2   56.84  3884.2   54.13    3951    50.2    4000   49.65    4045   45.93
  4149.1   49.62  4216.9   48.57  4275.5   44.04  4381.1   42.23  4473.8   37.01
  4574.2   34.34  4783.2   33.59  4828.2   34.95  4979.3   32.93  4980.8   29.93
  5019.2   29.93  5020.7   32.93  5155.4   34.71  5187.1   33.02  5316.3   35.29
  5350.6   33.61  5502.7   35.64  5691.5   34.29  5718.8   40.64    5822   46.24
    5900   52.86  5929.1   57.12  5956.1   56.02  6025.6   58.85  6122.2   58.52
#Mann= 3 ,-1,0
  3166.2     .15       0  4979.3     .05       0  5020.7     .15       0
Bank Sta=4979.3,5020.7
XS Rating Curve= 0 ,0
Exp/Cntr=0.3,0.1

Type RM Length L Ch R = 1 ,17398   ,1064,1064,1064
BEGIN DESCRIPTION:
Reedy Creek XS 9.0
END DESCRIPTION:
XS GIS Cut Line= 2
      2504672.24       807228.39      2501553.45       807038.09
#Sta/Elev= 30
  2969.3    56.7  3161.4   56.22  3206.3   52.92  3237.6   52.27  3286.2   54.26
  3405.9   54.88  3646.2   53.34  3693.3   49.84  3816.2   46.94  3908.9   40.58
    4192   34.18  4263.9   33.64  4296.1   35.01  4351.7   34.28  4374.1   32.58
  4489.4   33.68  4549.5   32.46  4716.9   33.27  4979.1   32.03  4980.6   29.03
  5019.4   29.03  5020.9   32.03    5362   32.71  5386.8   36.51  5444.2   40.48
  5586.9   47.99  5849.6   52.87  5893.5   52.39  5936.8   54.84  6093.9   54.91
#Mann= 3 ,-1,0
  2969.3     .15       0  4979.1     .05       0  5020.9     .15       0
Bank Sta=4979.1,5020.9
XS Rating Curve= 0 ,0
Exp/Cntr=0.3,0.1

Type RM Length L Ch R = 1 ,16334   ,1162,1162,1162
BEGIN DESCRIPTION:
Reedy Creek XS 8.0
END DESCRIPTION:
XS GIS Cut Line= 2
      2504154.18       806224.01      2501532.28       806224.01
#Sta/Elev= 30
  4002.6    57.1  4208.6   54.67  4229.3   49.94  4238.5   49.43  4263.3   53.58
  4298.6   54.87  4312.5   51.41  4335.8   39.99  4389.2   39.99  4405.6   46.35
  4420.6   46.31  4431.3   43.07  4468.9   42.58  4477.7   39.19  4491.6   36.61
  4535.6   32.28  4979.1   31.78  4980.6   28.78  5019.4   28.78  5020.9   31.78
  5592.2   32.05  5730.2   34.75  5879.8    44.7  6022.7   47.76  6144.5   43.93
  6222.8    46.2  6342.3   54.23  6406.8   54.03  6482.3   56.86  6624.5   58.07
#Mann= 3 ,-1,0
  4002.6     .15       0  4979.1     .05       0  5020.9     .15       0
Bank Sta=4979.1,5020.9
XS Rating Curve= 0 ,0
Exp/Cntr=0.3,0.1

Type RM Length L Ch R = 1 ,15172   ,567,567,567
BEGIN DESCRIPTION:
Reedy Creek XS 7.0
END DESCRIPTION:
XS GIS Cut Line= 4
      2504545.45        805663.7       2503741.9       805177.34
      2502251.18       805008.18      2501754.26       803750.01
#Sta/Elev= 30
  3696.4   56.73  4091.4   56.05  4100.2   55.87  4105.2   53.91  4110.3   55.14
  4145.4   48.66  4180.4   47.31  4318.1   46.08  4350.9   43.26  4419.7   46.52
  4525.4   45.14  4611.3   35.75  4633.7   32.37  4649.9   31.73  4883.4   32.84
  4978.3   31.58  4979.8   28.58  5020.2   28.58  5021.7   31.58  5023.5   33.39
  5052.7   31.82  5153.3   32.84  5457.1   31.67  6023.6      32  6145.8   35.48
  6192.5   40.25  6496.4   50.39  6907.9   50.12  7274.5   54.53  7488.7    52.8
#Mann= 3 ,-1,0
  3696.4     .15       0  4978.3     .05       0  5021.7     .15       0
Bank Sta=4978.3,5021.7
XS Rating Curve= 0 ,0
Exp/Cntr=0.3,0.1

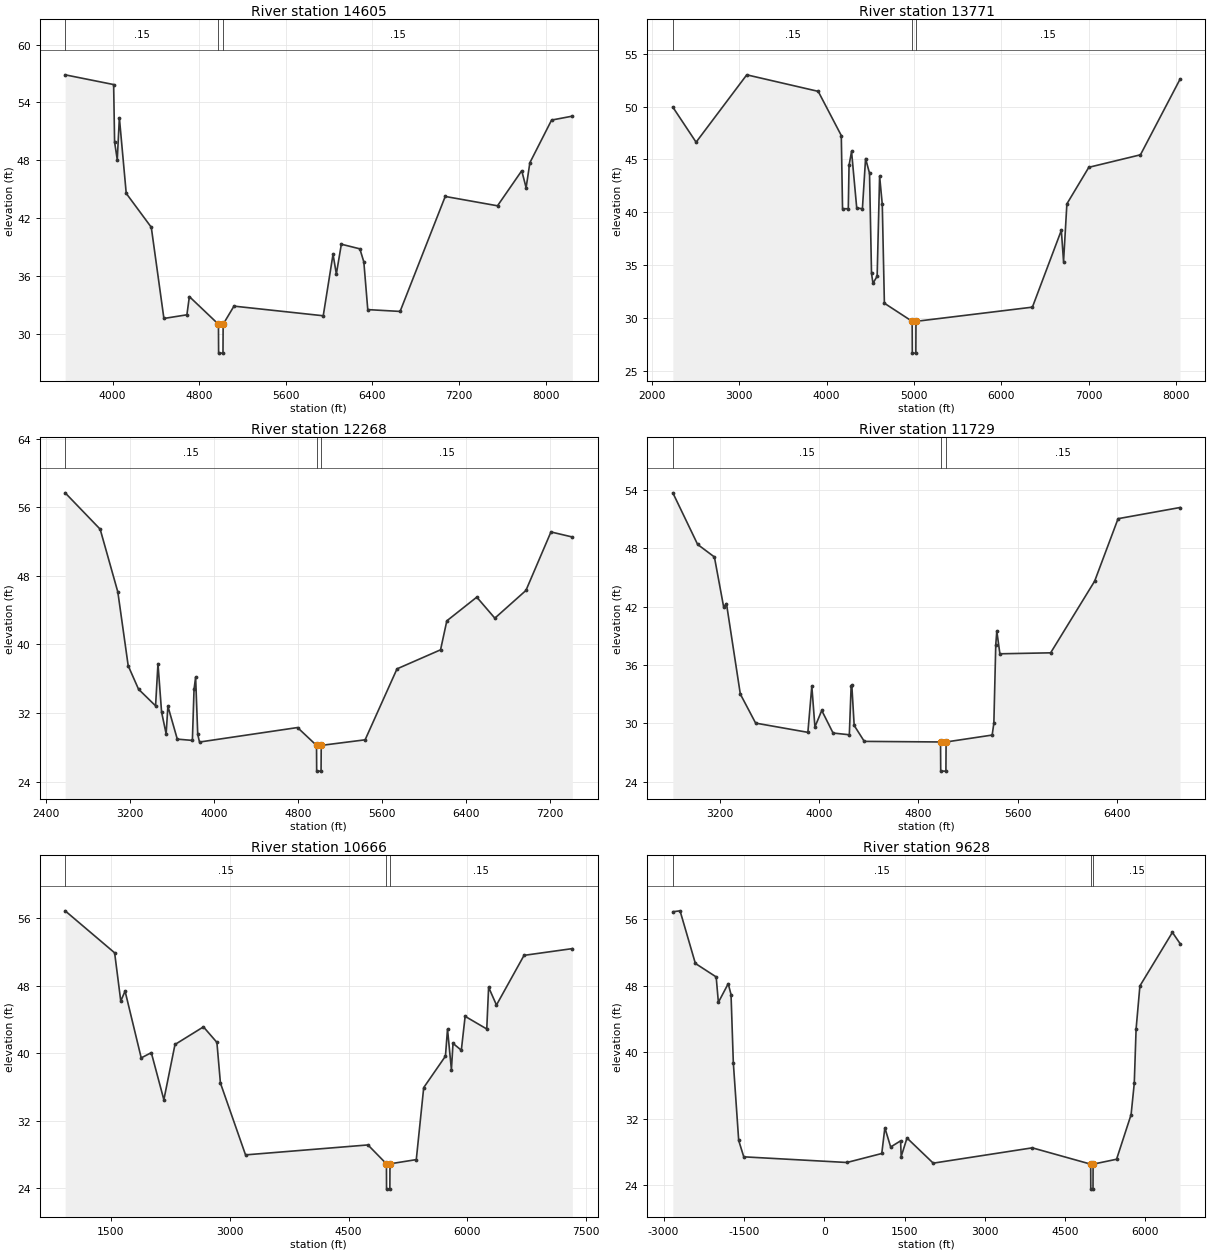
Type RM Length L Ch R = 1 ,14605   ,834,834,834
BEGIN DESCRIPTION:
Reedy Creek  XS 6.5
END DESCRIPTION:
XS GIS Cut Line= 4
      2504510.91       805607.25      2503743.76       805126.16
      2503009.14       803767.44      2502677.59       801557.08
#Sta/Elev= 30
  3562.3   56.87  4010.2   55.86    4019   49.89  4043.6   48.06  4063.1   52.41
  4126.5   44.56  4357.9   41.04  4474.5   31.57  4686.9   31.95  4709.7   33.84
  4978.3   30.97  4979.8   27.97  5020.2   27.97  5021.7   30.97  5121.7   32.85
  5946.3   31.85  6036.7   38.23  6067.4   36.19  6113.6   39.28  6284.5    38.8
  6321.3   37.44  6357.6   32.49  6656.2    32.3  7073.1   44.24    7556   43.27
  7779.9   46.91  7820.2   45.15  7854.9   47.74  8055.4   52.17  8247.5   52.58
#Mann= 3 ,-1,0
  3562.3     .15       0  4978.3     .05       0  5021.7     .15       0
Bank Sta=4978.3,5021.7
XS Rating Curve= 0 ,0
Exp/Cntr=0.3,0.1

Type RM Length L Ch R = 1 ,13771   ,1503,1503,1503
BEGIN DESCRIPTION:
Reedy Creek XS 6.0
END DESCRIPTION:
XS GIS Cut Line= 2
      2505549.77        806636.3      2502716.38       801572.15
#Sta/Elev= 30
  2240.1   49.94  2506.2   46.63  3085.8   52.99  3903.2   51.43  4167.3   47.26
  4181.6   40.35  4247.3   40.35    4256   44.44  4284.7   45.76  4343.9   40.42
  4408.9   40.35  4445.1   45.09  4490.3    43.7  4513.1   34.24  4529.8   33.31
  4577.5   33.98  4605.7   43.43  4636.2   40.76  4660.4   31.43  4978.3   29.72
  4979.8   26.72  5020.2   26.72  5021.7   29.72  6353.8   31.06  6684.7   38.31
  6710.1   35.36  6748.3   40.81  6999.2   44.26  7589.8   45.44    8043   52.58
#Mann= 3 ,-1,0
  2240.1     .15       0  4978.3     .05       0  5021.7     .15       0
Bank Sta=4978.3,5021.7
XS Rating Curve= 0 ,0
Exp/Cntr=0.3,0.1

Type RM Length L Ch R = 1 ,12268   ,539,539,539
BEGIN DESCRIPTION:
Reedy Creek XS 5.0
END DESCRIPTION:
XS GIS Cut Line= 2
      2506881.94       804733.32      2503361.33       801424.15
#Sta/Elev= 30
  2583.1   57.67  2916.6   53.43  3084.9   46.11  3183.7   37.51  3282.2   34.78
  3444.5   32.84  3467.3   37.76  3501.7   32.12  3545.1   29.57  3561.8    32.8
  3651.3   28.96  3795.1   28.81  3810.8   34.76  3825.9   36.18    3846   29.53
  3862.9   28.62  4796.7   30.31  4977.6   28.23  4979.1   25.23  5020.9   25.23
  5022.4   28.23  5440.6   28.88  5744.3   37.15  6159.1   39.37    6219   42.75
  6504.2   45.51  6676.3   43.06  6972.4   46.29  7210.8   53.11  7414.8   52.52
#Mann= 3 ,-1,0
  2583.1     .15       0  4977.6     .05       0  5022.4     .15       0
Bank Sta=4977.6,5022.4
XS Rating Curve= 0 ,0
Exp/Cntr=0.3,0.1

Type RM Length L Ch R = 1 ,11729   ,1063,1063,1063
BEGIN DESCRIPTION:
Reedy Creek XS 4.0
END DESCRIPTION:
XS GIS Cut Line= 2
       2507220.2       804098.92      2504048.46       801529.81
#Sta/Elev= 30
  2823.4    53.7    3023   48.39  3157.9    47.1  3232.3   41.96  3255.1    42.3
  3366.4      33  3489.7   30.01  3910.1   29.06  3941.8   33.81  3966.8   29.62
  4021.8   31.31  4112.8   28.99  4243.7   28.81  4258.1   33.79  4263.7   33.88
  4282.7   29.77    4364   28.13  4977.6   28.07  4979.1   25.07  5020.9   25.07
  5022.4   28.07  5393.1   28.78  5406.8   30.01  5422.1   38.08  5430.5   39.47
  5455.3   37.14  5863.7   37.24    6218   44.62  6406.3   51.04  6905.1   52.19
#Mann= 3 ,-1,0
  2823.4     .15       0  4977.6     .05       0  5022.4     .15       0
Bank Sta=4977.6,5022.4
XS Rating Curve= 0 ,0
Exp/Cntr=0.3,0.1

Type RM Length L Ch R = 1 ,10666   ,1038,1038,1038
BEGIN DESCRIPTION:
Reedy Creek XS 3.0
END DESCRIPTION:
XS GIS Cut Line= 4
      2507881.05       805255.18       2507979.5       803310.67
      2506010.36        801809.2      2504065.84        801464.6
#Sta/Elev= 30
     925   56.89  1549.2   51.91  1626.6   46.19  1680.9   47.37  1884.5   39.45
  2011.8   40.07  2170.1   34.49  2310.5   41.04  2669.5   43.13  2839.2   41.29
  2883.6   36.47  3200.4   27.95  4744.7   29.13  4977.6   26.89  4979.1   23.89
  5020.9   23.89  5022.4   26.89  5354.3   27.39  5447.9   35.93  5722.2   39.66
  5748.1   42.86  5797.3   38.05  5817.6   41.17  5922.4   40.36  5970.4   44.38
  6243.2   42.88  6266.6   47.83  6365.6   45.72  6713.6   51.61  7323.1   52.41
#Mann= 3 ,-1,0
     925     .15       0  4977.6     .05       0  5022.4     .15       0
Bank Sta=4977.6,5022.4
XS Rating Curve= 0 ,0
Exp/Cntr=0.3,0.1

Type RM Length L Ch R = 1 ,9628    ,1100,1100,1100
BEGIN DESCRIPTION:
Reedy Creek XS 2.0
END DESCRIPTION:
XS GIS Cut Line= 4
      2509653.28       806239.76      2510785.53       804073.71
      2505985.75       800726.17      2504828.93       800947.69
#Sta/Elev= 30
 -2827.1   56.86 -2692.4   56.97 -2406.2   50.65 -2017.6   49.03 -1976.5   45.98
 -1792.6   48.22 -1740.1   46.91 -1697.5   38.75 -1597.1   29.39 -1502.4   27.42
   424.4   26.74  1075.4   27.82  1133.2   30.91  1241.4    28.6  1426.9   29.34
  1437.9   27.45  1546.6   29.68  2036.6   26.66  3886.7    28.5  4977.6   26.54
  4979.1   23.54  5020.9   23.54  5022.4   26.54  5461.1   27.13  5732.3   32.49
  5791.6   36.26  5825.7   42.78  5896.8   47.95  6503.7   54.38  6646.7   53.04
#Mann= 3 ,-1,0
 -2827.1     .15       0  4977.6     .05       0  5022.4     .15       0
Bank Sta=4977.6,5022.4
XS Rating Curve= 0 ,0
Exp/Cntr=0.3,0.1

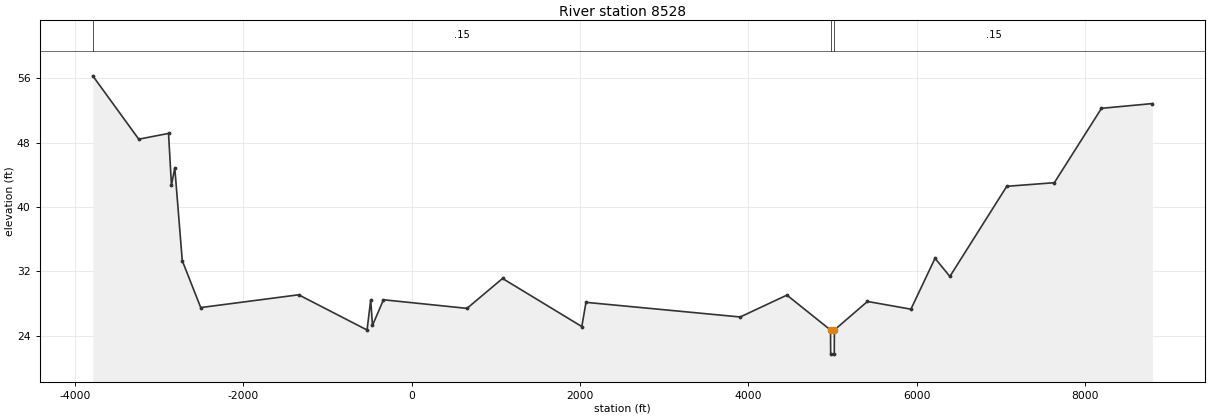
Type RM Length L Ch R = 1 ,8528    ,0,0,0
BEGIN DESCRIPTION:
Reedy Creek XS 1.0
END DESCRIPTION:
XS GIS Cut Line= 4
      2509874.81       806412.05      2511400.89       803753.73
      2506256.51       799495.46      2503425.89       799766.21
#Sta/Elev= 30
 -3786.2   56.32 -3239.9   48.44 -2886.4   49.16 -2851.5   42.73   -2812   44.88
 -2723.1   33.33   -2504    27.5 -1340.7   29.09  -528.3   24.71  -484.6   28.47
    -464   25.28    -333   28.47   659.1    27.4  1081.1   31.12  2022.8   25.14
  2072.3   28.15  3904.2   26.33    4459   29.05  4977.1   24.71  4978.6   21.71
  5021.4   21.71  5022.9   24.71  5415.8   28.26    5932    27.3  6218.4   33.63
  6394.7   31.37  7070.5   42.58  7635.5   43.03  8195.6   52.28  8800.7   52.87
#Mann= 3 ,-1,0
 -3786.2     .15       0  4977.1     .05       0  5022.9     .15       0
Bank Sta=4977.1,5022.9
XS Rating Curve= 0 ,0
Exp/Cntr=0.3,0.1
LCMann Table=0

Chan Stop Cuts=-1
Use User Specified Reach Order=0
User Specified Reach Order=Reedy Creek     ,Reach-1
Composite Channel Slope=5