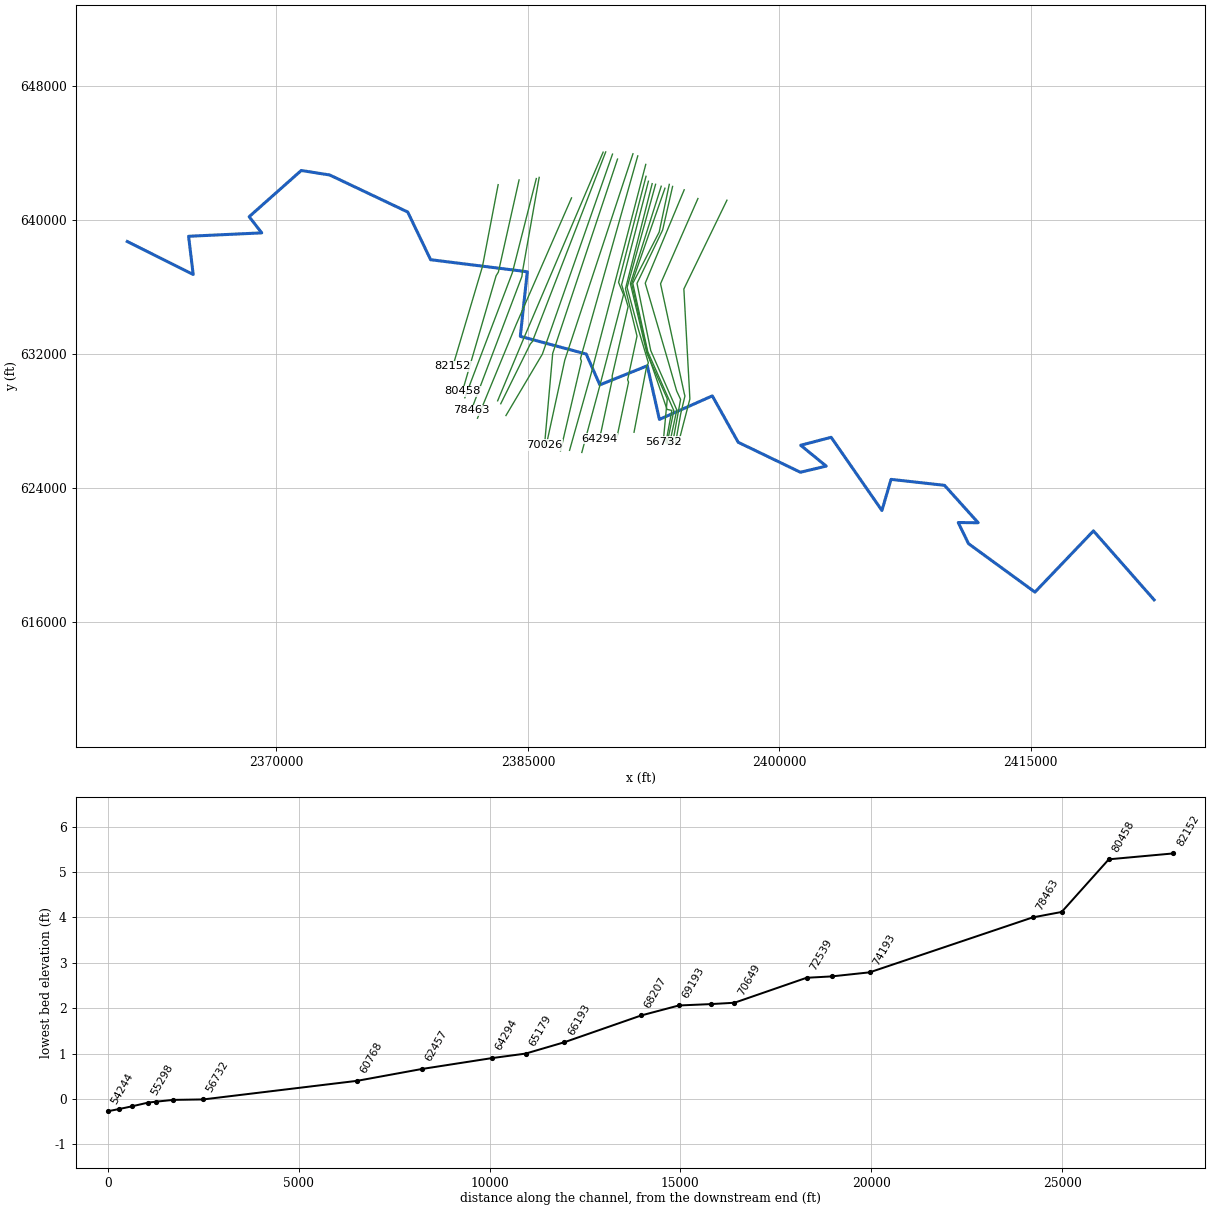
--- BlackRiver.prj (project) ---

Proj Title=S-45-30 over Black River
Current Plan=p07
Default Exp/Contr=0.3,0.1
English Units
Geom File=g05
Geom File=g01
Geom File=g06
Geom File=g02
Flow File=f01
Flow File=f02
Flow File=f03
Plan File=p04
Plan File=p05
Plan File=p01
Plan File=p07
Plan File=p02
Y Axis Title=Elevation
X Axis Title(PF)=Main Channel Distance
X Axis Title(XS)=Station
BEGIN DESCRIPTION:
END DESCRIPTION:
DSS Export Rating Curves= 0
DSS Export Rating Curve Sorted= 0
DSS Export Volume Flow Curves= 0
DXF OffsetX= 0
DXF OffsetY= 0
DXF ScaleX= 1
DXF ScaleY= 10

--- BlackRiver.p07 (plan) ---

Plan Title=Proposed Conditions
Program Version=6.60
Short Identifier=Proposed
Geom File=g06
Flow File=f01
Subcritical Flow
K Sum by GR= 0
Std Step Tol= 0.01
Critical Tol= 0.01
Num of Std Step Trials= 20
Max Error Tol= 0.3
Flow Tol Ratio= 0.001
Split Flow NTrial= 30
Split Flow Tol= 0.02
Split Flow Ratio= 0.02
Log Output Level= 0
Friction Slope Method= 1
Unsteady Friction Slope Method= 2
Unsteady Bridges Friction Slope Method= 1
Parabolic Critical Depth
Global Vel Dist= 0 , 0 , 0
Global Log Level= 0
CheckData=True
Encroach Param=-1 ,0,0, 0
Flow Ratio Tolerance=0.1
Flow Ratio Min Ratio=0.5
Flow Ratio Max Ratio=4
Flow Ratio Max Iterations= 10
Computation Interval=1MIN
Output Interval=1HOUR
Instantaneous Interval=1HOUR
Mapping Interval=1HOUR
Computation Time Step Use Courant=        0
Computation Time Step Use Time Series=    0
Computation Time Step Count To Double=0
Computation Time Step Max Doubling=0
Computation Time Step Max Halving=0
Computation Time Step Residence Courant=0
Run HTab= 0
Run UNet= 0
Run Sediment= 0
Run PostProcess= 0
Run WQNet= 0
Run RASMapper= 0
UNET Theta= 1
UNET Theta Warmup= 1
UNET ZTol= 0.02
UNET ZSATol= 0.02
UNET MxIter= 20
UNET Max Iter WO Improvement= 0
UNET MaxInSteps= 0
UNET DtIC= 0
UNET DtMin= 0
UNET MaxCRTS= 20
UNET WFStab= 2
UNET SFStab= 1
UNET WFX= 1
UNET SFX= 1
UNET Gravity=32.17405
UNET 1D Methodology=Finite Difference
UNET DSS MLevel= 4
UNET Pardiso=0
UNET DZMax Abort= 100
UNET Use Existing IB Tables=-1
UNET Froude Reduction=False
UNET Froude Limit= 0.8
UNET Froude Power= 4
UNET D1 Cores= 0
UNET WindReference=Eulerian
UNET WindDragFormulation=Hsu (1988)
UNET D2 Coriolis=0
UNET D2 Cores= 0
UNET D2 Theta= 1
UNET D2 Theta Warmup= 1
UNET D2 Z Tol= 0.01
UNET D2 Volume Tol= 0.01
UNET D2 Max Iterations= 20
UNET D2 Advanced Convergence=0
UNET D2 WS Max Tol=0.15
UNET D2 WS RMS Tol=0.002
UNET D2 WS Stall Tol=1
UNET D2 Equation= 0
UNET D2 RampUpFraction=0.1
UNET D2 TimeSlices= 1
UNET D2 Turbulence Formulation=None
UNET D2 Eddy Viscosity=0.3
UNET D2 Transverse Eddy Viscosity=0.1
UNET D2 Smagorinsky Mixing=0.05
UNET D2 BCVolumeCheck=0
UNET D2 Cores=0
UNET D2 SolverType=PARDISO (Direct)
UNET D2 Minimum Iterations= 3
UNET D2 Maximum Iterations= 30
UNET D2 Restart Number= 10
UNET D2 Relaxation Coeff=1.3
UNET D2 SOR Precondition Iterations= 10
UNET D2 ILUT Maximum Fill= 8
UNET D2 ILUT Tolerance=1E-08
UNET D2 Convergence Tolerance=0.00001
PS Theta= 1
PS WS Tol= 0.01
PS Volume Tol= 0.01
PS Max Iterations= 20
PS Equation= 0
PS Advance Time Step=-1
PS Target Courant=0.9
PS Time Slices= 1
PS Iterate With 2D=0
PS Project Initial WSE from DS=-1
PS Ramp Up Initial WSE from US=-1
PS Cores=0
UNET D1D2 MaxIter= 0
UNET D1D2 ZTol=0.01
UNET D1D2 QTol=0.1
UNET D1D2 MinQTol=1
Write IC File= 0
Write IC File at Fixed DateTime=0
Write IC File at Sim End=0
Echo Input=False
Echo Parameters=False
Echo Output=False
Write Detailed= 0
HDF Write Warmup=0
HDF Write Time Slices=0
HDF Flush=0
HDF Compression= 1
HDF Chunk Size= 1
HDF Spatial Parts= 1
HDF Use Max Rows=0
HDF Fixed Rows= 1
Calibration Method= 0
Calibration Iterations= 20
Calibration Max Change=0.05
Calibration Tolerance=0.2
Calibration Maximum=1.5
Calibration Minimum=0.5
Calibration Optimization Method= 1
WQ AD Non Conservative
WQ ULTIMATE=-1
WQ Max Comp Step=1HOUR
WQ Output Interval=15MIN
WQ Output Selected Increments= 0
WQ Create Restart=0
WQ Fixed Restart=0
WQ System Summary=0
WQ Write To DSS=0
Sorting and Armoring Iterations= 10
XS Update Threshold= 0.02
Bed Roughness Predictor= 0
Processes Affected by Predictor=Sediment Only
Hydraulics Update Threshold= 0.02
Energy Slope Method= 1
Volume Change Method= 1
Sediment Retention Method= 0
Sediment TS Multiplier= 1
Warm Up Method= 0
XS Weighting Method= 0
Number of US Weighted Cross Sections= 1
Number of DS Weighted Cross Sections= 1
Upstream XS Weight=0
Main XS Weight=1
Downstream XS Weight=0
Number of DS XS's Weighted with US Boundary= 1
Upstream Boundary Weight= 1
Weight of XSs Associated with US Boundary= 0
Number of US XS's Weighted with DS Boundary= 1
Downstream Boundary Weight= 0.5
Weight of XSs Associated with DS Boundary= 0.5
Percentile Method= 0
Sediment Output Level= 3
Mass or Volume Output= 0
Output Increment Type= 1
Profile and TS Output Increment= 1
Transport Output Increment 1
XS Output Flag= 0
XS Output Increment= 10
Read HDF5 Sediment Hotstart= 0
Sediment Hotstart Type= 0
Write Gradation File= 0
Read Gradation Hotstart= 0
Write HDF5 File= 1
Write Binary Output= 1
Write DSS Sediment File= 0
DSS Sediment Output Type= 1
SV Curve= 0
Specific Gage Flag= 0
Subcell Erosion Methods= 0
Subcell Deposition Methods= 0
Advection Scheme= 1
Matrix Solver= 0
Implicit Weighting Factor= 1
Maximum Outer Loop Convergence Iterations= 5
Convergence Maximum Absolute= 0.001
Convergence RMSE= 0.0001
Grain Fractions Max Abs Error= 0.001
Max Subgrid Regions= 1
Max Subgrid Length Scale= 3.402823E+38
Initial Layer Thickness= 3
Min Layer Thickness= 0.1
Max Layer Thickness= 6
Number of Layers= 5

--- BlackRiver.p01 (plan) ---

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Plan Title=Natural Conditions
Short Identifier=Natural
Geom File=g01
Flow File=f01

--- BlackRiver.p02 (plan) ---

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Plan Title=FEMA Effective Model
Short Identifier=FEMA DE
Geom File=g02
Flow File=f03

--- BlackRiver.p04 (plan) ---

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Plan Title=Existing Conditions
Short Identifier=Existing
Geom File=g05
Flow File=f01

--- BlackRiver.p05 (plan) ---

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Plan Title=Sensitivity
Short Identifier=Sensitivity
Geom File=g05
Flow File=f02

--- BlackRiver.f01 (steady flow) ---

Flow Title=USGS Regression Equations
Program Version=6.60
Number of Profiles= 6
Profile Names=2 Yr,10 Yr,25 yr,50 Yr,100 Yr,500 Yr
River Rch & RM=Black River,Reach-1         ,82152
    6359   17852   26219   33689   41645   62746
Boundary for River Rch & Prof#=Black River,Reach-1         , 1
Up Type= 0
Dn Type= 3
Dn Slope=0.0005
Boundary for River Rch & Prof#=Black River,Reach-1         , 2
Up Type= 0
Dn Type= 3
Dn Slope=0.0005
Boundary for River Rch & Prof#=Black River,Reach-1         , 3
Up Type= 0
Dn Type= 3
Dn Slope=0.0005
Boundary for River Rch & Prof#=Black River,Reach-1         , 4
Up Type= 0
Dn Type= 3
Dn Slope=0.0005
Boundary for River Rch & Prof#=Black River,Reach-1         , 5
Up Type= 0
Dn Type= 3
Dn Slope=0.0005
Boundary for River Rch & Prof#=Black River,Reach-1         , 6
Up Type= 0
Dn Type= 3
Dn Slope=0.0005
DSS Import GetInterval= 0
DSS Import GetPeak= 0
DSS Import FillOption= 0

--- BlackRiver.f02 (steady flow) ---

Flow Title=USGS Regression Equations - Sensitivity
Program Version=6.60
Number of Profiles= 3
Profile Names=-3 ft,100 yr,+3 ft
River Rch & RM=Black River,Reach-1         ,82152
   41645   41645   41645
Boundary for River Rch & Prof#=Black River,Reach-1         , 1
Up Type= 0
Dn Type= 1
Dn Known WS=13.53
Boundary for River Rch & Prof#=Black River,Reach-1         , 2
Up Type= 0
Dn Type= 1
Dn Known WS=16.53
Boundary for River Rch & Prof#=Black River,Reach-1         , 3
Up Type= 0
Dn Type= 1
Dn Known WS=19.53
DSS Import GetInterval= 0
DSS Import GetPeak= 0
DSS Import FillOption= 0

--- BlackRiver.f03 (steady flow) ---

Flow Title=FEMA Effective Flowrates
Program Version=6.60
Number of Profiles= 1
Profile Names=100-year
River Rch & RM=Black River,Reach-1         ,159657
   34101
River Rch & RM=Black River,Reach-1         ,157998
   34129
River Rch & RM=Black River,Reach-1         ,156926
   34131
River Rch & RM=Black River,Reach-1         ,146643
   34132
River Rch & RM=Black River,Reach-1         ,144971
   34136
River Rch & RM=Black River,Reach-1         ,139998
   34138
River Rch & RM=Black River,Reach-1         ,131704
   34138
River Rch & RM=Black River,Reach-1         ,129998
   34138
River Rch & RM=Black River,Reach-1         ,121676
   34138
River Rch & RM=Black River,Reach-1         ,111998
   34138
River Rch & RM=Black River,Reach-1         ,105327
   34138
River Rch & RM=Black River,Reach-1         ,91806
   34138
River Rch & RM=Black River,Reach-1         ,86119
   34138
River Rch & RM=Black River,Reach-1         ,79002
   34138
Boundary for River Rch & Prof#=Black River,Reach-1         , 1
Up Type= 0
Dn Type= 1
Dn Known WS=22.63
DSS Import GetInterval= 0
DSS Import GetPeak= 0
DSS Import FillOption= 0

--- BlackRiver.g06 (geometry) ---

Geom Title=Proposed
Program Version=6.60

River Reach=Black River     ,Reach-1
Reach XY= 30
      2361100.22       638690.91      2365033.58       636721.76
      2364759.06       639003.622369121.22480828639206.904638617
      2368370.99       640171.83      2371478.86       642930.54
      2373178.48       642661.58      2377830.98       640451.42
      2379196.78       637604.73      2384964.09636886.862805294
       2384545.7       633031.15      2388476.19       631974.85
2389292.30014387630134.5181526952392121.05202736631273.590874441
      2392844.47        628073.6      2395999.55       629477.55
      2397544.66        626707.8 2401254.9018714624918.326245681
2402793.60900441625285.5280088242401271.16118874626529.463774955
2403090.13987087627004.3184095212406117.00926423622635.007148867
       2406661.8       624493.28      2409853.01       624137.64
      2411860.08       621905.57      2410670.19       621915.98
      2411282.27       620657.37      2415245.44       617764.05
      2418735.29       621418.43      2422351.99        617304.6

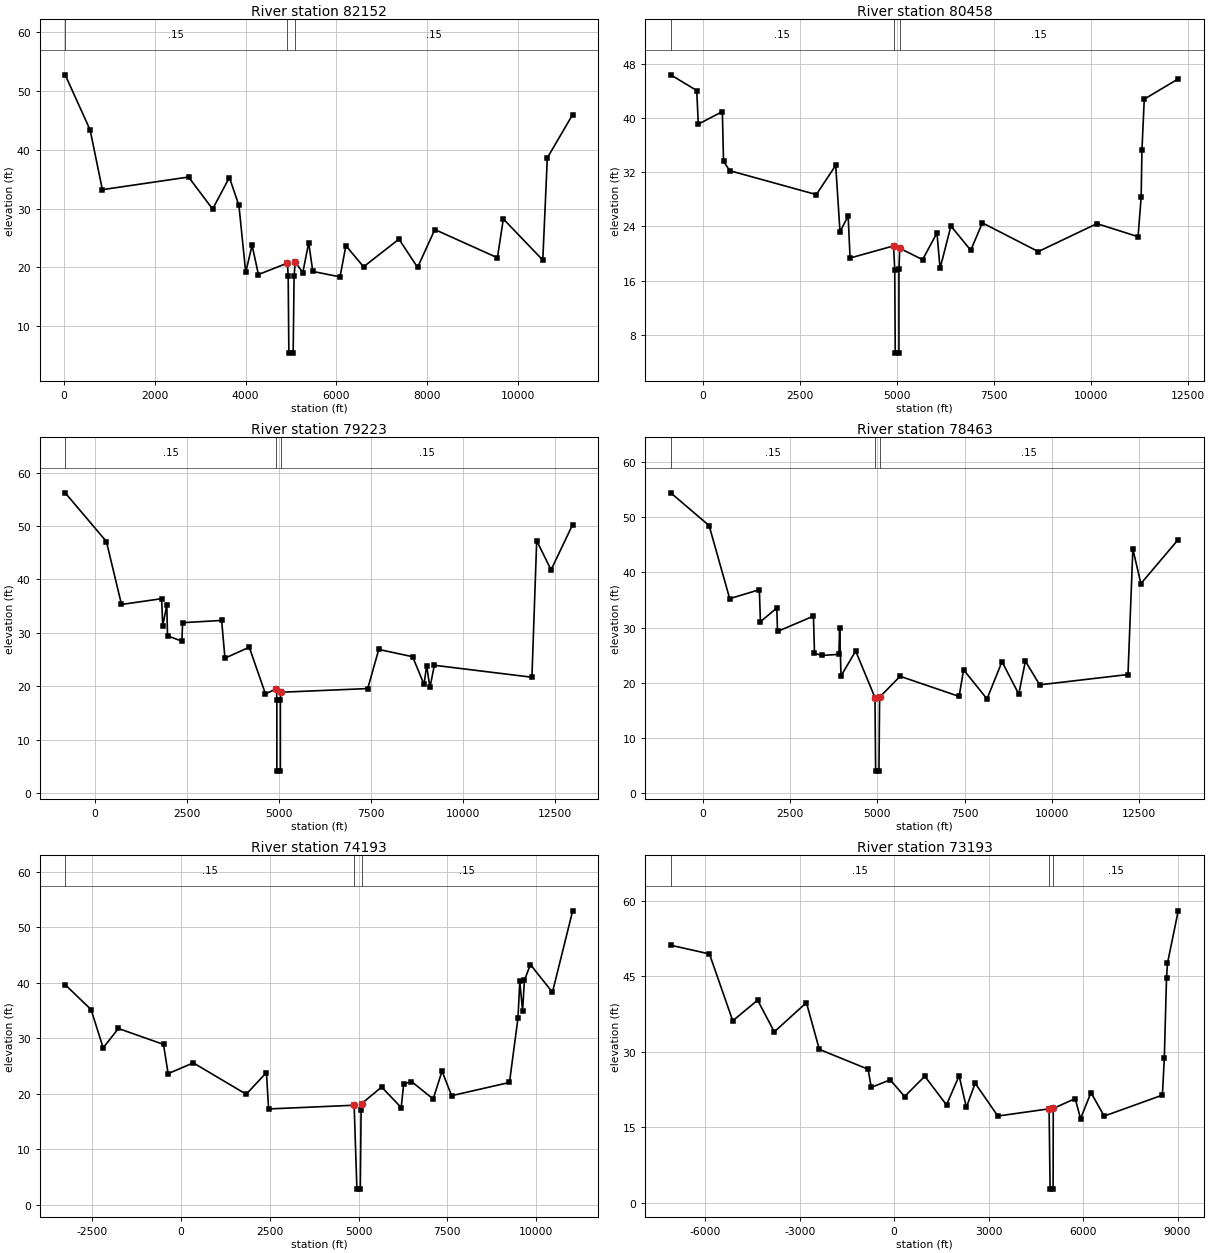
Type RM Length L Ch R = 1 ,82152   ,1693.7,1693.7,1693.7
BEGIN DESCRIPTION:
Black River 142.0
END DESCRIPTION:
XS GIS Cut Line= 3
      2383224.88        642084.3      2382287.32       637195.08
      2380519.72       631243.32
#Sta/Elev= 30
    21.7   52.79   571.7   43.41   841.7   33.24  2741.7   35.39  3271.7   29.94
  3641.7   35.31  3851.7   30.56  4001.7   19.15  4141.7   23.78  4281.7   18.79
  4921.7   20.74 4937.84   18.48  4952.5    5.41  5047.5    5.41 5067.94   18.48
 5092.11   20.94    5260   19.12    5390    24.2    5480   19.32    6080   18.39
    6210    23.7    6600   20.11    7380   24.82    7790      20    8170   26.45
    9550   21.65    9680   28.25   10550   21.25   10650   38.65 11208.7   46.03
#Mann= 3 ,0,0
    21.7     .15       0  4921.7     .05       0 5092.11     .15       0
Bank Sta=4921.7,5092.11
XS Rating Curve= 0 ,0
Exp/Cntr=0.3,0.1

Type RM Length L Ch R = 1 ,80458   ,1235.1,1235.1,1235.1
BEGIN DESCRIPTION:
Black River 141.0
END DESCRIPTION:
XS GIS Cut Line= 4
      2384472.22        642365.72383238.73749811636866.689391571
2383102.11948439636643.896938436      2381090.49       629741.96
#Sta/Elev= 30
  -830.8   46.39  -160.8   44.07  -120.8    39.1   499.2   40.96   529.2   33.61
   689.2   32.23  2919.2    28.7  3419.2   33.02  3529.2   23.22  3739.2   25.53
  3789.2   19.33  4909.2   21.12 4939.59   17.62  4952.5    5.28  5047.5    5.28
  5047.8   17.67    5069 20.7655  5657.2   19.09  6027.2   23.03  6107.2    17.8
  6387.2   24.06  6897.2   20.47  7197.2   24.52  8637.2   20.28 10147.2   24.41
 11207.2   22.48 11287.2   28.32 11307.2   35.22 11367.2    42.8 12242.2   45.79
#Mann= 3 ,0,0
  -830.8     .15       0  4909.2     .05       0    5069     .15       0
Bank Sta=4909.2,5069
XS Rating Curve= 0 ,0
Exp/Cntr=0.3,0.1

Type RM Length L Ch R = 1 ,79223   ,759.7,759.7,759.7
BEGIN DESCRIPTION:
Black River 140.0
END DESCRIPTION:
XS GIS Cut Line= 3
      2385501.46       642449.76      2384072.76       636830.64
       2381237.5       629363.82
#Sta/Elev= 30
  -797.9    56.2   322.1   47.09   732.1   35.31  1822.1   36.39  1852.1    31.3
  1962.1   35.21  1982.1   29.44  2372.1   28.44  2392.1    31.9  3452.1   32.32
  3542.1   25.26  4202.1   27.31  4642.1   18.58  4942.1   19.53    4952   17.39
  4952.3    4.12  5047.7    4.12    5048   17.39    5060   18.88    7420   19.57
    7720   26.89    8640   25.53    8950   20.34    9020   23.86    9110   19.78
    9230   23.93   11880   21.69   12010   47.25   12400   41.78   12987   50.26
#Mann= 3 ,0,0
  -797.9     .15       0  4942.1     .05       0    5060     .15       0
Bank Sta=4942.1,5060
XS Rating Curve= 0 ,0
Exp/Cntr=0.3,0.1

Type RM Length L Ch R = 1 ,78463   ,4270.2,4270.2,4270.2
BEGIN DESCRIPTION:
Black River 139.0
END DESCRIPTION:
XS GIS Cut Line= 4
      2385672.27       642518.332384670.14200467636860.525891702
2384644.51401387636613.856480237      2381620.38       628621.59
#Sta/Elev= 30
  -919.4   54.44   180.6    48.5   770.6   35.26  1620.6   36.88  1650.6   31.08
  2120.6   33.56  2140.6   29.32  3170.6   32.09  3200.6   25.36  3410.6   24.97
  3900.6   25.16  3920.6   29.88  3960.6   21.25  4380.6   25.77  4933.917.32317
  4952.3       4  5047.7       4 5066.94    17.4  5654.3   21.19  7344.3   17.54
  7474.3   22.36  8144.3   17.09  8574.3   23.84  9054.3   17.96  9244.3   23.93
  9654.3   19.64 12184.3   21.51 12324.3   44.25 12554.3   37.98 13624.5   45.97
#Mann= 3 ,0,0
  -919.4     .15       0  4933.9     .05       0 5066.94     .15       0
Bank Sta=4933.9,5066.94
XS Rating Curve= 0 ,0
Exp/Cntr=0.3,0.1

Type RM Length L Ch R = 1 ,74193   ,1000,1000,1000
BEGIN DESCRIPTION:
Black River 135.0
END DESCRIPTION:
XS GIS Cut Line= 3
      2387601.91       641294.47      2384291.71       633720.54
      2381993.69        628145.6
#Sta/Elev= 30
 -3265.7   39.66 -2535.7   35.17 -2195.7   28.27 -1765.7   31.76  -495.7   28.89
  -365.7   23.62   344.3   25.56  1834.3    19.9  2404.3   23.82  2464.3   17.25
  4874.3   17.92  4952.3    2.79  5047.7    2.79 5070.07      17 5084.15   18.21
    5650    21.2    6200    17.5    6270   21.74    6490    22.2    7100   19.04
    7350   24.07    7620   19.64    9250   22.03    9490   33.67    9540   40.25
    9620   34.94    9670   40.45    9840   43.29   10460   38.29   11030   52.98
#Mann= 3 ,0,0
 -3265.7     .15       0  4874.3     .05       0 5084.15     .15       0
Bank Sta=4874.3,5084.15
XS Rating Curve= 0 ,0
Exp/Cntr=0.3,0.1

Type RM Length L Ch R = 1 ,73193   ,653.6,653.6,653.6
BEGIN DESCRIPTION:
Black River 134.0
END DESCRIPTION:
XS GIS Cut Line= 3
      2389486.97       644024.85      2384744.68       632895.06
      2383194.37       629183.21
#Sta/Elev= 30
   -7098   51.18   -5868   49.45   -5128   36.16   -4338   40.26   -3808   33.96
   -2788   39.77   -2378   30.48    -828   26.53    -728   22.92    -128   24.42
     332   21.11     972   25.14    1662   19.44    2062   25.23 2292.96   18.95
    2572   23.75    3292   17.23  4920.718.65973  4952.3     2.7  5047.7     2.7
  5052.718.73096    5750    20.7    5920    16.7    6250   21.89    6670   17.22
    8520   21.39    8580   28.67    8650   44.57    8680   47.57  9022.6   58.02
#Mann= 3 ,0,0
   -7098     .15       0  4920.7     .05       0  5052.7     .15       0
Bank Sta=4920.7,5052.7
XS Rating Curve= 0 ,0
Exp/Cntr=0.3,0.1

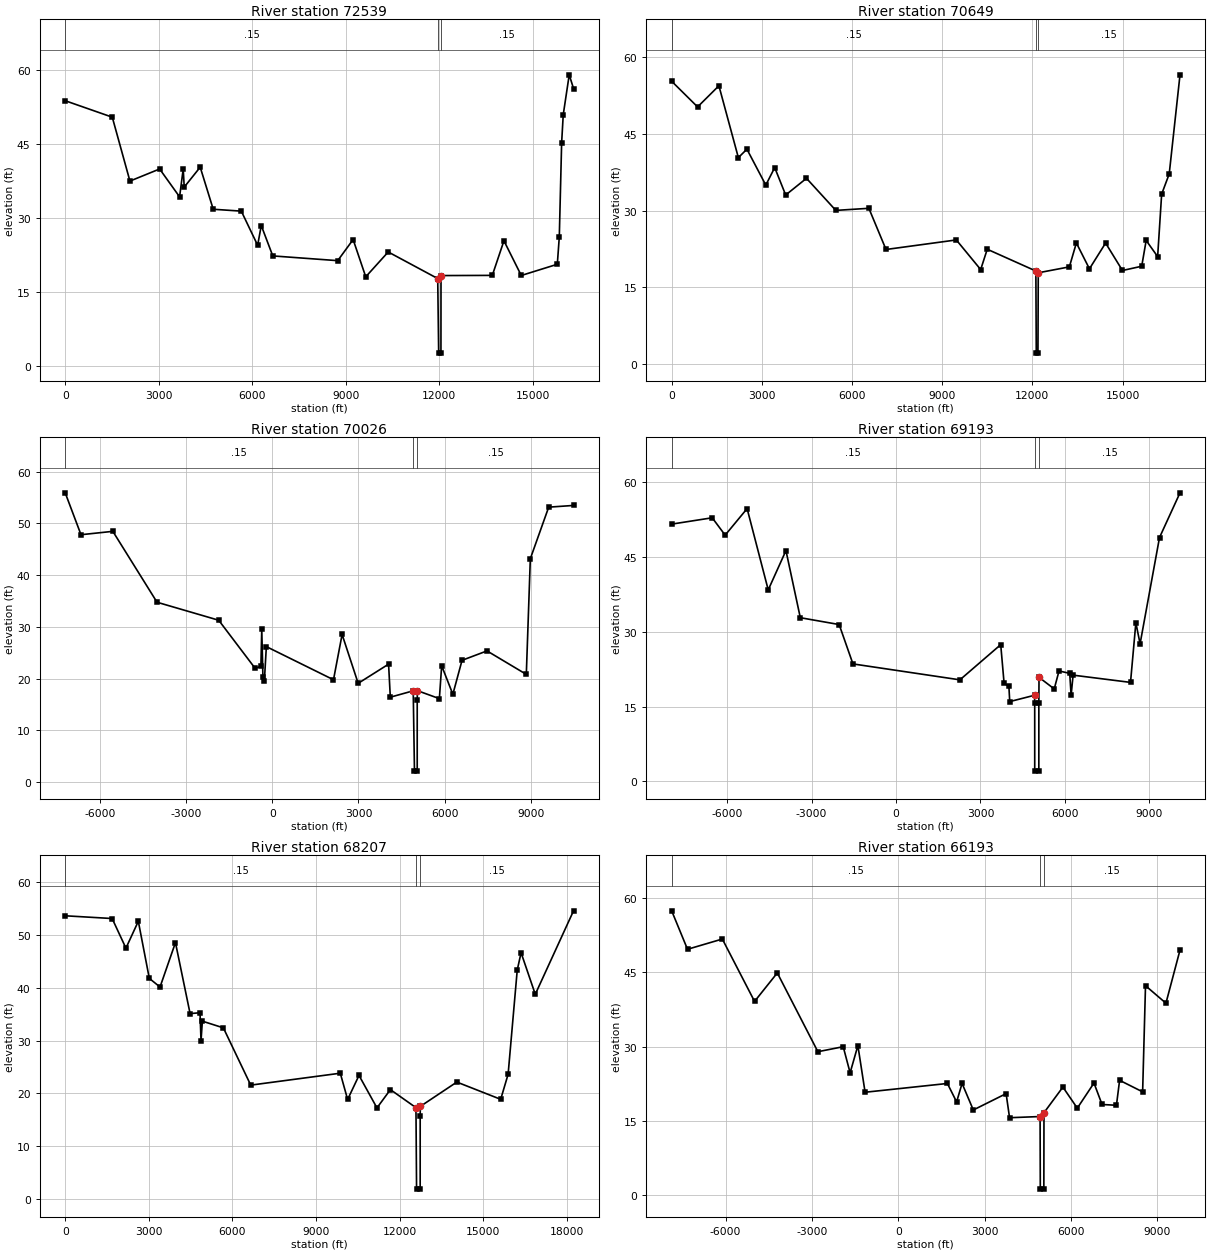
Type RM Length L Ch R = 1 ,72539   ,1890.1,1890.1,1890.1
BEGIN DESCRIPTION:
Black River 133.0
END DESCRIPTION:
XS GIS Cut Line= 5
2389641.32232304644040.4090044122385335.97099559632904.830187991
2385304.08590526632762.1778146992385143.20619301632577.944595825
2383380.53232304629008.149004412
#Sta/Elev= 30
       0   53.74  1510.4   50.41  2076.8   37.48  3030.1   39.93  3670.3   34.29
  3786.4   39.93    3819   36.26  4331.6    40.3  4749.4   31.78  5650.7    31.4
  6174.9   24.49    6291   28.49  6660.3   22.34  8743.5   21.38  9238.7   25.65
  9643.3   18.11 10364.4   23.14 11953.1 17.758611983.68    2.6712056.52    2.67
 12058.418.36255 13704.6    18.4 14077.8    25.4   14634   18.38 15790.3   20.65
 15854.1   26.17 15929.3   45.24 15980.6   50.91 16172.5   58.98 16310.9   56.21
#Mann= 3 ,0,0
       0     .15       0 11953.1     .05       0 12058.4     .15       0
Bank Sta=11953.1,12058.4
XS Rating Curve= 0 ,0
Exp/Cntr=0.3,0.1

Type RM Length L Ch R = 1 ,70649   ,623.1,623.1,623.1
BEGIN DESCRIPTION:
Black River 132.0
END DESCRIPTION:
XS GIS Cut Line= 3
2390046.31215834643907.8983524972385861.38215834631968.108352497
2383690.13215834628303.508352497
#Sta/Elev= 30
       0   55.32   862.3    50.3  1571.5   54.44  2218.2   40.38  2503.2   42.03
  3131.6      35    3428   38.43  3793.1   33.06  4484.9   36.33  5461.4   30.05
  6560.6   30.46  7130.7    22.4  9469.6   24.27 10280.5   18.47 10498.8   22.45
 12116.2   18.1912130.15    2.1212185.53    2.12 12196.1   17.84   13231      19
 13463.8   23.68 13898.6   18.62 14436.3   23.66 14996.9   18.29 15637.6   19.12
 15786.1   24.17 16167.7   21.01 16301.1   33.23 16552.8   37.19 16911.5   56.58
#Mann= 3 ,0,0
       0     .15       0 12116.2     .05       0 12196.1     .15       0
Bank Sta=12116.2,12196.1
XS Rating Curve= 0 ,0
Exp/Cntr=0.3,0.1

Type RM Length L Ch R = 1 ,70026   ,833.3,833.3,833.3
BEGIN DESCRIPTION:
Black River 131.0
END DESCRIPTION:
XS GIS Cut Line= 3
      2390345.07       643611.74      2386479.95       632019.32
      2385991.09        626545.4
#Sta/Elev= 30
 -7219.8   55.91 -6669.8   47.81 -5559.8   48.46 -4019.8   34.75 -1869.8   31.27
  -599.8   21.96  -399.8   22.37  -369.8   29.54  -329.8   20.38  -279.8   19.46
  -209.8   26.17  2130.2   19.76  2430.2   28.52  2990.2   19.07  4050.2   22.78
  4110.2   16.394908.60117.62008  4952.2    2.09  5047.8    2.09  5048.1    15.9
    505517.64949    5820   16.11    5900   22.47    6290   16.95    6610   23.52
    7480   25.34    8850    20.8    8990   43.17    9630   53.14 10495.7   53.47
#Mann= 3 ,0,0
 -7219.8     .15       04908.601     .05       0    5055     .15       0
Bank Sta=4908.601,5055
XS Rating Curve= 0 ,0
Exp/Cntr=0.3,0.1

Type RM Length L Ch R = 1 ,69193   ,986.4,986.4,986.4
BEGIN DESCRIPTION:
Black River 130.0
END DESCRIPTION:
XS GIS Cut Line= 3
      2391266.72       643929.58      2387200.13       631612.53
      2386118.22       626640.79
#Sta/Elev= 30
   -7971   51.55   -6531   52.82   -6071   49.34   -5291   54.66   -4541   38.37
   -3911   46.25   -3401    32.8   -2021   31.43   -1531   23.54    2269   20.35
    3719    27.4    3839   19.64    4009   19.07    4039   15.99    4919   17.26
  4926.5   15.78    4927    2.06    5073    2.06  5073.5   15.78    5080   20.85
    5620   18.53    5790   22.13    6170   21.65    6220   17.25    6290   21.29
    8330   19.84    8520   31.79    8670   27.57    9360   48.86 10088.1   57.82
#Mann= 3 ,0,0
   -7971     .15       0    4919     .05       0    5080     .15       0
Bank Sta=4919,5080
XS Rating Curve= 0 ,0
Exp/Cntr=0.3,0.1

Type RM Length L Ch R = 1 ,68207   ,2013.6,2013.6,2013.6
BEGIN DESCRIPTION:
Black River 129.0
END DESCRIPTION:
XS GIS Cut Line= 4
      2391552.72       643802.372388136.81859957631708.635633598
  2388192.424994 631544.39581934      2386944.51        626195.8
#Sta/Elev= 30
       0   53.67  1683.7   53.15  2178.1   47.53  2622.4   52.63  3016.7    41.8
  3401.3   40.16  3954.3   48.59  4479.3   35.12  4835.2   35.29  4871.4   29.97
  4919.1   33.69  5672.6   32.42  6654.5   21.56  9866.6   23.82 10129.8   18.84
 10537.7    23.4   11182   17.24 11663.7   20.71 12580.7   17.29 12602.5    1.84
 12731.8    1.84 12732.3   15.69 12736.317.52385 14046.6   22.14 15619.9   18.87
 15886.1   23.62 16213.3   43.38 16351.1   46.67 16860.1   38.78 18232.5   54.61
#Mann= 3 ,0,0
       0     .15       0 12580.7     .05       0 12736.3     .15       0
Bank Sta=12580.7,12736.3
XS Rating Curve= 0 ,0
Exp/Cntr=0.3,0.1

Type RM Length L Ch R = 1 ,66193   ,1013.8,1013.8,1013.8
BEGIN DESCRIPTION:
Black River 127.0
END DESCRIPTION:
XS GIS Cut Line= 3
      2392029.45       643293.94      2388780.58       630837.45
      2387484.79       626227.61
#Sta/Elev= 30
 -7873.2   57.41 -7323.2   49.65 -6113.2   51.72 -4993.2   39.13 -4203.2   44.88
 -2793.2   28.98 -1913.2   29.99 -1673.2   24.72 -1403.2   30.22 -1153.2    20.8
  1706.8   22.57  2026.8   18.85  2216.8   22.58  2606.8   17.22  3746.8   20.52
  3866.8   15.66  4927.3 15.8995 4934.78    1.25 5057.85    1.25  5062.5 16.6704
    5720   21.84    6220   17.59    6800   22.66    7080   18.33    7580   18.17
    7690   23.21    8490   20.88    8590    42.3    9300   38.77  9788.5   49.49
#Mann= 3 ,0,0
 -7873.2     .15       0  4927.3     .05       0  5062.5     .15       0
Bank Sta=4927.3,5062.5
XS Rating Curve= 0 ,0
Exp/Cntr=0.3,0.1

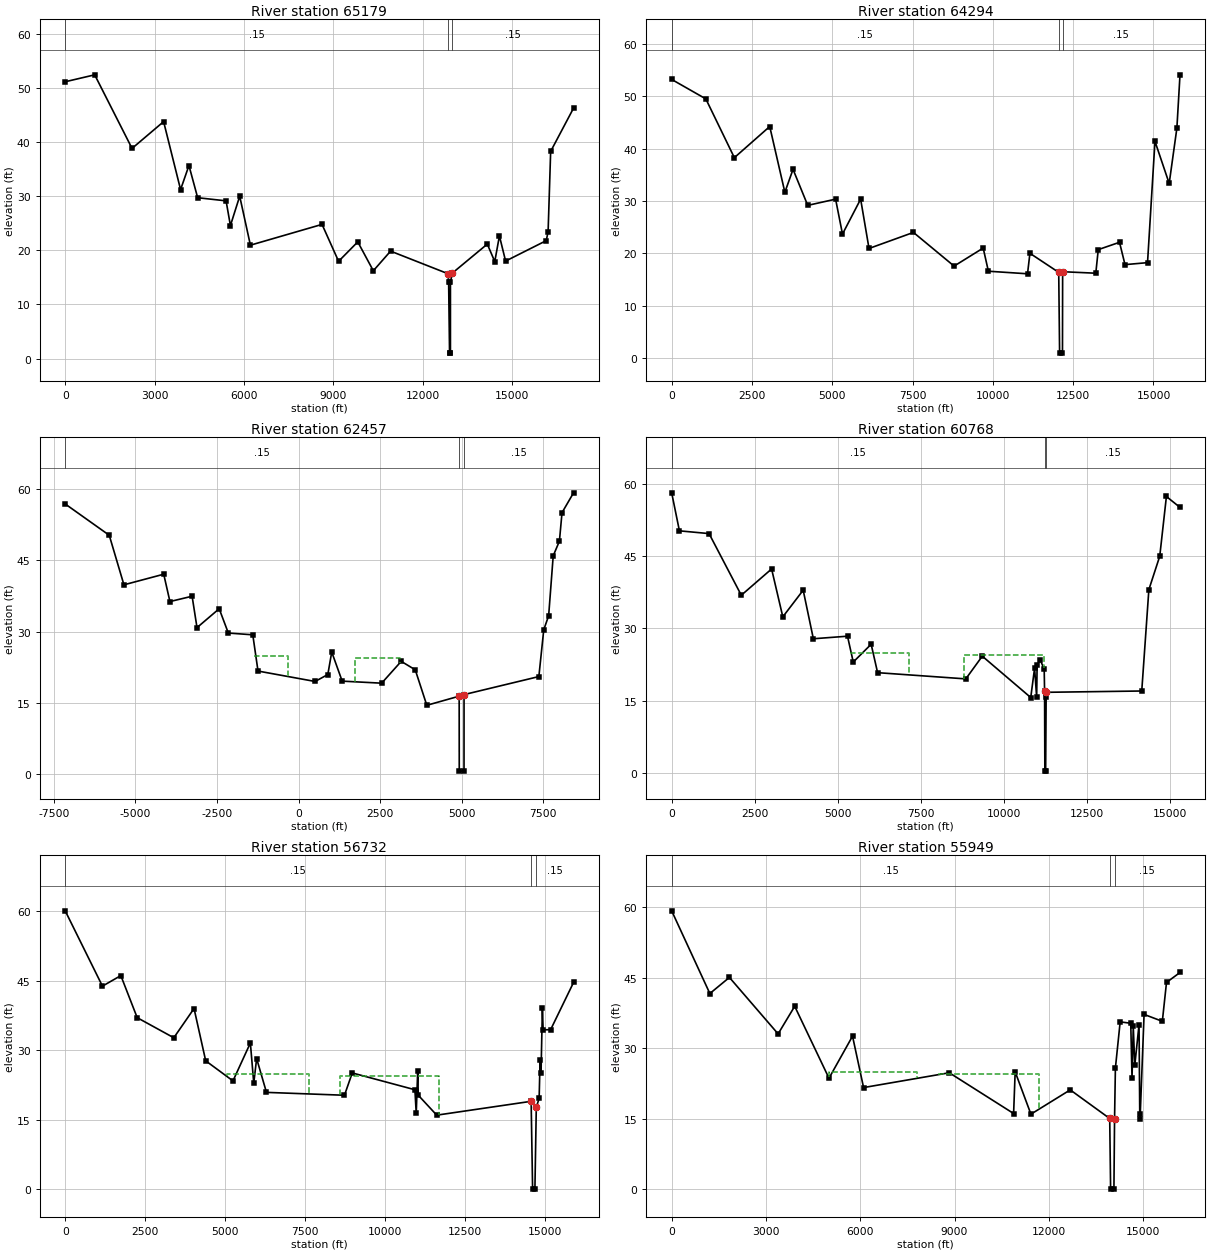
Type RM Length L Ch R = 1 ,65179   ,887.6,887.6,887.6
BEGIN DESCRIPTION:
Black River 126.0
END DESCRIPTION:
XS GIS Cut Line= 5
2392045.62790117642583.1714991632390408.77801605636254.300524402
2390704.82113191635519.296926412      2389315.17       630180.56
      2388215.75        626100.5
#Sta/Elev= 30
       0   51.15   990.4   52.43  2244.3   38.83    3305   43.78  3874.7   31.22
  4155.7   35.67  4448.3   29.72  5402.8   29.14  5548.5   24.57  5860.3      30
  6219.5   20.95  8625.4   24.79  9181.4   17.97  9825.6   21.56 10347.7   16.22
 10927.4   19.8512857.67   15.67 12877.1   14.1212907.92       112937.49       1
12937.49   14.18 13005.3   15.81 14175.6   21.15 14426.4   17.92 14582.7   22.66
   14790   18.01   16156   21.79 16217.9   23.47 16303.5   38.28 17071.7   46.27
#Mann= 3 ,0,0
       0     .15       012857.67     .05       0 13005.3     .15       0
Bank Sta=12857.67,13005.3
XS Rating Curve= 0 ,0
Exp/Cntr=0.3,0.1

Type RM Length L Ch R = 1 ,64294   ,1836.5,1836.5,1836.5
BEGIN DESCRIPTION:
Black River 125.0
END DESCRIPTION:
XS GIS Cut Line= 6
2392188.97640201642289.5268889442390590.35118085636116.319255313
2390976.57309344634800.0679348082390026.52563953 630675.79232132
2390033.16879415630468.363649827       2389274.4       626911.51
#Sta/Elev= 30
       0   53.23  1063.4   49.51  1951.3   38.27  3052.8   44.23  3523.9   31.65
  3778.1   36.04  4235.6   29.15  5103.3   30.34  5317.5   23.66    5883   30.34
  6143.7   20.91  7526.5   23.98  8792.5   17.54  9698.1   20.99  9859.8   16.56
 11078.6   16.07 11152.6   19.99 12049.8   16.3412077.08      .912166.49      .9
 12171.516.46592 13203.8   16.18 13280.5   20.69   13942   22.09 14113.3   17.82
 14814.5    18.2 15045.9    41.4 15488.8   33.34 15728.1   43.91 15825.3   54.11
#Mann= 3 ,0,0
       0     .15       0 12049.8     .05       0 12171.5     .15       0
Bank Sta=12049.8,12171.5
XS Rating Curve= 0 ,0
Exp/Cntr=0.5,0.3

Type RM Length L Ch R = 1 ,62457   ,1689.3,1689.3,1689.3
BEGIN DESCRIPTION:
Black River 124.0
END DESCRIPTION:
XS GIS Cut Line= 6
2392411.62904549642144.1880529362390820.97212948635870.983906001
2391508.15823089 633043.876172992390948.57437392630438.624271995
2391003.63038155630296.821347977      2390313.29       627022.17
#Sta/Elev= 30
 -7151.8   56.83 -5801.8   50.25 -5351.8   39.83 -4131.8   42.06 -3941.8   36.31
 -3261.8   37.43 -3111.8   30.83 -2431.8    34.8 -2151.8   29.69 -1401.8   29.32
 -1241.8    21.7   508.2   19.51   898.2   20.97  1018.2    25.7  1338.2   19.58
  2548.2   19.15  3148.2   23.74  3578.2   21.96 3932.38    14.5 4924.18   16.42
    4927     .66    5073     .66 5073.85   16.75    7367   20.54    7517   30.38
    7667   33.32    7807   45.93    7997   49.01    8077      55  8429.9   59.17
#Mann= 3 ,0,0
 -7151.8     .15       0 4924.18     .05       0 5073.85     .15       0
#XS Ineff= 2 ,-1
   -1376    -326   24.82    1732    3110   24.49
Permanent Ineff=
       F       F
Bank Sta=4924.18,5073.85
XS Rating Curve= 0 ,0
Exp/Cntr=0.5,0.3

Type RM Length L Ch R = 1 ,60768   ,4035.7,4035.7,4035.7
BEGIN DESCRIPTION:
Black River 122.0
END DESCRIPTION:
XS GIS Cut Line= 6
2392615.88384059642104.9415424332390916.53686308635945.744096208
 2391565.9501438633530.5279791982392184.42293721631451.457225425
2392068.57769228631159.791814128      2391330.26       627308.14
#Sta/Elev= 30
       0   58.09   233.1   50.21  1124.9   49.64  2094.9   36.86  3006.7   42.31
    3344   32.38  3957.1   37.91  4262.9   27.84  5290.8   28.37  5463.5   23.01
  6002.1    26.7  6196.1   20.81  8849.9   19.52  9345.9   24.23 10804.1   15.66
 10919.9   21.75 10982.1    15.7 10995.8   22.49 11092.6   23.42 11208.8   21.52
 11220.5   16.9211228.81      .411252.48      .4 11267.3   15.69 11273.316.73991
 14144.4   17.01 14358.2   38.02 14685.6   44.95 14886.1   57.33 15295.1   55.07
#Mann= 3 ,0,0
       0     .15       0 11220.5     .05       0 11273.3     .15       0
#XS Ineff= 2 ,-1
    5370    7155   24.82    8800   11190   24.49
Permanent Ineff=
       F       F
Bank Sta=11220.5,11273.3
XS Rating Curve= 0 ,0
Exp/Cntr=0.5,0.3

Type RM Length L Ch R = 1 ,56732   ,303.3,783.9,422.6
BEGIN DESCRIPTION:
Black River 119.0
END DESCRIPTION:
XS GIS Cut Line= 5
2392951.86449467641990.8318998412391114.10749375636173.747892966
 2392099.0704993632014.1728724692393313.47135297629301.822644573
 2393074.2968054626752.979974497
#Sta/Elev= 30
       0   60.11  1165.4   43.84  1740.7   46.12  2252.7   37.03  3398.5   32.69
  4031.6   39.01  4396.3   27.71  5249.7   23.37  5794.5   31.57    5900   22.88
  5990.5    28.2  6297.6   20.89  8738.9   20.27  8982.3   25.09 10942.8   21.46
 10984.4   16.38 11030.2   25.43 11048.6   20.27 11626.1   15.97 14580.1   18.96
 14626.2    -.0114698.29    -.01 14741.6   17.67 14830.6    19.6 14860.2   27.82
 14889.9   25.18 14932.7   39.09 14955.8   34.41 15189.7   34.43 15906.9   44.63
#Mann= 3 ,0,0
       0     .15       0 14580.1     .05       0 14741.6     .15       0
#XS Ineff= 2 ,-1
    5050    7622   24.82    8614   11711   24.49
Permanent Ineff=
       F       F
Bank Sta=14580.1,14741.6
XS Rating Curve= 0 ,0
Exp/Cntr=0.5,0.3

Type RM Length L Ch R = 1 ,55949   ,510.5,458.2,423
XS GIS Cut Line= 6
2393174.39616985641872.5241645742391189.09304328636176.672092498
2392141.05645509632023.7239730392393299.32390235628669.509174718
2393585.35402672628609.702122483 2393231.4022123626680.524348297
#Sta/Elev= 30
       0    59.2  1214.9    41.6  1836.8   45.03  3386.5   33.01  3914.6   38.89
  5005.6   23.58  5754.6   32.53    6106   21.59    8834   24.74   10880   16.07
 10929.5   24.94 11430.7   15.93 12681.7    21.1 13937.915.0102213966.46    -.02
14071.84    -.02   1409214.92412 14118.7   25.74 14270.5   35.57 14607.4   35.28
 14647.5   23.56 14687.5    34.6 14735.4    26.3   14871   34.99 14893.3   16.05
 14904.3   14.97 15031.1   37.16   15612   35.69 15744.9   43.96 16174.3   46.08
#Mann= 3 ,0,0
       0     .15       0 13937.9     .05       0   14092     .15       0
#XS Ineff= 2 ,-1
    4990    7808   24.82    8493   11696   24.49
Permanent Ineff=
       F       F
Bank Sta=13937.9,14092
XS Rating Curve= 0 ,0
Exp/Cntr(USF)=0,0
Exp/Cntr=0.5,0.3

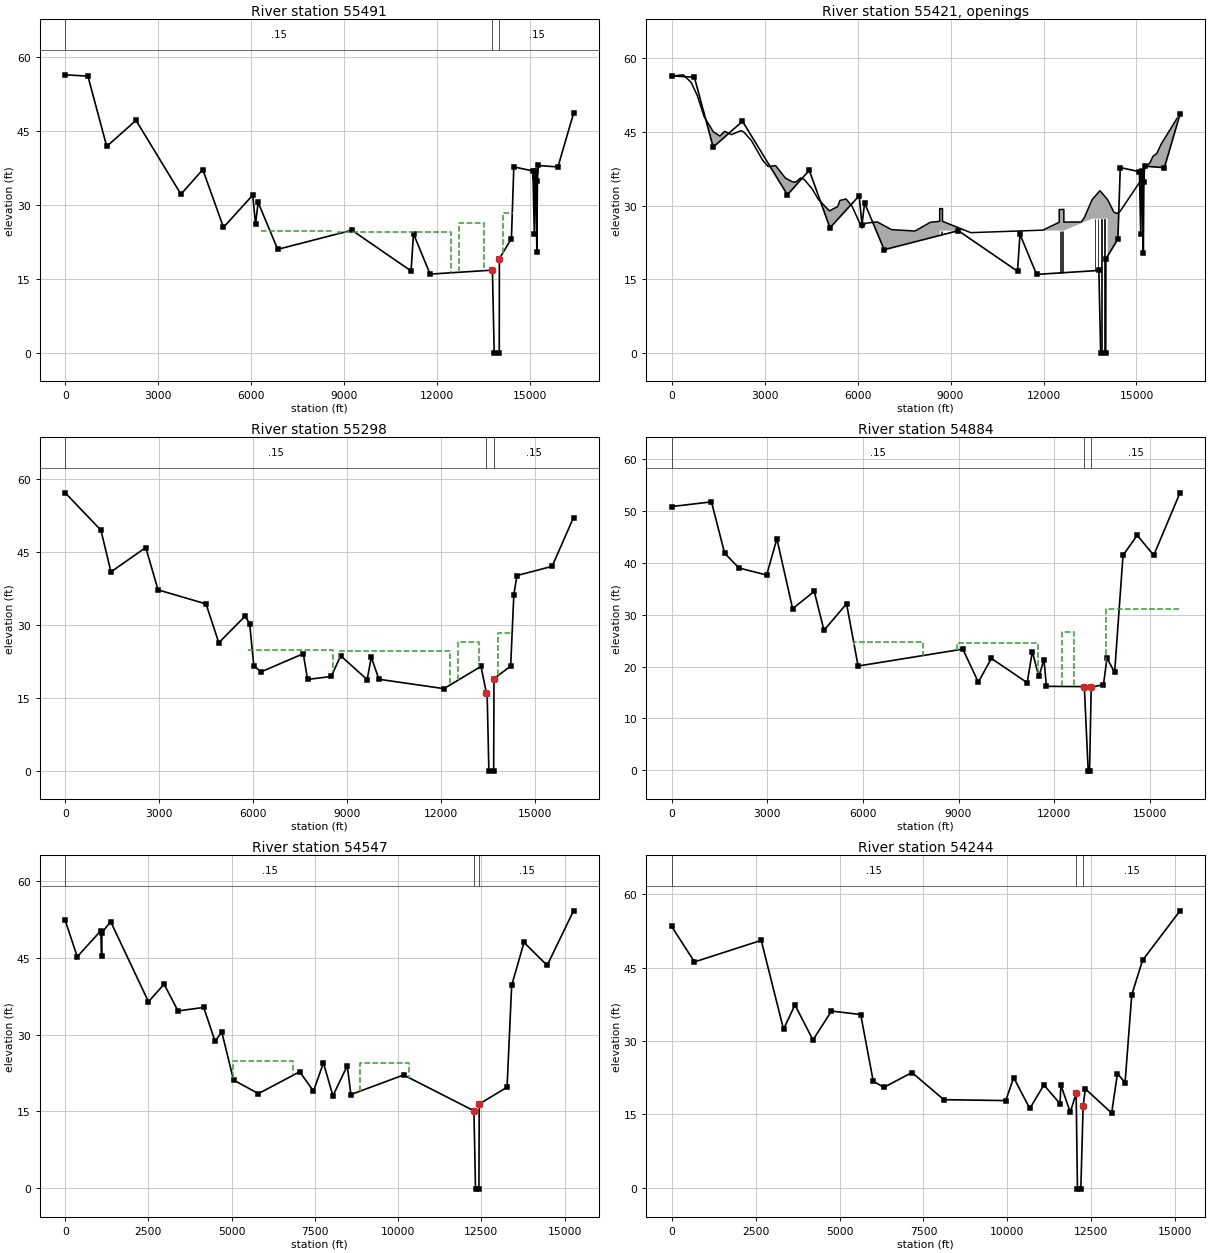
Type RM Length L Ch R = 1 ,55491   ,200.8,200.8,200.8
BEGIN DESCRIPTION:
Black River 118.0
END DESCRIPTION:
XS GIS Cut Line= 6
2393432.63647658642101.5866659632392829.92725322639252.634513813
2391255.92538498636193.9854142632392147.82003084 632121.22054437
2393705.31246644628597.7499796052393304.95174855626641.986105873
#Sta/Elev= 30
       0   56.43   732.7   56.17  1339.8    41.9  2285.4   47.19  3735.4   32.19
  4440.1    37.2    5108   25.47  6051.6   32.01  6142.4   26.12    6226   30.53
  6858.8   21.01  9251.8   24.89 11161.5   16.62 11240.6   24.16 11776.4   15.98
 13787.116.7875313845.22    -.0614007.88    -.06 14012.6   19.12 14400.8   23.18
 14477.7   37.75   15094   36.91 15139.9   24.16   15163   35.75 15186.5   36.96
 15221.3   20.42 15239.6   34.88 15260.2   38.03 15901.6   37.73 16405.1   48.59
#Mann= 3 ,0,0
       0     .15       0 13787.1     .05       0 14012.6     .15       0
#XS Ineff= 4 ,-1
    6310    8590   24.82    8800   12447   24.49   12717   13510    26.4
   14130   14448   28.38
Permanent Ineff=
       F       F       F       F
Bank Sta=13787.1,14012.6
XS Rating Curve= 0 ,0
Exp/Cntr=0.5,0.3

Type RM Length L Ch R = 4 ,55421   ,,,
Node Name=Bridge S-45-30
Bridge Culvert-0,0,0,0, 0
Deck Dist Width WeirC Skew NumUp NumDn MinLoCord MaxHiCord MaxSubmerge Is_Ogee
65,27.5,2.6,0, 60, 60, , , 0.98, 0, 2,2,,
       0   375.1   627.2   822.2  1044.1  1344.2  1555.1  1709.7  1928.2  2234.2
  2328.3  2570.3    2931  3109.9  3354.2  3671.1  3884.9    3991  4164.6  4279.7
  4537.6  4729.6  5091.6  5357.5    5430    5627    5821    6140    6260    6628
    7094    7854    8347    8650    8650    8740    8740    9651   11982   12507
   12507   12657   12657   13220   13320   13570   13570   13820   14070   14070
   14270   14370   14470   15120   15176 15443.8 15531.2 15655.4 15805.9 16312.9
   56.41   56.65   55.12    52.5   48.17   45.04   44.17   45.13   44.46   45.27
      45   43.28   39.31   37.96   38.15   35.61   34.89   34.75   35.65   35.31
   33.37   31.31   28.92   29.81   31.05   31.35   29.89   25.42    26.4   26.69
   25.11   24.82    26.6    26.8  29.383  29.383    26.8   24.49      25   26.61
  29.193  29.223   26.64   26.67   27.62   31.23   31.23   33.04   31.21   31.21
   28.68   28.38   28.82   34.92   36.91   38.81   40.04   40.62   42.63   47.82
                                                                                
                                                                                
                                                                                
                                   24.91   24.91
   24.91   24.91                                   27.33   27.33   27.33
                                                                                
       0   375.1   627.2   822.2  1044.1  1344.2  1555.1  1709.7  1928.2  2328.3
  2570.3  3109.9  3354.2  3671.1  3884.9  4164.6  4279.7  4729.6  5091.6  5357.5
    5430    5627    5821    6140    6260    6628    7094    7854    8347    8610
    8610    8700    8700    9651   11982   12184   12333   12333   12483   12483
   12920   13275   13275   13525   13775   13775   13970   14170   14820   14870
   14970   15176   15309 15554.7 15708.8 15719.1 15745.9 15752.6 15960.6 16312.9
   56.41   56.65   55.12    52.5   48.17   45.04   44.17   45.13   44.46      45
   43.28   37.96   38.15   35.61   34.89   35.65   35.31   31.31   28.92   29.81
   31.05   31.35   29.89   25.42    26.4   26.69   25.11   24.82    26.6    26.8
  29.383  29.383    26.8   24.49      25   25.44   26.61  29.193  29.223   26.64
   26.67   31.23   31.23   33.04   31.21   31.21   28.68   28.82   34.92   36.91
   36.99   38.68   38.81      42   42.69   44.26   44.13   45.69   47.25   47.82
                                                                                
                                                                                
                                                                                
   24.91   24.91                                           24.91   24.91
                   27.33   27.33   27.33
                                                                                
Pier Skew, UpSta & Num, DnSta & Num=  ,8680, 2 ,8640, 2 , 0 , 0 , 0 ,,
     1.5     1.5
       0   24.91
     1.5     1.5
       0   24.91
Pier Skew, UpSta & Num, DnSta & Num=  ,8710, 2 ,8670, 2 , 0 , 0 , 0 ,,
     1.5     1.5
       0   24.91
     1.5     1.5
       0   24.91
Pier Skew, UpSta & Num, DnSta & Num=  ,12537, 2 ,12363, 2 , 0 , 0 , 0 ,,
     1.5     1.5
       0   24.91
     1.5     1.5
       0   24.91
Pier Skew, UpSta & Num, DnSta & Num=  ,12567, 2 ,12393, 2 , 0 , 0 , 0 ,,
     1.5     1.5
       0   24.91
     1.5     1.5
       0   24.91
Pier Skew, UpSta & Num, DnSta & Num=  ,12597, 2 ,12423, 2 , 0 , 0 , 0 ,,
     1.5     1.5
       0   24.91
     1.5     1.5
       0   24.91
Pier Skew, UpSta & Num, DnSta & Num=  ,12627, 2 ,12453, 2 , 0 , 0 , 0 ,,
     1.5     1.5
       0   24.91
     1.5     1.5
       0   24.91
Pier Skew, UpSta & Num, DnSta & Num=  ,13670, 2 ,13375, 2 , 0 , 0 , 0 ,,
       8       8
     -20      30
       8       8
     -20      30
Pier Skew, UpSta & Num, DnSta & Num=  ,13770, 2 ,13475, 2 , 0 , 0 , 0 ,,
       8       8
     -20      30
       8       8
     -20      30
Pier Skew, UpSta & Num, DnSta & Num=  ,13870, 2 ,13575, 2 , 0 , 0 , 0 ,,
       8       8
     -20      30
       8       8
     -20      30
Pier Skew, UpSta & Num, DnSta & Num=  ,13970, 2 ,13675, 2 , 0 , 0 , 0 ,,
       8       8
     -20      30
       8       8
     -20      30
Abutment Skew #Up #Dn= , 2 , 2
    8650    8700
   24.91    -.09
    8610    8660
   24.91    -.09
Abutment Skew #Up #Dn= , 2 , 2
    8690    8740
    -.09   24.91
    8650    8700
    -.09   24.91
Abutment Skew #Up #Dn= , 2 , 2
   12507   12557
   24.91    -.09
   12333   12383
   24.91    -.09
Abutment Skew #Up #Dn= , 2 , 2
   12607   12657
    -.09   24.91
   12433   12483
    -.09   24.91
Abutment Skew #Up #Dn= , 3 , 3
   13570   13572   13592
   25.33   25.33    15.2
   13275   13277   13297
   25.33   25.33    15.2
Abutment Skew #Up #Dn= , 3 , 3
   14048   14068   14070
    15.2   25.33   25.33
   13753   13773   13775
    15.2   25.33   25.33
BR Coef=-1 , 1 , 0 ,, 0 ,,,0.8,0,2,0,
WSPro=,,,, 1 ,,,, 0 ,,,, 0 ,,,,-1 ,-1 ,-1 , 0 , 0 , 0 , 0 , 0
BR Coef=-1 ,-1 , 0 ,, 0 ,,,0.8,0,2,0,
WSPro=,,,, 1 ,,,, 0 ,,,, 0 ,,,,-1 ,-1 ,-1 , 0 , 0 , 0 , 0 , 0
BR Coef=-1 ,-1 , 0 ,, 0 ,,,0.8,0,1.2,0,
WSPro=,,,, 1 ,,,, 0 ,,,, 0 ,,,,-1 ,-1 ,-1 , 0 , 0 , 0 , 0 , 0
BC Mult= 3 ,0,10990,0,10990
BC Mult= 3 ,10490,13270,10490,13070
BC Mult= 3 ,12800,16406,12600,16229
BC Design=,, 0 ,, 0 ,,,,,,
BC Use User HTab Curves=0
BC User HTab FreeFlow(D)= 0

Type RM Length L Ch R = 1 ,55298   ,413.5,413.5,413.5
XS GIS Cut Line= 6
2393630.39708732641978.3491041592393038.05879676639382.142979573
2391507.54803687636191.8580229632392326.77242443632183.224190622
2393881.00177459628635.7356667982393455.58703222626647.612137168
#Sta/Elev= 30
       0   57.07  1140.5   49.39  1460.2   40.83  2570.8   45.84  2963.5   37.14
  4495.6   34.26  4903.1   26.28  5743.7   31.75    5889   30.21  6020.3   21.57
    6255   20.31  7600.3   24.03  7736.8   18.75  8495.2   19.36  8793.5   23.62
  9638.7   18.71  9771.3   23.29 10016.6   18.78 12089.7   16.86 13273.4   21.42
 13448.5   15.88 13470.1   15.7213525.62    -.08 13678.3    -.08 13688.3   18.91
 14221.2   21.49 14321.8   36.13 14422.5   40.09 15544.4   41.97   16228      52
#Mann= 3 ,0,0
       0     .15       0 13448.5     .05       0 13688.3     .15       0
#XS Ineff= 4 ,-1
    5850    8560   24.82    8750   12283   24.49   12533   13225    26.4
   13825   14306   28.38
Permanent Ineff=
       F       F       F       F
Bank Sta=13448.5,13688.3
XS Rating Curve= 0 ,0
Exp/Cntr(USF)=0,0
Exp/Cntr=0.5,0.3

Type RM Length L Ch R = 1 ,54884   ,337.1,337.1,337.1
XS GIS Cut Line= 6
2394322.68866886641777.0050034342391998.80223099636205.549074871
2393375.37076971631506.1219100392393873.98960343629768.717871241
2394107.03722327629266.5292095492393630.75489178626654.418297743
#Sta/Elev= 30
       0   50.86  1248.8   51.77  1661.7   41.86  2112.3   39.01  2980.9   37.66
  3300.9   44.64    3795   31.17  4473.2    34.5  4779.7      27  5487.2   32.12
  5849.8   20.11  9135.6   23.37  9621.9      17 10031.3   21.58 11155.7   16.89
 11316.1   22.88 11520.9   18.09 11681.4   21.31 11759.9   16.19 12947.9   16.14
13069.19    -.1613112.41    -.16 13163.216.00946 13548.6   16.52 13659.3   21.62
 13898.7   18.89 14162.2   41.47   14607   45.32 15126.2   41.47 15949.9   53.51
#Mann= 3 ,0,0
       0     .15       0 12947.9     .05       0 13163.2     .15       0
#XS Ineff= 4 ,-1
    5727    7890   24.82    8942   11489   24.49   12239   12610   26.59
   13640 15949.9    31.2
Permanent Ineff=
       F       F       F       F
Bank Sta=12947.9,13163.2
XS Rating Curve= 0 ,0
Exp/Cntr(USF)=0,0
Exp/Cntr=0.5,0.3

Type RM Length L Ch R = 1 ,54547   ,303.1,303.1,303.1
BEGIN DESCRIPTION:
Black River 116.0
END DESCRIPTION:
XS GIS Cut Line= 6
2395142.88186549641258.0851607682392912.17520342636170.551597593
2394329.30743497629608.2887355732394366.78837151629469.897585245
2394114.36218134628404.560556833 2393806.5398177626669.562269123
#Sta/Elev= 30
       0   52.33   362.3   45.25  1070.8   50.33  1093.1   45.44  1101.8   49.95
  1365.3   52.11  2500.9   36.44  2970.2   39.87  3389.4   34.63  4160.6   35.33
    4501    28.7  4702.6   30.53  5056.2   21.12  5802.6   18.46  7044.6   22.74
  7457.4   18.95  7756.2   24.48  8041.5   18.03  8471.1    23.9  8581.9   18.28
   10165   22.11   1227715.1011712324.66    -.2212426.83    -.22 12435.9   16.42
 13272.1   19.72 13410.7   39.63 13781.3   48.04 14476.8   43.54 15268.9   54.22
#Mann= 3 ,0,0
       0     .15       0   12277     .05       0 12435.9     .15       0
#XS Ineff= 2 ,-1
    5040    6837   24.82    8862   10320   24.49
Permanent Ineff=
       F       F
Bank Sta=12277,12435.9
XS Rating Curve= 0 ,0
Exp/Cntr=0.5,0.3

Type RM Length L Ch R = 1 ,54244   ,445.5,445.5,445.5
XS GIS Cut Line= 5
2396872.84860439641156.5932441342394302.70123852635856.864856662
2394631.17298708629875.2214356442394661.59984378629291.579002426
2393989.44291832626700.974185548
#Sta/Elev= 30
       0   53.42   678.9   46.17  2667.5   50.57  3331.9   32.41  3671.8   37.38
  4208.5   30.21  4759.1   36.12  5630.6   35.42  6004.5   21.77  6323.2   20.53
  7157.8   23.56  8106.8   18.01  9950.8   17.83 10187.3   22.52 10667.1   16.21
 11087.6   21.02 11567.4   17.19 11593.7   20.97   11873   15.47 12048.719.27743
12086.87    -.2712187.22    -.27 12256.5   16.82   12323   20.22 13105.4   15.27
 13277.6   23.35 13504.9    21.5 13704.8   39.47 14026.8   46.51 15141.5   56.61
#Mann= 3 ,0,0
       0     .15       0 12048.7     .05       0 12256.5     .15       0
Bank Sta=12048.7,12256.5
XS Rating Curve= 0 ,0
Exp/Cntr(USF)=0,0
Exp/Cntr=0.3,0.1