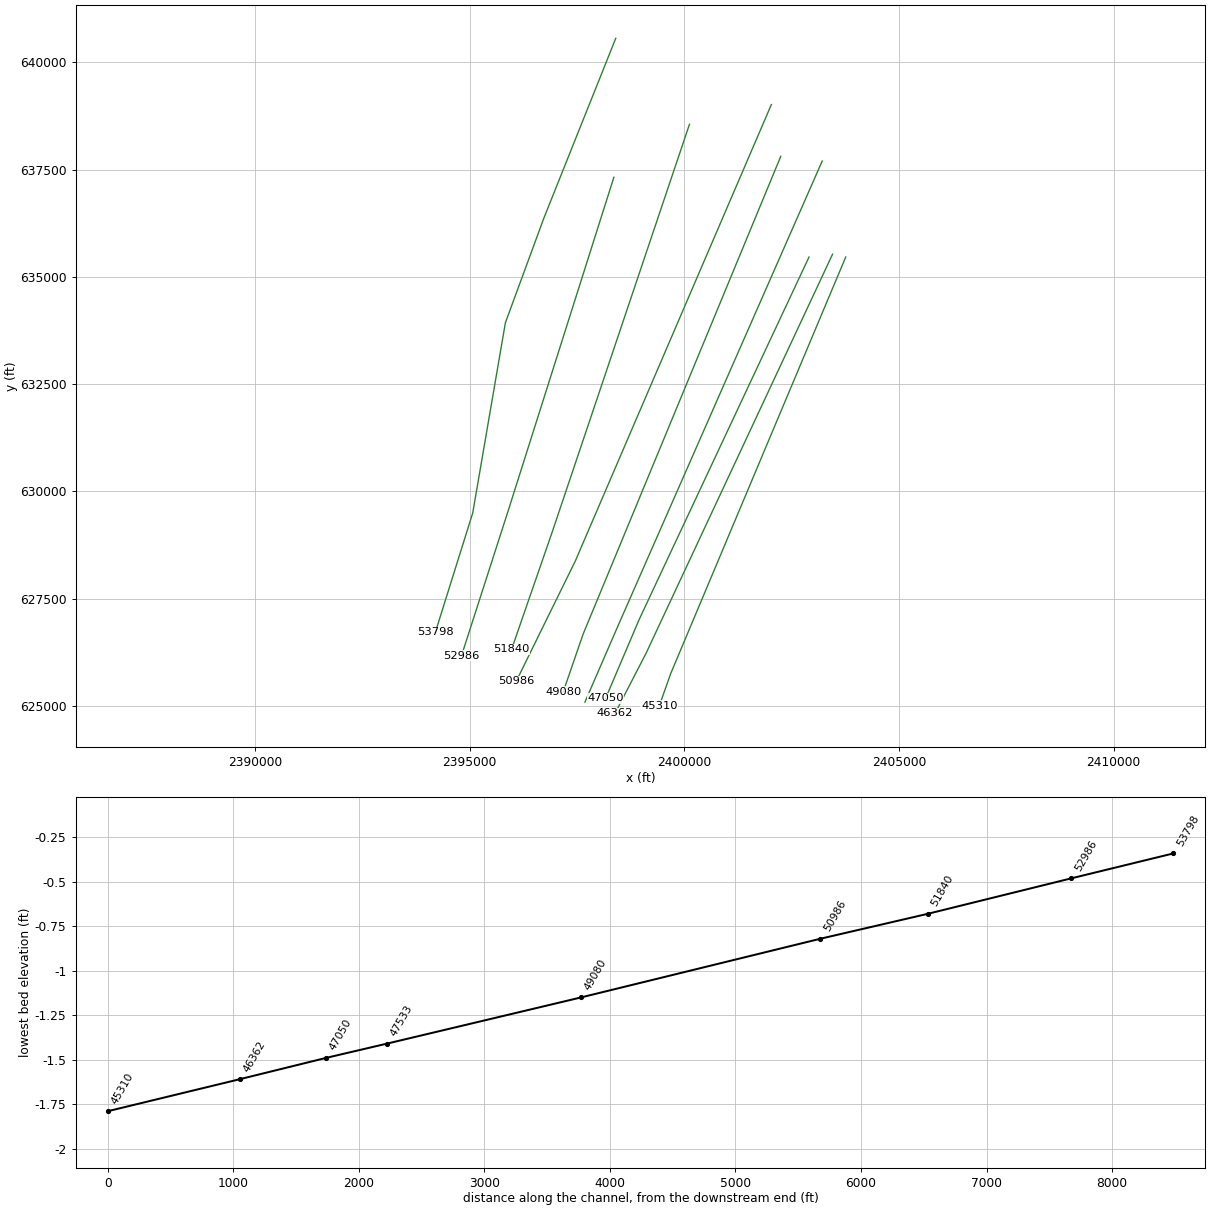
HEC-RAS study BlackRiver.prj: S-45-30 over Black River

--- BlackRiver.g06 (geometry) --- (continued)

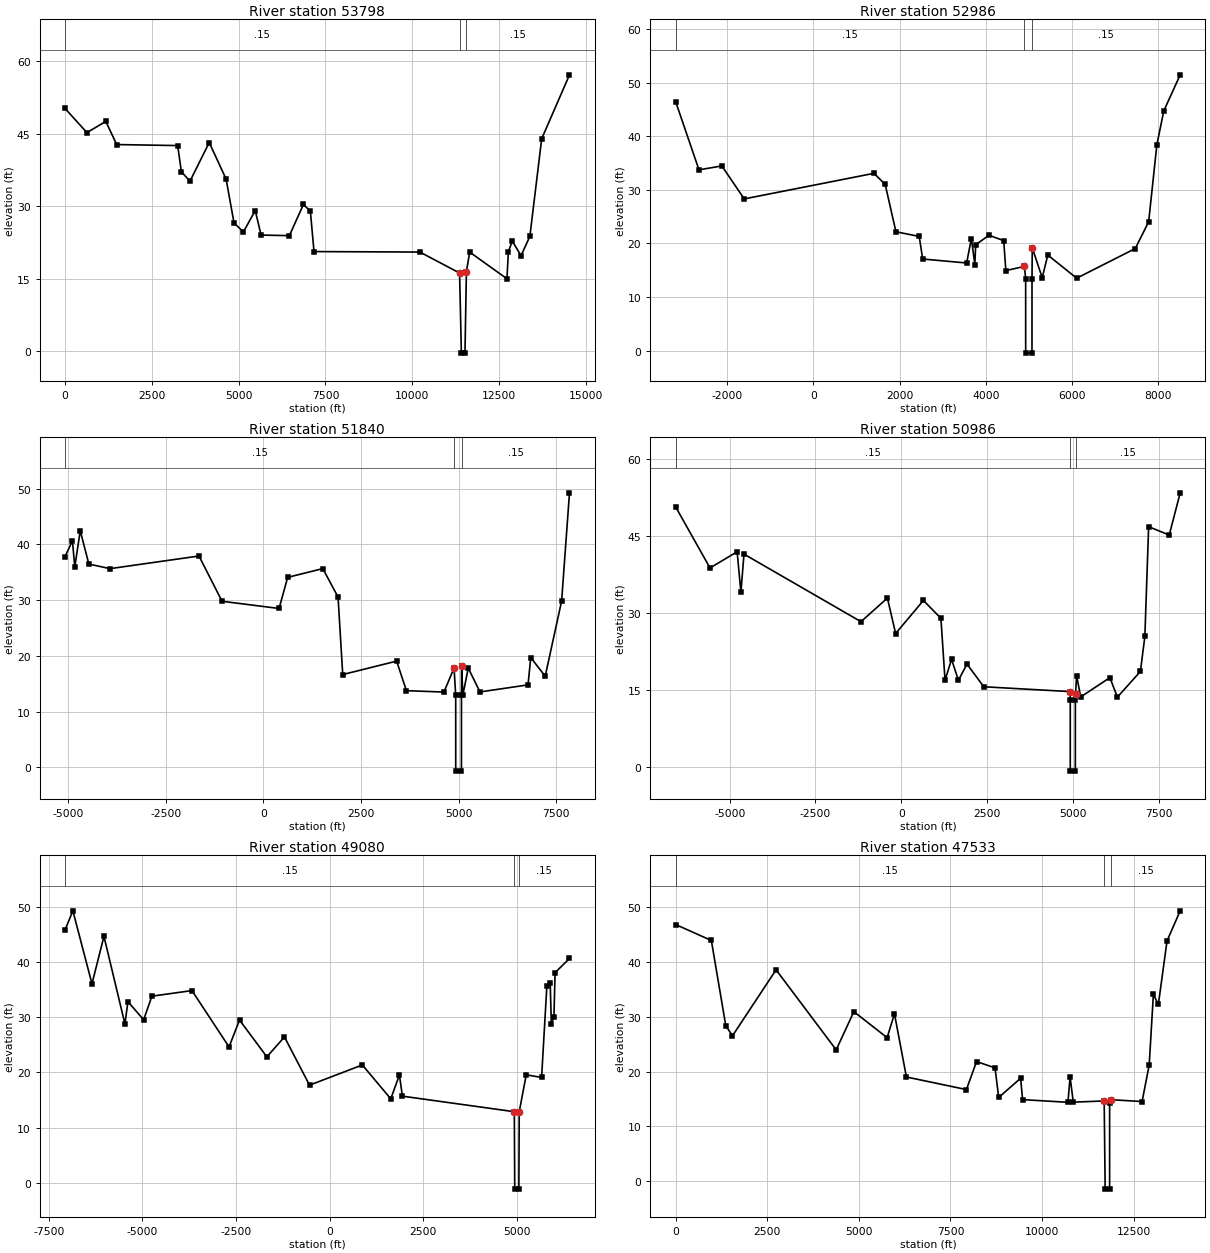
Type RM Length L Ch R = 1 ,53798   ,812.3,812.3,812.3
BEGIN DESCRIPTION:
Black River 115.0
END DESCRIPTION:
XS GIS Cut Line= 5
2398399.90993523640563.111017029 2396726.4920029636375.113978397
2395829.16029188633933.0097724552395068.30969503629499.606685864
      2394197.38       626717.25
#Sta/Elev= 30
       0   50.19   629.9    45.2    1174   47.51  1488.5   42.73  3243.6   42.52
  3350.4   37.13  3597.7   35.16  4152.4   43.15  4638.6   35.59  4867.1   26.51
  5137.1    24.7  5477.5   29.11  5645.2   24.04  6459.6   23.92  6865.1   30.36
  7064.3   28.96  7169.6   20.63   10219   20.53 11360.8    16.211412.04    -.34
11515.82    -.34 11557.2    16.5 11651.7   20.52 12724.3   15.02 12765.5   20.61
   12879    22.8 13129.9   19.77 13384.3   23.78 13724.7   43.92 14525.4   57.13
#Mann= 3 ,0,0
       0     .15       0 11360.8     .05       0 11557.2     .15       0
Bank Sta=11360.8,11557.2
XS Rating Curve= 0 ,0
Exp/Cntr=0.3,0.1

Type RM Length L Ch R = 1 ,52986   ,1145.6,1145.6,1145.6
BEGIN DESCRIPTION:
Black River 114.0
END DESCRIPTION:
XS GIS Cut Line= 3
      2398356.31       637324.63      2395882.35       629514.07
      2394806.51       626171.12
#Sta/Elev= 30
   -3193   46.46   -2653   33.76   -2123   34.49   -1603   28.33    1407   33.11
    1667   31.04    1917   22.19    2457   21.32    2537    17.1    3557   16.36
    3667   20.93    3747   16.07    3767   19.77    4077   21.54    4417   20.53
    4467   14.94    4897   15.72  4926.4   13.46  4926.8    -.48  5073.2    -.48
  5073.6   13.46    5080   19.19    5310   13.61    5440   17.84    6110   13.52
    7470   19.06    7780   24.05    7970   38.41    8130   44.75  8511.8   51.51
#Mann= 3 ,0,0
   -3193     .15       0    4897     .05       0    5080     .15       0
Bank Sta=4897,5080
XS Rating Curve= 0 ,0
Exp/Cntr=0.3,0.1

Type RM Length L Ch R = 1 ,51840   ,854.4,854.4,854.4
BEGIN DESCRIPTION:
Black River 113.0
END DESCRIPTION:
XS GIS Cut Line= 3
      2400116.49       638558.21      2396914.12       629038.84
      2395975.01       626325.01
#Sta/Elev= 30
 -5075.8   37.79 -4885.8   40.62 -4825.8   35.92 -4685.8   42.43 -4465.8   36.46
 -3925.8   35.63 -1645.8    37.9 -1055.8   29.78   404.2   28.49   624.2   34.07
  1524.2   35.64  1914.2   30.54  2034.2   16.64  3414.2   19.05  3664.2   13.75
  4624.2    13.5  4884.2    17.8  4926.4   12.91  4926.8    -.68  5073.2    -.68
  5073.6   12.91  5077.8   18.26  5107.8   12.91  5247.8   17.79  5547.8   13.52
  6777.8   14.79  6847.8   19.69  7217.8   16.34  7637.8   29.82  7839.5   49.23
#Mann= 3 ,0,0
 -5075.8     .15       0  4884.2     .05       0  5077.8     .15       0
Bank Sta=4884.2,5077.8
XS Rating Curve= 0 ,0
Exp/Cntr=0.3,0.1

Type RM Length L Ch R = 1 ,50986   ,1905.9,1905.9,1905.9
BEGIN DESCRIPTION:
Black River 112.0
END DESCRIPTION:
XS GIS Cut Line= 3
      2402024.75       639018.84      2397459.67       628382.84
      2396080.62       625573.25
#Sta/Elev= 30
 -6574.3   50.71 -5574.3   38.82 -4784.3   41.98 -4674.3    34.1 -4584.3   41.52
 -1174.3   28.34  -404.3   32.95  -164.3   26.03   645.7   32.48  1155.7      29
  1275.7    16.9  1465.7   20.99  1665.7   16.91  1915.7   20.06  2405.7   15.64
  4915.7    14.7  4925.8   13.04  4926.2    -.82  5073.8    -.82  5074.3   13.04
    5080   14.26    5110    17.8    5230   13.66    6080   17.42    6300   13.62
    6970   18.63    7100   25.46    7210   46.88    7810   45.24  8129.8   53.48
#Mann= 3 ,0,0
 -6574.3     .15       0  4915.7     .05       0    5080     .15       0
Bank Sta=4915.7,5080
XS Rating Curve= 0 ,0
Exp/Cntr=0.3,0.1

Type RM Length L Ch R = 1 ,49080   ,1546.5,1546.5,1546.5
BEGIN DESCRIPTION:
Black River 110.0
END DESCRIPTION:
XS GIS Cut Line= 3
       2402244.1       637812.49      2397637.94       626669.97
      2397177.32       625331.99
#Sta/Elev= 30
   -7065   45.77   -6855   49.23   -6345   36.02   -6025   44.61   -5465   28.75
   -5385   32.79   -4965   29.51   -4745   33.78   -3675   34.79   -2685   24.59
   -2405   29.46   -1675    22.8   -1205    26.4    -535   17.67     875   21.33
    1635   15.19    1865   19.53    1945   15.68  4933.612.86433 4944.99   -1.15
 5054.68   -1.15    5065 12.8808    5252   19.54    5662   19.07    5802   35.55
    5892   36.16    5922    28.8    5992   30.07    6022   38.03  6407.1   40.61
#Mann= 3 ,0,0
   -7065     .15       0  4933.6     .05       0    5065     .15       0
Bank Sta=4933.6,5065
XS Rating Curve= 0 ,0
Exp/Cntr=0.3,0.1

Type RM Length L Ch R = 1 ,47533   ,483.4,483.4,483.4
BEGIN DESCRIPTION:
Black River 109.0
END DESCRIPTION:
XS GIS Cut Line= 3
      2403209.17       637702.76      2398471.43       626911.25
      2397681.81       625090.72
#Sta/Elev= 30
       0   46.77   972.7   43.87  1366.8   28.35  1549.6   26.51  2739.2   38.53
  4380.2   23.95  4862.7   30.91  5770.5   26.17  5971.1   30.52  6296.9   19.01
  7934.7   16.72  8211.7   21.82  8715.8   20.67  8816.1   15.28  9414.5   18.78
  9468.2   14.89 10706.6    14.4 10765.3   19.04 10851.3   14.43 11695.314.64683
   11722   -1.41 11843.7   -1.41 11843.814.22254 11869.6   14.88 12730.1   14.54
 12923.7   21.18 13038.2   34.05 13174.1   32.22   13411    43.8 13770.1   49.27
#Mann= 3 ,0,0
       0     .15       0 11695.3     .05       0 11869.6     .15       0
Bank Sta=11695.3,11869.6
XS Rating Curve= 0 ,0
Exp/Cntr=0.3,0.1

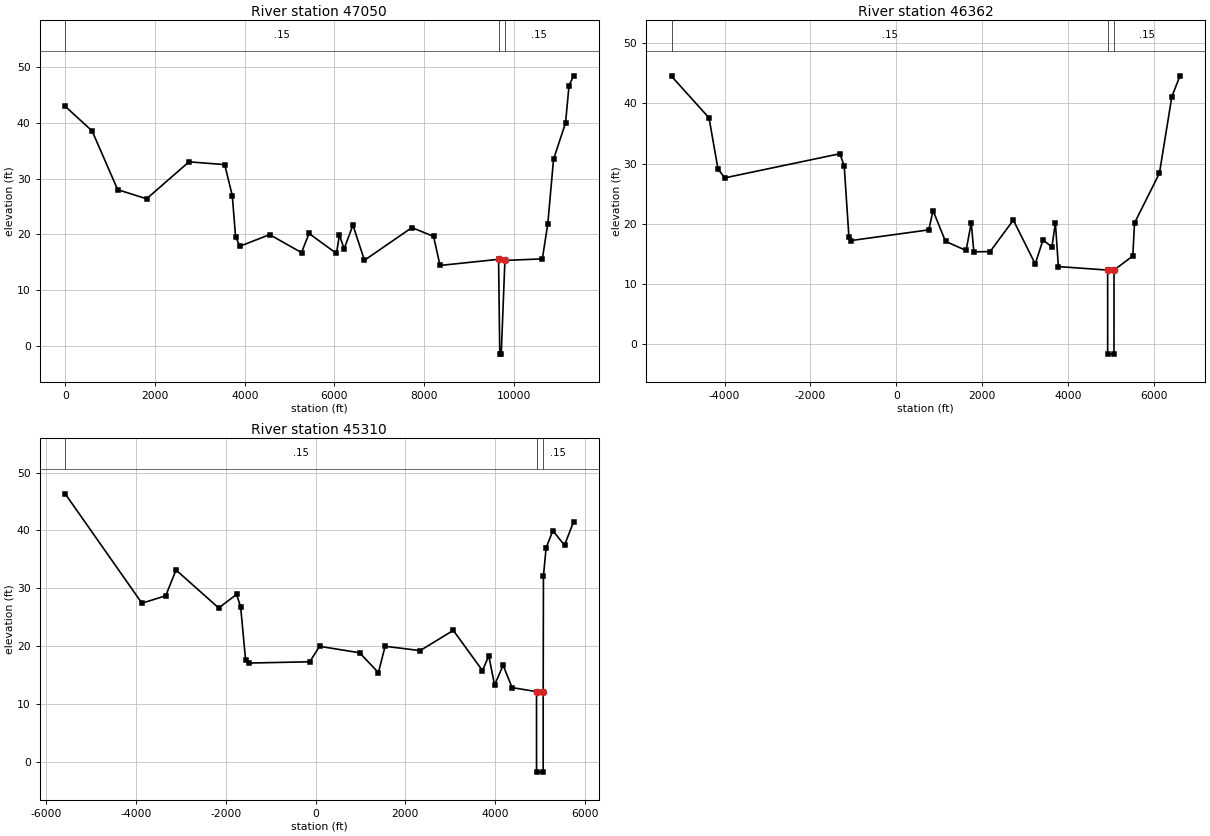
Type RM Length L Ch R = 1 ,47050   ,688.4,688.4,688.4
BEGIN DESCRIPTION:
Black River 108.0
END DESCRIPTION:
XS GIS Cut Line= 5
      2402902.12       635465.552398988.81776435627108.343608596
       2398958.7         627043.2398928.09864715626975.228620875
      2398164.35       625178.45
#Sta/Elev= 30
       0   42.94   599.8   38.52  1168.6      28  1813.4   26.36  2758.9   32.99
  3554.1   32.49  3722.6   26.95  3795.9    19.6  3890.5   17.85  4555.8   19.94
  5265.9   16.71  5432.5   20.15  6044.7   16.56    6110   19.86    6215    17.4
  6411.3   21.64  6667.9   15.34  7725.7    21.2  8207.5   19.62  8352.4   14.41
  9656.715.50992 9683.07   -1.49 9715.96   -1.49  9797.6   15.31 10631.8   15.59
   10753   21.88 10881.3   33.45 11148.8   39.97 11226.3   46.65 11326.7   48.41
#Mann= 3 ,0,0
       0     .15       0  9656.7     .05       0  9797.6     .15       0
Bank Sta=9656.7,9797.6
XS Rating Curve= 0 ,0
Exp/Cntr=0.3,0.1

Type RM Length L Ch R = 1 ,46362   ,1051.4,1051.4,1051.4
BEGIN DESCRIPTION:
Black River 107.0
END DESCRIPTION:
XS GIS Cut Line= 3
      2403450.44       635531.29      2399107.52       626231.29
      2398383.68       624827.48
#Sta/Elev= 30
 -5231.9   44.45 -4361.9   37.58 -4151.9   29.06 -3991.9   27.63 -1311.9   31.63
 -1211.9   29.58 -1101.9   17.78 -1061.9   17.22   758.1      19   858.1   22.19
  1148.1   17.09  1628.1   15.58  1748.1    20.2  1808.1   15.36  2188.1    15.4
  2728.1   20.62  3238.1   13.35  3418.1    17.3  3628.1   16.19  3708.1   20.19
  3778.1   12.91  4925.8   12.33  4926.2   -1.61  5073.8   -1.61  5074.3   12.33
  5512.2   14.67  5552.2   20.14  6132.2   28.39  6422.2   41.12  6611.6   44.55
#Mann= 3 ,0,0
 -5231.9     .15       0  4925.8     .05       0  5074.3     .15       0
Bank Sta=4925.8,5074.3
XS Rating Curve= 0 ,0
Exp/Cntr=0.3,0.1

Type RM Length L Ch R = 1 ,45310   ,589.8,589.8,589.8
BEGIN DESCRIPTION:
Black River 106.0
END DESCRIPTION:
XS GIS Cut Line= 3
      2403757.52        635465.5       2399677.8       625748.74
       2399414.6         625003.
#Sta/Elev= 30
 -5578.8   46.33 -3868.8   27.42 -3338.8    28.7 -3108.8   33.16 -2158.8    26.6
 -1758.8   28.94 -1668.8   26.77 -1558.8    17.6 -1478.8   17.07  -128.8   17.29
    91.2   19.96   981.2   18.85  1401.2   15.42  1551.2   19.97  2331.2   19.22
  3071.2   22.72  3721.2   15.76  3861.2   18.31  3991.2   13.27  4181.2   16.69
  4381.2   12.82  4925.7   12.14  4926.1   -1.79  5073.9   -1.79  5074.3   12.14
  5079.7   32.14  5139.7   37.01  5289.7   39.95  5549.7   37.44  5750.5   41.49
#Mann= 3 ,0,0
 -5578.8     .15       0  4925.7     .05       0  5074.3     .15       0
Bank Sta=4925.7,5074.3
XS Rating Curve= 0 ,0
Exp/Cntr=0.3,0.1