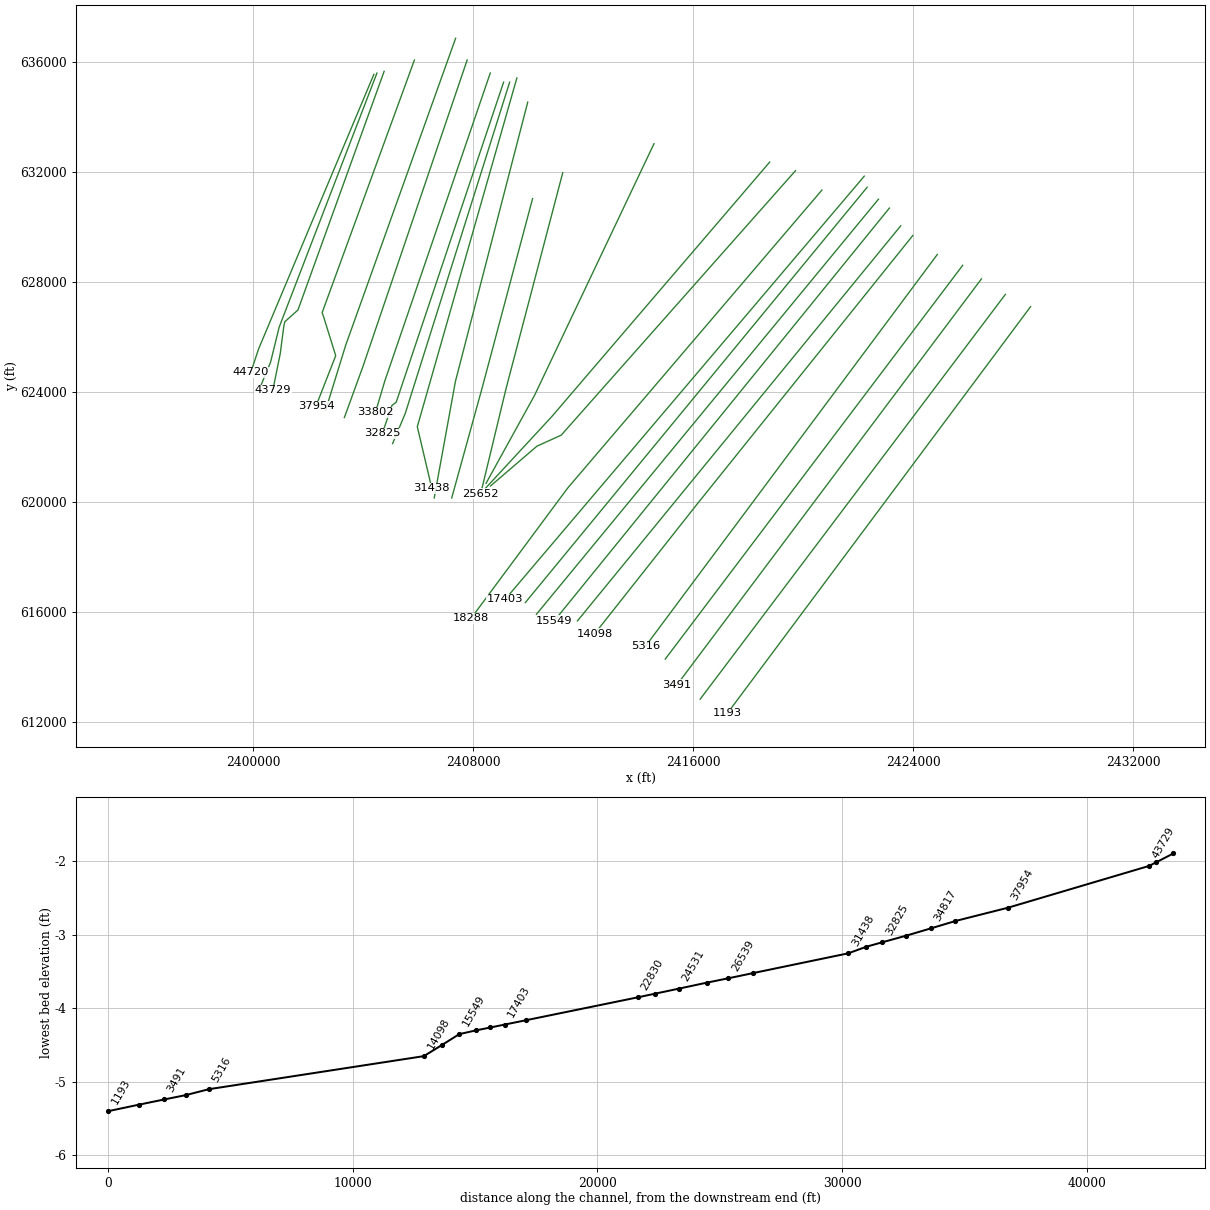
HEC-RAS study BlackRiver.prj: S-45-30 over Black River

--- BlackRiver.g06 (geometry) --- (continued)

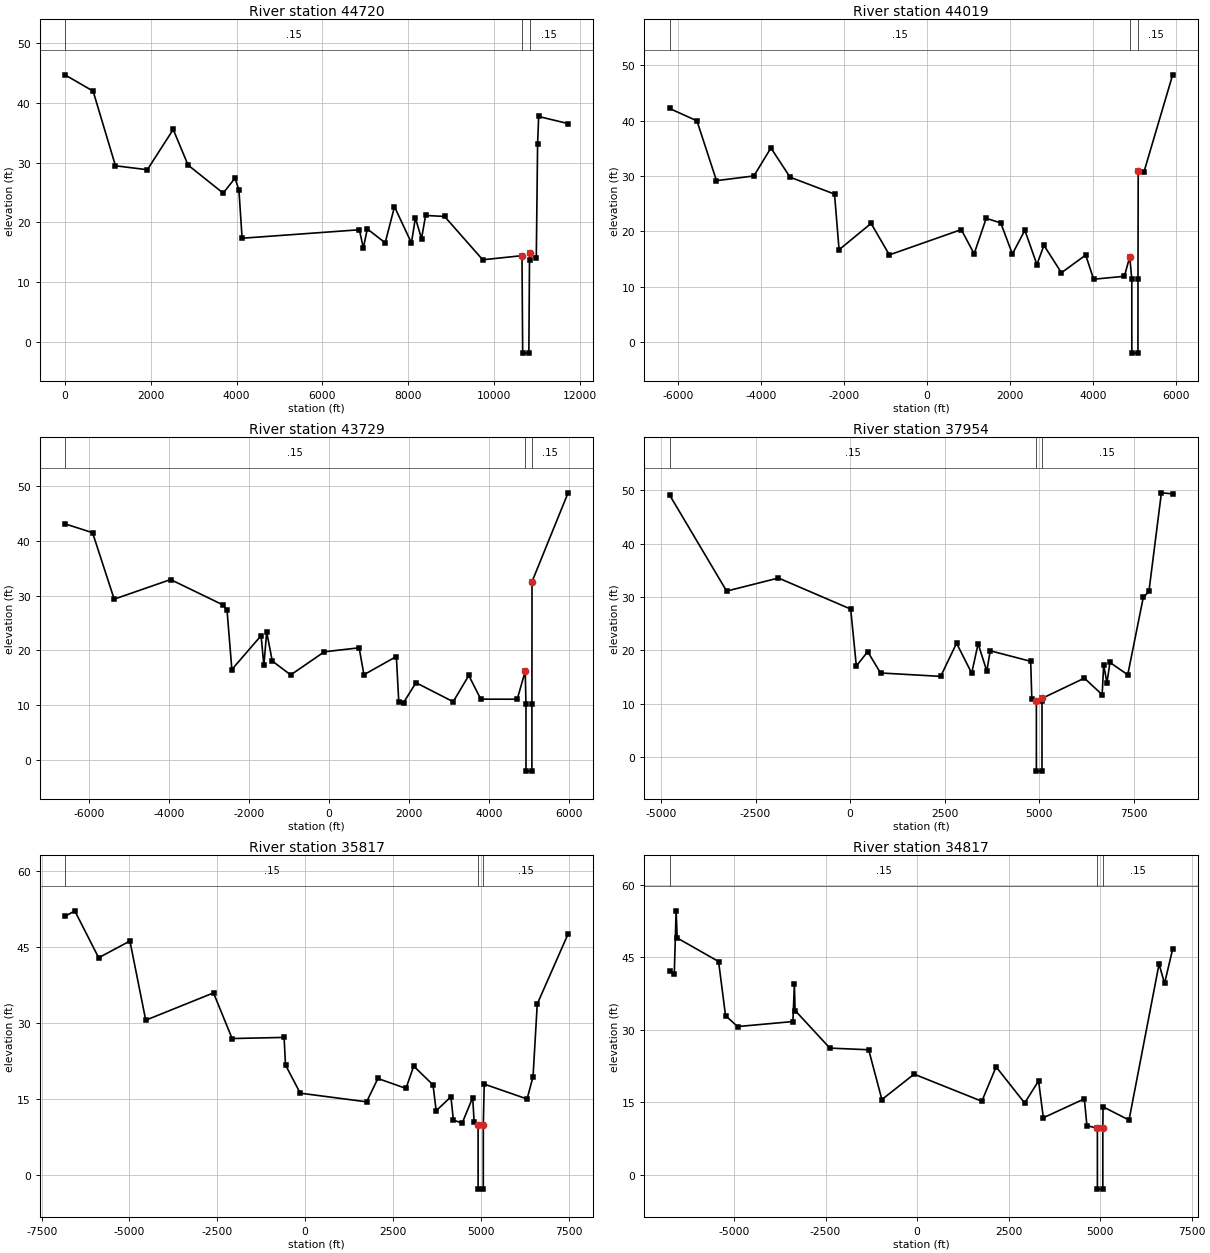
Type RM Length L Ch R = 1 ,44720   ,701.5,701.5,701.5
BEGIN DESCRIPTION:
Black River 105.0
END DESCRIPTION:
XS GIS Cut Line= 3
      2404393.62       635553.26      2400204.22       625573.27
      2399919.09       624717.88
#Sta/Elev= 30
       0   44.74     656   42.01  1177.3    29.5  1919.7   28.84  2523.1   35.58
    2869   29.62  3687.4   24.92  3962.5   27.42  4053.8   25.49  4128.6   17.36
  6861.3   18.78    6954   15.73  7046.3   18.92  7462.6   16.59  7679.6   22.64
  8074.3   16.57  8166.7   20.75  8309.4    17.3  8405.5   21.18  8846.7   21.01
  9735.9   13.75 10650.7   14.44 10667.2   -1.89 10810.9   -1.89 10826.1   13.79
 10838.9   14.92 10984.3   14.06 11014.8   33.15 11039.5   37.76 11725.3   36.57
#Mann= 3 ,0,0
       0     .15       0 10650.7     .05       0 10838.9     .15       0
Bank Sta=10650.7,10838.9
XS Rating Curve= 0 ,0
Exp/Cntr=0.3,0.1

Type RM Length L Ch R = 1 ,44019   ,290.3,290.3,290.3
BEGIN DESCRIPTION:
Black River 104.0
END DESCRIPTION:
XS GIS Cut Line= 4
2404504.78718518635599.2177248742400951.46718518626364.967724874
2400640.74718518625099.0577248742400293.45718518624259.337724874
#Sta/Elev= 30
 -6197.8   42.22 -5537.8   39.98 -5067.8   29.17 -4167.8   30.02 -3757.8   35.08
 -3297.8    29.8 -2227.8   26.74 -2117.8   16.68 -1347.8   21.44  -907.8   15.75
   822.2   20.32  1132.2   15.95  1422.2   22.36  1772.2   21.53  2052.2   15.91
  2352.2    20.2  2642.2   14.01  2812.2   17.47  3232.2   12.52  3816.5   15.72
  4006.5   11.35  4746.5   11.88  4876.5   15.39  4925.7   11.33  4926.1   -2.01
  5073.9   -2.01  5074.3   11.33  5079.930.91173    5220   30.79  5908.7    48.3
#Mann= 3 ,0,0
 -6197.8     .15       0  4876.5     .05       0  5079.9     .15       0
Bank Sta=4876.5,5079.9
XS Rating Curve= 0 ,0
Exp/Cntr=0.3,0.1

Type RM Length L Ch R = 1 ,43729   ,2157.5,5774.9,3100.5
BEGIN DESCRIPTION:
Black River 100.0
END DESCRIPTION:
XS GIS Cut Line= 6
      2404766.48       635662.872401634.35664548626989.192994724
2401155.08222733626558.8082817082401116.25871611626369.573923346
 2400989.7017451625397.8550131242400719.37486587624066.941551917
#Sta/Elev= 30
 -6592.4   43.16 -5902.4   41.54 -5362.4   29.39 -3952.4   32.97 -2632.4   28.29
 -2542.4   27.34 -2422.4   16.52 -1692.4   22.71 -1622.4   17.29 -1552.4   23.37
 -1412.4   18.07  -952.4   15.53  -112.4   19.76   757.6   20.49   877.6   15.57
  1687.6    18.9  1747.6   10.65  1867.6   10.47  2177.6   14.11  3107.4   10.63
  3497.1   15.43  3797.1    11.1  4707.1   11.09  4907.1   16.21  4925.7    10.3
  4926.1   -2.06  5073.9   -2.06  5074.3    10.3  5077.1   32.59    5978   48.83
#Mann= 3 ,0,0
 -6592.4     .15       0  4907.1     .05       0  5077.1     .15       0
Bank Sta=4907.1,5077.1
XS Rating Curve= 0 ,0
Exp/Cntr=0.3,0.1

Type RM Length L Ch R = 1 ,37954   ,2136.6,2136.6,2136.6
BEGIN DESCRIPTION:
Black River 97.0
END DESCRIPTION:
XS GIS Cut Line= 5
      2405868.07       636074.792402513.00145481626891.813217019
2402560.61817018626759.6016340362403006.28676002625326.902494304
      2402287.95       623489.55
#Sta/Elev= 30
 -4774.7   49.13 -3264.7    31.1 -1894.7   33.55    15.3   27.73   165.3   17.06
   465.3   19.75   805.3   15.76  2395.3   15.12  2815.3   21.33  3215.3   15.72
  3385.3   21.24  3615.3   16.11  3705.3   19.92  4775.3   17.94  4805.3   10.91
  4925.7   10.42  4926.1   -2.63  5073.9   -2.63  5074.3   10.42  5075.3      11
  6195.2   14.79  6665.2   11.69  6705.2   17.27  6791.6   13.92  6871.6   17.73
  7341.6   15.42  7751.6    29.9  7901.6   31.03  8231.6   49.51  8529.3   49.32
#Mann= 3 ,0,0
 -4774.7     .15       0  4925.7     .05       0  5075.3     .15       0
Bank Sta=4925.7,5075.3
XS Rating Curve= 0 ,0
Exp/Cntr=0.3,0.1

Type RM Length L Ch R = 1 ,35817   ,999.8,999.8,999.8
BEGIN DESCRIPTION:
Black River 96.0
END DESCRIPTION:
XS GIS Cut Line= 3
      2407364.67       636862.51      2403372.88       625717.94
      2402638.62       623340.75
#Sta/Elev= 30
 -6837.9   51.04 -6557.9   52.15 -5877.9   42.88 -4987.9   46.19 -4537.9   30.55
 -2607.9   35.94 -2077.9   26.93  -597.9   27.15  -557.9   21.69  -137.9   16.14
  1752.1   14.43  2072.1   19.04  2872.1   17.08  3092.1   21.49  3642.1   17.77
  3732.1   12.67  4152.1   15.42  4222.1   10.82  4472.1   10.23  4772.1   15.27
  4812.1   10.54  4925.7     9.9  4926.1   -2.81  5073.9   -2.81  5074.3     9.9
    5100   17.93    6320   14.99    6490   19.39    6610   33.76    7488   47.58
#Mann= 3 ,0,0
 -6837.9     .15       0  4925.7     .05       0  5074.3     .15       0
Bank Sta=4925.7,5074.3
XS Rating Curve= 0 ,0
Exp/Cntr=0.3,0.1

Type RM Length L Ch R = 1 ,34817   ,1015.5,1015.5,1015.5
BEGIN DESCRIPTION:
Black River 95.0
END DESCRIPTION:
XS GIS Cut Line= 3
      2407784.76       636074.83      2403998.48       624940.39
      2403321.27       623078.21
#Sta/Elev= 30
 -6760.6   42.07 -6630.6   41.52 -6580.6   54.58 -6550.6   48.97 -5420.6   44.11
 -5230.6   32.92 -4900.6   30.67 -3390.6   31.71 -3350.6    39.4 -3330.6   33.99
 -2380.6   26.22 -1320.6   25.88  -960.6   15.59   -80.6   20.84  1769.4   15.24
  2159.4   22.35  2939.4   14.88  3319.4   19.45  3449.4   11.83  4569.4   15.74
  4639.4   10.22  4925.7    9.66  4926.1   -2.91  5073.9   -2.91  5074.3    9.66
    5080    14.1    5790   11.36    6610   43.58    6760   39.58  6981.5   46.69
#Mann= 3 ,0,0
 -6760.6     .15       0  4925.7     .05       0  5074.3     .15       0
Bank Sta=4925.7,5074.3
XS Rating Curve= 0 ,0
Exp/Cntr=0.3,0.1

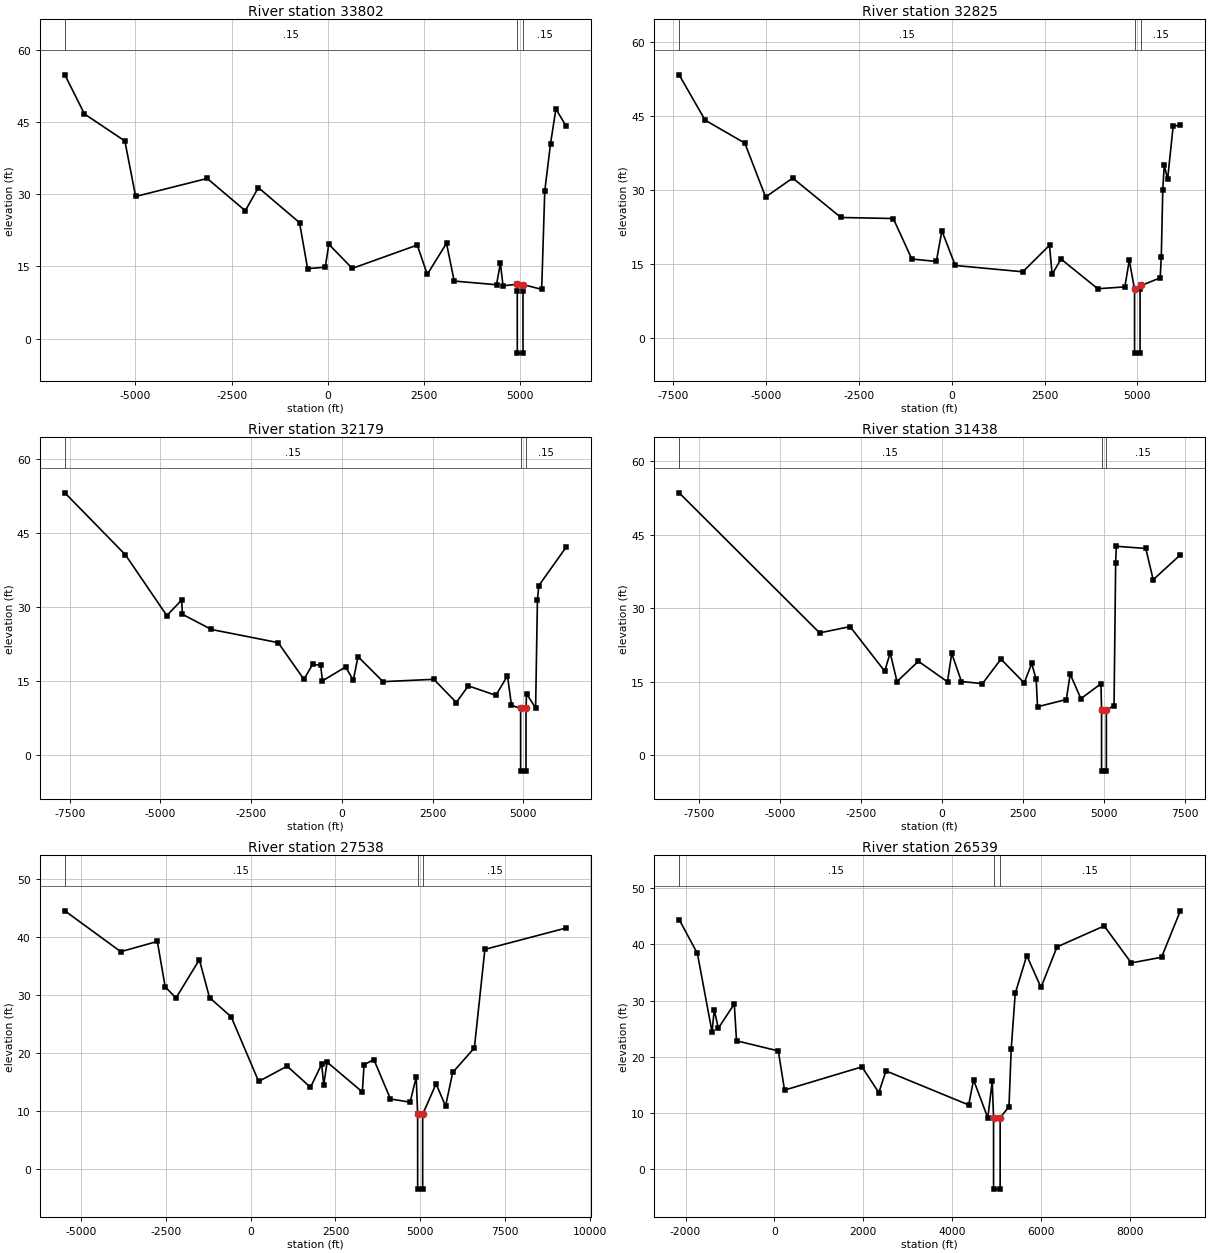
Type RM Length L Ch R = 1 ,33802   ,976.4,976.4,976.4
BEGIN DESCRIPTION:
Black River 94.0
END DESCRIPTION:
XS GIS Cut Line= 3
      2408624.93       635602.18      2404791.01       624406.33
      2404450.27       623261.98
#Sta/Elev= 30
 -6834.1    54.8 -6324.1   46.67 -5274.1   41.05 -4994.1   29.53 -3134.1   33.27
 -2144.1   26.57 -1804.1   31.37  -734.1   24.09  -524.1   14.54   -64.1   14.84
    25.9   19.61   635.9   14.59  2325.9   19.44  2585.9   13.34  3085.9   19.81
  3285.9   11.96  4385.9    11.2  4485.9   15.65  4555.9   10.98  4915.9   11.29
  4925.7     9.8  4926.1   -3.01  5073.9   -3.01  5074.3     9.8    5080   11.22
    5560   10.24    5640   30.67    5790   40.52    5930   47.72    6194   44.15
#Mann= 3 ,0,0
 -6834.1     .15       0  4915.9     .05       0    5080     .15       0
Bank Sta=4915.9,5080
XS Rating Curve= 0 ,0
Exp/Cntr=0.3,0.1

Type RM Length L Ch R = 1 ,32825   ,646.2,646.2,646.2
BEGIN DESCRIPTION:
Black River 93.0
END DESCRIPTION:
XS GIS Cut Line= 4
      2409109.42        635268.1 2405205.6824262623633.918126905
2405051.32126339623519.962385588       2404700.7       622502.54
#Sta/Elev= 30
 -7345.9   53.32 -6645.9   44.13 -5575.9   39.48 -5015.9   28.55 -4285.9   32.39
 -2985.9    24.4 -1575.9   24.19 -1075.9   15.98  -415.9   15.48  -265.9    21.7
    94.1   14.67  1914.1   13.39  2634.1   18.76  2704.1   12.88  2944.1   15.97
  3934.1    9.95  4664.1   10.33  4784.1   15.73  4925.7    9.83  4926.1    -3.1
  5073.9    -3.1  5074.3    9.83  5106.1   10.62  5616.1   12.15  5646.1   16.41
  5686.1   30.05  5726.1   35.01  5816.1   32.14  5966.1   42.95  6159.7   43.08
#Mann= 3 ,0,0
 -7345.9     .15       0  4925.7     .05       0  5106.1     .15       0
Bank Sta=4925.7,5106.1
XS Rating Curve= 0 ,0
Exp/Cntr=0.3,0.1

Type RM Length L Ch R = 1 ,32179   ,741.3,741.3,741.3
BEGIN DESCRIPTION:
Black River 92.0
END DESCRIPTION:
XS GIS Cut Line= 3
      2409328.77        635268.1      2405534.18       623226.33
      2405073.57       622129.63
#Sta/Elev= 30
 -7636.2   53.07 -5966.2   40.54 -4826.2   28.27 -4416.2   31.41 -4396.2   28.53
 -3596.2   25.46 -1756.2    22.8 -1046.2   15.38  -806.2   18.43  -586.2    18.2
  -536.2   15.08   103.8   17.89   313.8   15.21   443.8   19.97  1133.8   14.92
  2533.8   15.39  3153.8    10.7  3483.8   14.07  4243.8   12.15  4563.8   16.11
  4673.8   10.14  4925.7    9.51  4926.1   -3.16  5073.9   -3.16  5074.3    9.51
  5089.3   12.47  5339.3     9.6  5389.3    31.5  5429.3   34.34  6178.8   42.07
#Mann= 3 ,0,0
 -7636.2     .15       0  4925.7     .05       0  5074.3     .15       0
Bank Sta=4925.7,5074.3
XS Rating Curve= 0 ,0
Exp/Cntr=0.3,0.1

Type RM Length L Ch R = 1 ,31438   ,3899.5,3899.5,3899.5
BEGIN DESCRIPTION:
Black River 91.0
END DESCRIPTION:
XS GIS Cut Line= 3
      2409591.97       635421.63      2405972.86       622743.79
      2406499.29       620506.48
#Sta/Elev= 30
   -8123   53.52   -3783   24.95   -2843   26.23   -1773   17.14   -1603   20.87
   -1393   15.01    -733   19.16     167   14.97     297   20.78     597   15.03
    1247    14.6    1817    19.6    2537   14.73    2767   18.71    2907   15.46
    2947    9.88    3837   11.36    3957   16.55    4287   11.53    4907   14.57
  4925.6    9.25    4926   -3.25    5074   -3.25  5074.4    9.25  5311.3   10.08
  5361.3   39.16  5381.3   42.62  6291.3   42.17  6521.3    35.8  7359.7   40.87
#Mann= 3 ,0,0
   -8123     .15       0  4925.6     .05       0  5074.4     .15       0
Bank Sta=4925.6,5074.4
XS Rating Curve= 0 ,0
Exp/Cntr=0.3,0.1

Type RM Length L Ch R = 1 ,27538   ,999.7,999.7,999.7
BEGIN DESCRIPTION:
Black River 88.0
END DESCRIPTION:
XS GIS Cut Line= 3
      2409986.78       634544.28      2407358.19       624392.47
      2406587.01       620155.58
#Sta/Elev= 30
 -5486.6   44.58 -3836.6   37.52 -2756.6   39.29 -2526.6   31.45 -2206.6   29.51
 -1516.6   36.14 -1216.6   29.58  -576.6   26.25   233.4   15.09  1073.4   17.73
  1763.4   14.08  2093.4   18.09  2153.4   14.49  2253.4   18.43  3293.4   13.28
  3343.4   17.97  3633.4   18.88  4123.4   12.06  4703.4   11.51  4883.4   15.85
  4925.6    9.42    4926   -3.52    5074   -3.52  5074.4    9.42    5470   14.67
    5750   10.84    5960   16.64    6600   20.89    6910   37.92  9306.5   41.61
#Mann= 3 ,0,0
 -5486.6     .15       0  4925.6     .05       0  5074.4     .15       0
Bank Sta=4925.6,5074.4
XS Rating Curve= 0 ,0
Exp/Cntr=0.3,0.1

Type RM Length L Ch R = 1 ,26539   ,887,887,887
BEGIN DESCRIPTION:
Black River 87.0
END DESCRIPTION:
XS GIS Cut Line= 3
      2410162.24       631034.79      2408327.35       624148.72
      2407223.09       620155.54
#Sta/Elev= 30
 -2143.7   44.44 -1733.7   38.41 -1403.7   24.41 -1353.7   28.37 -1263.7   25.07
  -903.7   29.39  -853.7   22.84    86.3   21.03   226.3   14.05  1966.3   18.19
  2346.3    13.6  2506.3   17.47  4366.3   11.41  4476.3   15.85  4796.3    9.12
  4896.3   15.66  4925.6    9.12    4926   -3.59    5074   -3.59  5074.4    9.12
  5272.6    11.1  5322.6   21.36  5412.6   31.27  5672.6   38.02  5992.6   32.34
  6352.6   39.56  7412.6    43.3  8022.6   36.71  8702.6   37.72  9125.7   45.99
#Mann= 3 ,0,0
 -2143.7     .15       0  4925.6     .05       0  5074.4     .15       0
Bank Sta=4925.6,5074.4
XS Rating Curve= 0 ,0
Exp/Cntr=0.3,0.1

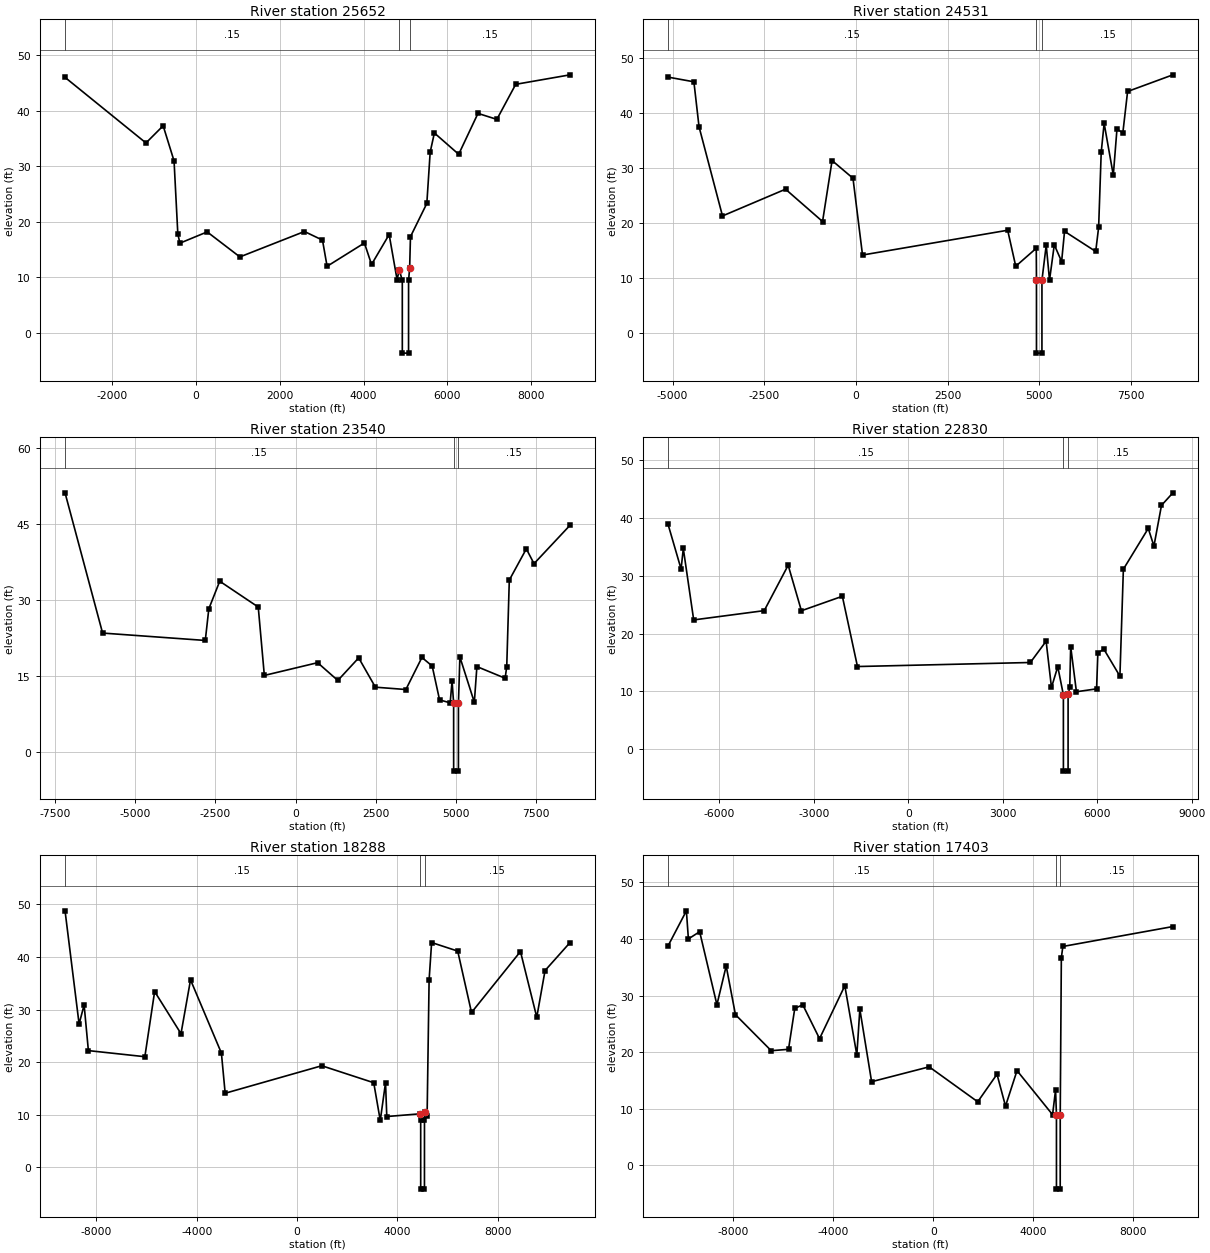
Type RM Length L Ch R = 1 ,25652   ,1120.7,1120.7,1120.7
BEGIN DESCRIPTION:
Black River 86.0
END DESCRIPTION:
XS GIS Cut Line= 3
      2411258.96       631978.01      2409197.16       624125.63
      2408275.93        620309.1
#Sta/Elev= 30
 -3118.4   46.05 -1188.4   34.23  -778.4   37.33  -518.4   30.99  -428.4   17.81
  -378.4   16.17   271.6    18.2  1051.6   13.69  2591.6   18.27  3021.6   16.72
  3131.6      12  4021.6    16.2  4191.6   12.33  4611.6   17.72  4801.6    9.55
  4851.6   11.39  4925.2    9.45  4925.7   -3.65  5074.3   -3.65  5074.8    9.45
  5100.2   11.61  5120.2   17.34  5510.2   23.33  5590.2   32.58  5690.2   36.03
  6270.2   32.19  6730.2   39.56  7180.2   38.48  7630.2    44.8  8926.3   46.51
#Mann= 3 ,0,0
 -3118.4     .15       0  4851.6     .05       0  5100.2     .15       0
Bank Sta=4851.6,5100.2
XS Rating Curve= 0 ,0
Exp/Cntr=0.3,0.1

Type RM Length L Ch R = 1 ,24531   ,991.4,991.4,991.4
BEGIN DESCRIPTION:
Black River 85.0
END DESCRIPTION:
XS GIS Cut Line= 3
      2414576.01       633032.23       2410236.2       623888.38
      2408470.64        620687.6
#Sta/Elev= 30
 -5130.2    46.5 -4420.2   45.64 -4280.2   37.47 -3640.2   21.23 -1920.2    26.1
  -910.2   20.22  -650.2   31.31   -80.2   28.09   179.8   14.12  4139.8   18.63
  4359.8   12.08  4919.8   15.35  4925.2    9.54  4925.7   -3.73  5074.3   -3.73
  5074.8    9.54  5191.3   15.92  5281.3    9.54  5411.3   15.98  5611.3   12.94
  5691.3   18.43  6541.3   14.77  6621.3   19.17  6691.3   32.81  6771.3   38.09
  7021.3   28.65  7121.3   37.04  7281.3   36.34  7411.3   43.88  8646.7   46.91
#Mann= 3 ,0,0
 -5130.2     .15       0  4925.2     .05       0  5074.8     .15       0
Bank Sta=4925.2,5074.8
XS Rating Curve= 0 ,0
Exp/Cntr=0.3,0.1

Type RM Length L Ch R = 1 ,23540   ,709.6,709.6,709.6
BEGIN DESCRIPTION:
Black River 84.0
END DESCRIPTION:
XS GIS Cut Line= 3
      2418780.14       632362.76      2410856.66       623108.09
      2408443.85       620500.13
#Sta/Elev= 30
 -7183.2   51.17 -6013.2   23.47 -2813.2   22.01 -2703.2   28.26 -2363.2   33.71
 -1163.2   28.61  -973.2    15.1   686.8   17.62  1316.8   14.11  1966.8   18.57
  2486.8   12.78  3436.8   12.32  3936.8   18.65  4256.8   16.96  4486.8   10.27
  4816.8    9.69  4876.8   13.98  4925.2    9.56  4925.7    -3.8  5074.3    -3.8
  5074.8    9.56    5120   18.75    5570    9.79    5650   16.85    6530   14.55
    6580   16.86    6660   33.94    7190    40.1    7430   37.18  8552.9   44.77
#Mann= 3 ,0,0
 -7183.2     .15       0  4925.2     .05       0  5074.8     .15       0
Bank Sta=4925.2,5074.8
XS Rating Curve= 0 ,0
Exp/Cntr=0.3,0.1

Type RM Length L Ch R = 1 ,22830   ,4542.2,4542.2,4542.2
BEGIN DESCRIPTION:
Black River 83.0
END DESCRIPTION:
XS GIS Cut Line= 4
2419719.37667265 632051.559223872411203.95667265 622438.23922387
2410320.28667265 622036.569223872408633.30667265 620590.58922387
#Sta/Elev= 30
 -7633.1   39.04 -7213.1   31.17 -7143.1   34.74 -6813.1   22.36 -4573.1   23.97
 -3813.1   31.84 -3393.1   23.95 -2093.1   26.46 -1613.1   14.28  3876.9   14.98
  4376.9   18.67  4546.9   10.65  4746.9   14.26  4925.2    9.36  4925.7   -3.85
  5074.3   -3.85  5074.8    9.36  5084.59.602027  5126.9   10.66  5156.9   17.75
  5339.3    9.91  5979.3   10.41  6019.3   16.63    6210   17.29    6720   12.61
    6830   31.15    7620   38.22    7800   35.16    8040   42.22  8401.9   44.39
#Mann= 3 ,0,0
 -7633.1     .15       0  4925.2     .05       0  5084.5     .15       0
Bank Sta=4925.2,5084.5
XS Rating Curve= 0 ,0
Exp/Cntr=0.3,0.1

Type RM Length L Ch R = 1 ,18288   ,885.1,885.1,885.1
BEGIN DESCRIPTION:
Black River 79.0
END DESCRIPTION:
XS GIS Cut Line= 3
2420679.77064764631346.7693523622411433.54064764620509.059352362
2407933.50064764615788.829352362
#Sta/Elev= 30
   -9246   48.78   -8686   27.25   -8486   30.88   -8316   22.19   -6066   21.03
   -5676   33.43   -4626   25.41   -4246   35.65   -3016   21.72   -2866   14.08
     984   19.31    3054   16.08    3314     8.9    3524   16.09    3574    9.65
    4884   10.16  4924.6     8.9  4925.1   -4.16  5074.9   -4.16  5075.4     8.9
    5080   10.49    5180    9.73    5260   35.63    5360   42.75    6400   41.12
    6950   29.44    8900   41.04    9550   28.54    9880   37.42 10876.3   42.75
#Mann= 3 ,0,0
   -9246     .15       0    4884     .05       0    5080     .15       0
Bank Sta=4884,5080
XS Rating Curve= 0 ,0
Exp/Cntr=0.3,0.1

Type RM Length L Ch R = 1 ,17403   ,583.6,583.6,583.6
BEGIN DESCRIPTION:
Black River 78.0
END DESCRIPTION:
XS GIS Cut Line= 3
       2422219.5       631852.47      2412125.65       619957.09
      2409164.65        616467.6
#Sta/Elev= 30
-10600.8   38.72 -9860.8   44.98 -9780.8   40.01 -9330.8   41.29 -8640.8   28.38
 -8270.8   35.23 -7900.8   26.62 -6470.8   20.25 -5780.8    20.5 -5530.8   27.73
 -5210.8   28.37 -4540.8   22.38 -3530.8   31.74 -3050.8   19.49 -2930.8   27.59
 -2460.8   14.77  -160.8    17.4  1779.2   11.22  2549.2   16.09  2889.2   10.46
  3349.2   16.73  4769.2    8.94  4889.2    13.3  4924.6    8.94  4925.1   -4.22
  5074.9   -4.22  5075.4    8.94    5120   36.67    5180   38.68  9576.5    42.2
#Mann= 3 ,0,0
-10600.8     .15       0  4924.6     .05       0  5075.4     .15       0
Bank Sta=4924.6,5075.4
XS Rating Curve= 0 ,0
Exp/Cntr=0.3,0.1

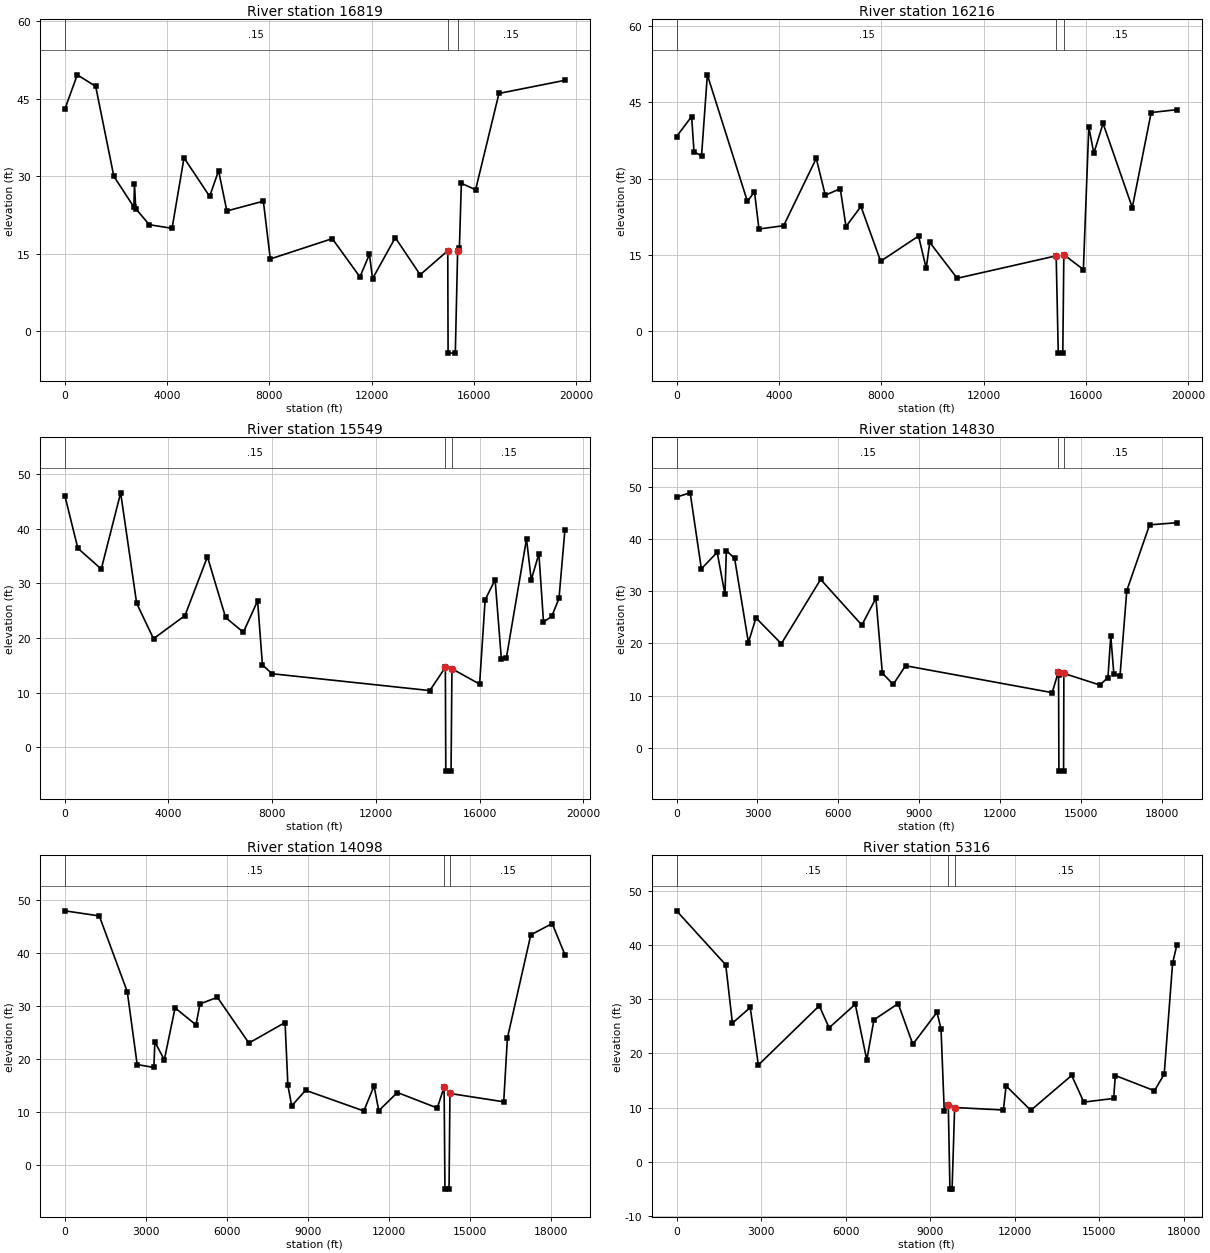
Type RM Length L Ch R = 1 ,16819   ,602.5,602.5,602.5
XS GIS Cut Line= 2
2422326.14102905631451.7317383092409898.42406972616351.682447161
#Sta/Elev= 30
       0   42.91   488.2   49.59  1207.4   47.36    1917   29.97  2701.7      24
  2724.4   28.51  2773.9   23.69  3303.8   20.59  4194.2   19.89    4662   33.53
  5664.8   26.06  6013.2   31.05  6336.1   23.25  7763.8   25.14  8035.8   13.96
 10457.8   17.89 11541.3   10.48 11911.5   14.87 12034.2   10.15 12922.3   18.09
 13895.3   10.91 14974.615.5494814987.19   -4.2615269.67   -4.26 15361.3   15.56
 15429.3      16 15505.8   28.61 16062.7   27.35 16976.9   45.99 19556.6   48.53
#Mann= 3 ,0,0
       0     .15       0 14974.6     .05       0 15361.3     .15       0
Bank Sta=14974.6,15361.3
XS Rating Curve= 0 ,0
Exp/Cntr(USF)=0,0
Exp/Cntr=0.3,0.1

Type RM Length L Ch R = 1 ,16216   ,667.1,667.1,667.1
XS GIS Cut Line= 3
2422735.69732506 631015.726585372411256.68006582617084.669722552
2410303.49004361615927.868221109
#Sta/Elev= 30
       0   38.26   588.8    42.2   681.5   35.25   975.7   34.47  1202.7   50.39
  2768.6   25.52  3044.9    27.4    3220   20.09  4184.5   20.74  5459.6   33.97
  5812.4   26.74  6398.1   28.01  6622.4   20.58  7206.8   24.52  7976.3   13.76
  9457.5   18.71  9757.5   12.37  9896.1   17.47 10968.6   10.41 14837.914.82012
14919.65    -4.315096.67    -4.3 15137.815.04826 15900.8   12.13 16112.9   40.12
   16311   34.99 16670.1   40.85 17813.4    24.3 18551.5   42.9819550.02   43.54
#Mann= 3 ,0,0
       0     .15       0 14837.9     .05       0 15137.8     .15       0
Bank Sta=14837.9,15137.8
XS Rating Curve= 0 ,0
Exp/Cntr(USF)=0,0
Exp/Cntr=0.3,0.1

Type RM Length L Ch R = 1 ,15549   ,718.9,718.9,718.9
XS GIS Cut Line= 2
2423133.54585452630693.1131033552410959.85328024615699.260087157
#Sta/Elev= 30
       0   46.08   502.6   36.43  1407.4   32.62    2155   46.57    2772   26.36
  3422.8   19.88  4635.7   24.11  5502.8   34.87  6203.6   23.76  6888.2   21.06
  7437.6    26.8  7623.5   15.09  7995.4   13.47 14081.3   10.39   14681   14.64
14697.94   -4.3514900.79   -4.35 14934.9   14.38 16002.4   11.57 16215.4   26.99
 16600.3   30.67 16840.5   16.22   17033   16.31 17811.9   38.13 17993.6   30.64
 18289.4   35.43 18466.9   22.94 18783.9   23.95 19064.4   27.25 19294.3   39.86
#Mann= 3 ,0,0
       0     .15       0   14681     .05       0 14934.9     .15       0
Bank Sta=14681,14934.9
XS Rating Curve= 0 ,0
Exp/Cntr(USF)=0,0
Exp/Cntr=0.3,0.1

Type RM Length L Ch R = 1 ,14830   ,732.4,732.4,732.4
XS GIS Cut Line= 3
2423543.75767698 630045.766538712412064.88167167616018.580060219
2411793.09164285615686.452644994
#Sta/Elev= 30
       0   48.05   504.7   48.86   919.1   34.29  1506.2   37.45  1794.6   29.38
  1846.8   37.79    2152   36.31    2665   20.16  2944.7   24.88  3886.6   19.93
  5344.2   32.26  6873.2    23.5  7394.8   28.66  7633.5    14.3  8036.2   12.12
  8494.1   15.71 13933.2   10.55 14166.3   14.57 14170.9   13.87 14183.3    -4.5
 14357.2    -4.5 14367.7   14.24 15704.8   12.01 16003.2   13.45   16108   21.44
 16222.4   14.09 16450.3   13.81 16702.4   30.13 17547.8   42.7218554.46   43.13
#Mann= 3 ,0,0
       0     .15       0 14166.3     .05       0 14367.7     .15       0
Bank Sta=14166.3,14367.7
XS Rating Curve= 0 ,0
Exp/Cntr(USF)=0,0
Exp/Cntr=0.3,0.1

Type RM Length L Ch R = 1 ,14098   ,8782.3,8782.3,8782.3
XS GIS Cut Line= 3
2423984.54004305629696.9469435982416118.95801424619900.342968921
2412418.29666035615217.446345251
#Sta/Elev= 30
       0   48.03  1277.5   47.07  2315.4   32.71  2681.4   18.93  3300.3   18.38
  3337.8   23.22    3687   19.83  4086.5   29.66  4860.9   26.44  5008.6   30.41
  5653.2   31.66  6821.7      23  8161.2   26.89  8266.3   14.98  8407.8   11.11
  8921.1   14.06 11079.5   10.15 11459.6   14.88 11633.8    10.2 12324.2   13.64
 13800.6   10.71 14055.2   14.66 14085.6   -4.65 14237.4   -4.65 14270.8   13.46
 16263.7   11.88 16399.9   23.95 17265.8   43.47 18059.9   45.6318532.09    39.7
#Mann= 3 ,0,0
       0     .15       0 14055.2     .05       0 14270.8     .15       0
Bank Sta=14055.2,14270.8
XS Rating Curve= 0 ,0
Exp/Cntr(USF)=0,0
Exp/Cntr=0.3,0.1

Type RM Length L Ch R = 1 ,5316    ,932.9,932.9,932.9
XS GIS Cut Line= 2
2424874.48321186629005.3259343582414269.48138206614768.239471411
#Sta/Elev= 30
       0   46.39  1744.8    36.4  1982.1   25.61  2614.4   28.51  2902.6   17.86
  5063.9   28.82  5414.8   24.75  6343.1   29.11  6751.2    18.8  7005.8   26.23
    7865   29.22  8385.4    21.7  9243.6   27.62  9386.8   24.53  9501.4    9.31
  9644.3   10.46 9702.75    -5.1 9779.34    -5.1  9869.5      10   11600    9.54
   11696      14 12573.7    9.48 14024.1   15.94 14455.6      11 15514.5   11.68
 15572.7   15.92 16962.7    13.1 17307.7   16.16 17606.1   36.6917752.77   39.99
#Mann= 3 ,0,0
       0     .15       0  9644.3     .05       0  9869.5     .15       0
Bank Sta=9644.3,9869.5
XS Rating Curve= 0 ,0
Exp/Cntr(USF)=0,0
Exp/Cntr=0.3,0.1

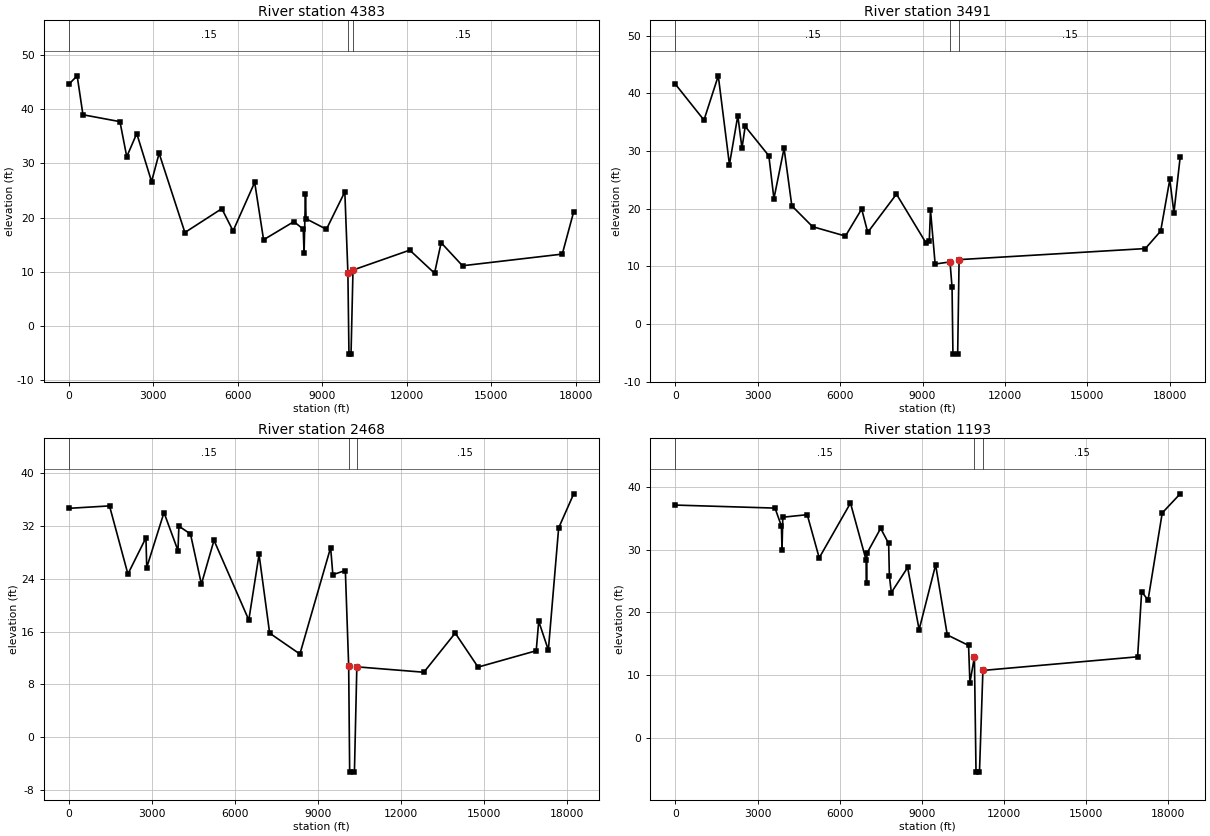
Type RM Length L Ch R = 1 ,4383    ,892,892,892
XS GIS Cut Line= 3
2425796.46416434628611.1615099262416834.17050112616745.864029703
2414985.85149137614298.850384188
#Sta/Elev= 30
       0   44.61   293.4   46.15     499   38.97  1813.9    37.7  2055.2   31.23
  2410.8   35.51  2937.1   26.65  3205.2   31.86  4121.3   17.25  5432.9   21.65
  5833.3   17.54  6600.6    26.5  6917.1   15.91  7994.4   19.26  8325.6   17.87
  8355.8   13.43  8405.2   24.38  8426.1   19.79  9149.7   17.85  9803.8   24.75
  9912.79.851045 9950.66   -5.1810024.17   -5.18 10094.1   10.33 12110.8      14
 12991.5    9.74 13225.8   15.37   13985   11.12 17529.8   13.2717936.32    21.1
#Mann= 3 ,0,0
       0     .15       0  9912.7     .05       0 10094.1     .15       0
Bank Sta=9912.7,10094.1
XS Rating Curve= 0 ,0
Exp/Cntr(USF)=0,0
Exp/Cntr=0.3,0.1

Type RM Length L Ch R = 1 ,3491    ,1022.9,1022.9,1022.9
XS GIS Cut Line= 3
 2426478.0029378 628117.633432592416462.20250015614763.232849051
 2415408.8720314613358.792224051
#Sta/Elev= 30
       0   41.61  1041.4   35.38  1562.4   43.06  1968.2   27.66  2273.5   36.14
  2424.8   30.51  2542.4   34.28  3403.6   29.18  3588.1   21.74  3957.7   30.48
  4240.2    20.5  4995.6   16.88  6192.3   15.25  6783.6   19.94  7004.3   15.89
  8050.1   22.53  9120.1    14.1  9245.3   14.38    9289   19.76  9458.6    10.4
10000.24   10.76 10074.36.33229410106.62   -5.2410278.81   -5.2410330.68   11.16
 17112.4   13.08 17670.2   16.11   18003   25.07   18153   19.29 18380.6   28.97
#Mann= 3 ,0,0
       0     .15       010000.24     .05       010330.68     .15       0
Bank Sta=10000.24,10330.68
XS Rating Curve= 0 ,0
Exp/Cntr(USF)=0,0
Exp/Cntr=0.3,0.1

Type RM Length L Ch R = 1 ,2468    ,1275.3,1275.3,1275.3
XS GIS Cut Line= 3
2427347.55240739627553.6013442062418573.55817313615916.905601312
2416254.92015999612841.762812694
#Sta/Elev= 30
       0    34.7  1468.4   35.07  2133.7   24.73  2785.9   30.23  2814.7   25.72
  3438.6   34.06  3944.5   28.28  3977.2      32  4396.6   30.81  4791.1    23.2
  5247.1   29.85  6505.8   17.76  6876.3    27.7  7259.4   15.77  8353.2    12.6
  9464.9   28.75  9545.1   24.64  9997.1   25.27 10117.210.8085610153.22   -5.31
10325.19   -5.31 10412.5   10.66 12836.4    9.84 13969.8   15.78 14796.7   10.62
 16899.5    13.1 16989.9   17.57 17338.5    13.2 17711.2   31.73 18255.4    36.9
#Mann= 3 ,0,0
       0     .15       0 10117.2     .05       0 10412.5     .15       0
Bank Sta=10117.2,10412.5
XS Rating Curve= 0 ,0
Exp/Cntr(USF)=0,0
Exp/Cntr=0.3,0.1

Type RM Length L Ch R = 1 ,1193    ,,,
XS GIS Cut Line= 2
2428264.10455102627107.0759409022417241.97749052612324.734957848
#Sta/Elev= 30
       0   37.09  3639.9   36.61  3873.2   33.75  3895.7      30  3924.3   35.16
  4816.5   35.56    5254   28.69  6396.2   37.41  6967.8   28.32  6982.5   24.72
  6997.8   29.42  7498.4   33.39  7790.7   30.98  7816.8   25.85  7888.1   23.17
  8484.6   27.16  8903.5   17.26  9506.4   27.58  9932.1   16.43 10709.6   14.76
 10758.7    8.84   10923  12.91910981.86    -5.411108.06    -5.4 11233.5   10.78
 16884.5   12.95 17031.9    23.3 17266.3   21.98 17783.7   35.8418439.22   38.88
#Mann= 3 ,0,0
       0     .15       0   10923     .05       0 11233.5     .15       0
Bank Sta=10923,11233.5
XS Rating Curve= 0 ,0
Exp/Cntr(USF)=0,0
Exp/Cntr=0.3,0.1
LCMann Table=0

Chan Stop Cuts=-1
Use User Specified Reach Order=0
Composite Channel Slope=5

--- BlackRiver.g01 (geometry) ---

Geom Title=Natural
Program Version=6.60

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
River Reach=Black River     ,Reach-1

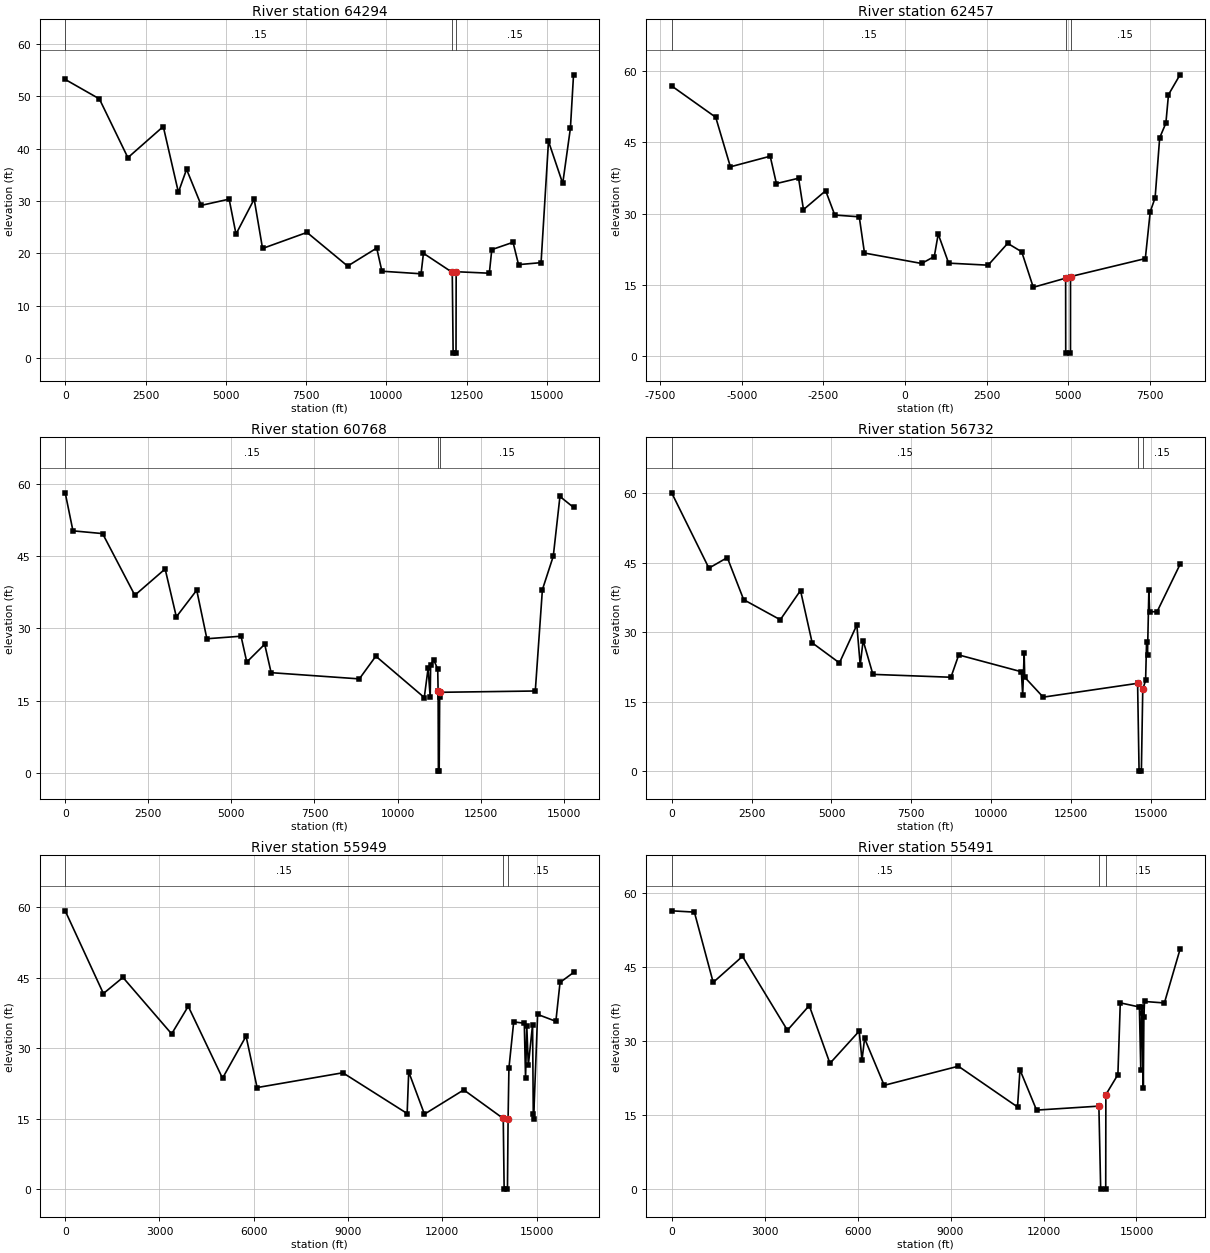
Type RM Length L Ch R = 1 ,64294   ,1836.5,1836.5,1836.5
BEGIN DESCRIPTION:
Black River 125.0
END DESCRIPTION:
XS GIS Cut Line= 6
2392188.97640201642289.5268889442390590.35118085636116.319255313
2390976.57309344634800.0679348082390026.52563953 630675.79232132
2390033.16879415630468.363649827       2389274.4       626911.51
#Sta/Elev= 30
       0   53.23  1063.4   49.51  1951.3   38.27  3052.8   44.23  3523.9   31.65
  3778.1   36.04  4235.6   29.15  5103.3   30.34  5317.5   23.66    5883   30.34
  6143.7   20.91  7526.5   23.98  8792.5   17.54  9698.1   20.99  9859.8   16.56
 11078.6   16.07 11152.6   19.99 12049.8   16.3412077.08      .912166.49      .9
 12171.516.46592 13203.8   16.18 13280.5   20.69   13942   22.09 14113.3   17.82
 14814.5    18.2 15045.9    41.4 15488.8   33.34 15728.1   43.91 15825.3   54.11
#Mann= 3 ,0,0
       0     .15       0 12049.8     .05       0 12171.5     .15       0
Bank Sta=12049.8,12171.5
XS Rating Curve= 0 ,0
Exp/Cntr=0.3,0.1

Type RM Length L Ch R = 1 ,62457   ,1689.3,1689.3,1689.3
BEGIN DESCRIPTION:
Black River 124.0
END DESCRIPTION:
XS GIS Cut Line= 6
2392411.62904549642144.1880529362390820.97212948635870.983906001
2391508.15823089 633043.876172992390948.57437392630438.624271995
2391003.63038155630296.821347977      2390313.29       627022.17
#Sta/Elev= 30
 -7151.8   56.83 -5801.8   50.25 -5351.8   39.83 -4131.8   42.06 -3941.8   36.31
 -3261.8   37.43 -3111.8   30.83 -2431.8    34.8 -2151.8   29.69 -1401.8   29.32
 -1241.8    21.7   508.2   19.51   898.2   20.97  1018.2    25.7  1338.2   19.58
  2548.2   19.15  3148.2   23.74  3578.2   21.96 3932.38    14.5 4924.18   16.42
    4927     .66    5073     .66 5073.85   16.75    7367   20.54    7517   30.38
    7667   33.32    7807   45.93    7997   49.01    8077      55  8429.9   59.17
#Mann= 3 ,0,0
 -7151.8     .15       0 4924.18     .05       0 5073.85     .15       0
#XS Ineff= 2 , 0
Permanent Ineff=
       F       F
Bank Sta=4924.18,5073.85
XS Rating Curve= 0 ,0
Exp/Cntr=0.3,0.1

Type RM Length L Ch R = 1 ,60768   ,4035.7,4035.7,4035.7
BEGIN DESCRIPTION:
Black River 122.0
END DESCRIPTION:
XS GIS Cut Line= 6
2392615.88384059642104.9415424332390916.53686308635945.744096208
 2391565.9501438633530.5279791982392184.42293721631451.457225425
2392068.57769228631159.791814128      2391330.26       627308.14
#Sta/Elev= 30
       0   58.09   233.1   50.21  1124.9   49.64  2094.9   36.86  3006.7   42.31
    3344   32.38  3957.1   37.91  4262.9   27.84  5290.8   28.37  5463.5   23.01
  6002.1    26.7  6196.1   20.81  8849.9   19.52  9345.9   24.23 10804.1   15.66
 10919.9   21.75 10982.1    15.7 10995.8   22.49 11092.6   23.42 11208.8   21.52
 11220.5   16.9211228.81      .411252.48      .4 11267.3   15.69 11273.316.73991
 14144.4   17.01 14358.2   38.02 14685.6   44.95 14886.1   57.33 15295.1   55.07
#Mann= 3 ,0,0
       0     .15       0 11220.5     .05       0 11273.3     .15       0
#XS Ineff= 2 , 0
Permanent Ineff=
       F       F
Bank Sta=11220.5,11273.3
XS Rating Curve= 0 ,0
Exp/Cntr=0.3,0.1

Type RM Length L Ch R = 1 ,56732   ,303.3,783.9,422.6
BEGIN DESCRIPTION:
Black River 119.0
END DESCRIPTION:
XS GIS Cut Line= 5
2392951.86449467641990.8318998412391114.10749375636173.747892966
 2392099.0704993632014.1728724692393313.47135297629301.822644573
 2393074.2968054626752.979974497
#Sta/Elev= 30
       0   60.11  1165.4   43.84  1740.7   46.12  2252.7   37.03  3398.5   32.69
  4031.6   39.01  4396.3   27.71  5249.7   23.37  5794.5   31.57    5900   22.88
  5990.5    28.2  6297.6   20.89  8738.9   20.27  8982.3   25.09 10942.8   21.46
 10984.4   16.38 11030.2   25.43 11048.6   20.27 11626.1   15.97 14580.1   18.96
 14626.2    -.0114698.29    -.01 14741.6   17.67 14830.6    19.6 14860.2   27.82
 14889.9   25.18 14932.7   39.09 14955.8   34.41 15189.7   34.43 15906.9   44.63
#Mann= 3 ,0,0
       0     .15       0 14580.1     .05       0 14741.6     .15       0
#XS Ineff= 2 , 0
Permanent Ineff=
       F       F
Bank Sta=14580.1,14741.6
XS Rating Curve= 0 ,0
Exp/Cntr=0.3,0.1

Type RM Length L Ch R = 1 ,55949   ,510.5,458.2,423
XS GIS Cut Line= 6
2393174.39616985641872.5241645742391189.09304328636176.672092498
2392141.05645509632023.7239730392393299.32390235628669.509174718
2393585.35402672628609.702122483 2393231.4022123626680.524348297
#Sta/Elev= 30
       0    59.2  1214.9    41.6  1836.8   45.03  3386.5   33.01  3914.6   38.89
  5005.6   23.58  5754.6   32.53    6106   21.59    8834   24.74   10880   16.07
 10929.5   24.94 11430.7   15.93 12681.7    21.1 13937.915.0102213966.46    -.02
14071.84    -.02   1409214.92412 14118.7   25.74 14270.5   35.57 14607.4   35.28
 14647.5   23.56 14687.5    34.6 14735.4    26.3   14871   34.99 14893.3   16.05
 14904.3   14.97 15031.1   37.16   15612   35.69 15744.9   43.96 16174.3   46.08
#Mann= 3 ,0,0
       0     .15       0 13937.9     .05       0   14092     .15       0
#XS Ineff= 2 , 0
Permanent Ineff=
       F       F
Bank Sta=13937.9,14092
XS Rating Curve= 0 ,0
Exp/Cntr(USF)=0,0
Exp/Cntr=0.3,0.1

Type RM Length L Ch R = 1 ,55491   ,200.8,200.8,200.8
BEGIN DESCRIPTION:
Black River 118.0
END DESCRIPTION:
XS GIS Cut Line= 6
2393432.63647658642101.5866659632392829.92725322639252.634513813
2391255.92538498636193.9854142632392147.82003084 632121.22054437
2393705.31246644628597.7499796052393304.95174855626641.986105873
#Sta/Elev= 30
       0   56.43   732.7   56.17  1339.8    41.9  2285.4   47.19  3735.4   32.19
  4440.1    37.2    5108   25.47  6051.6   32.01  6142.4   26.12    6226   30.53
  6858.8   21.01  9251.8   24.89 11161.5   16.62 11240.6   24.16 11776.4   15.98
 13787.116.7875313845.22    -.0614007.88    -.06 14012.6   19.12 14400.8   23.18
 14477.7   37.75   15094   36.91 15139.9   24.16   15163   35.75 15186.5   36.96
 15221.3   20.42 15239.6   34.88 15260.2   38.03 15901.6   37.73 16405.1   48.59
#Mann= 3 ,0,0
       0     .15       0 13787.1     .05       0 14012.6     .15       0
#XS Ineff= 2 , 0
Permanent Ineff=
       F       F
Bank Sta=13787.1,14012.6
XS Rating Curve= 0 ,0
Exp/Cntr=0.3,0.1