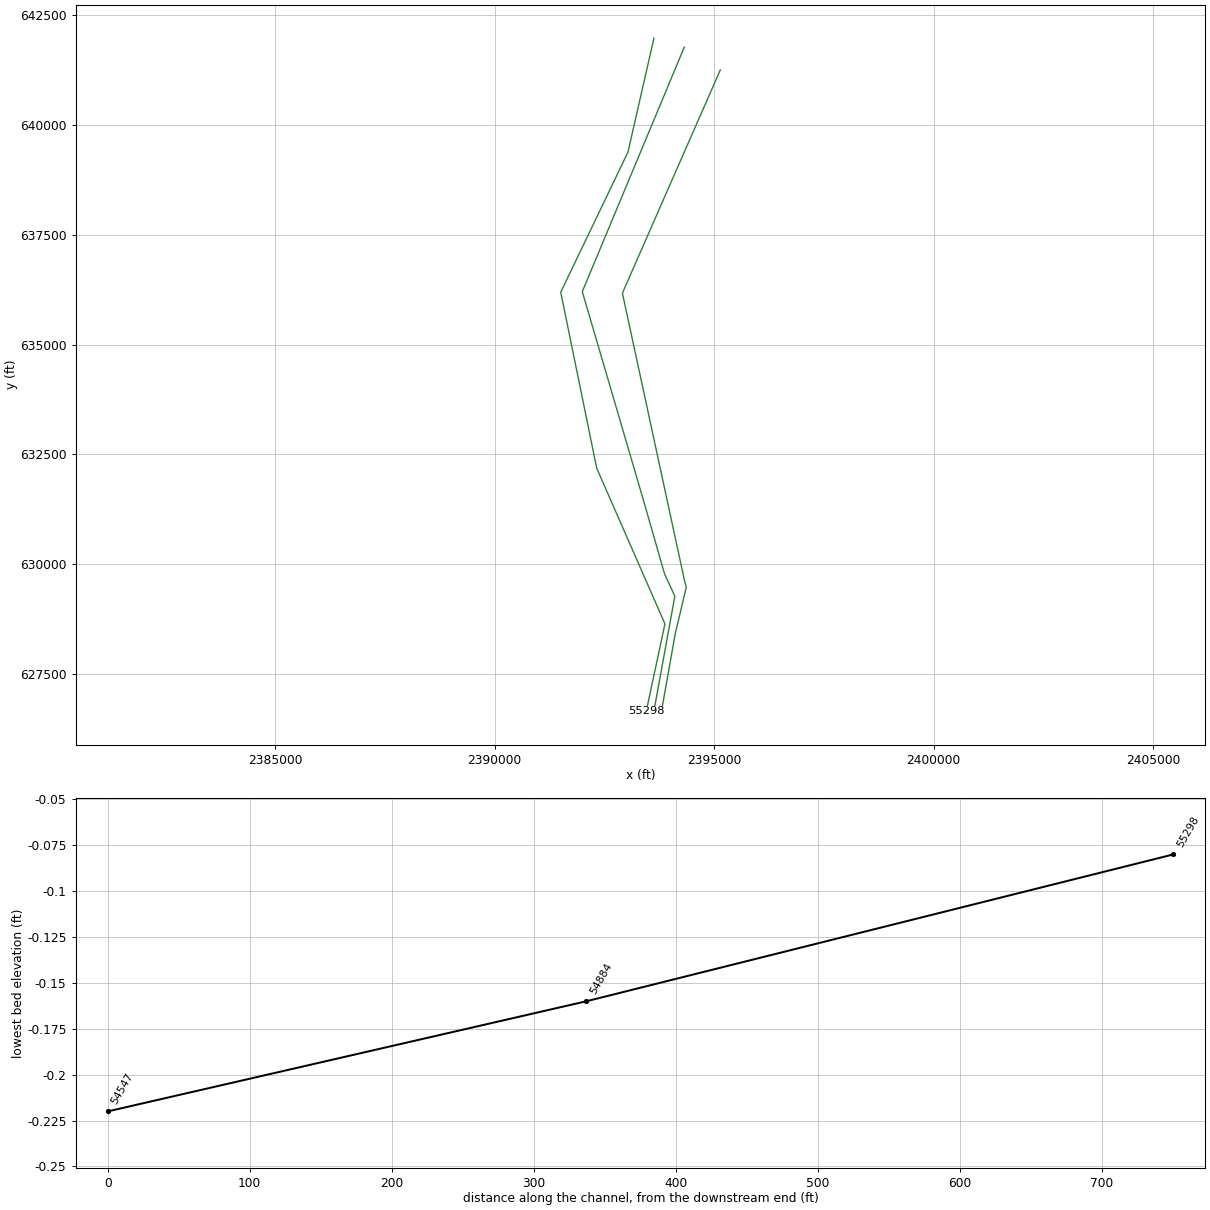
HEC-RAS study BlackRiver.prj: S-45-30 over Black River

--- BlackRiver.g01 (geometry) --- (continued)

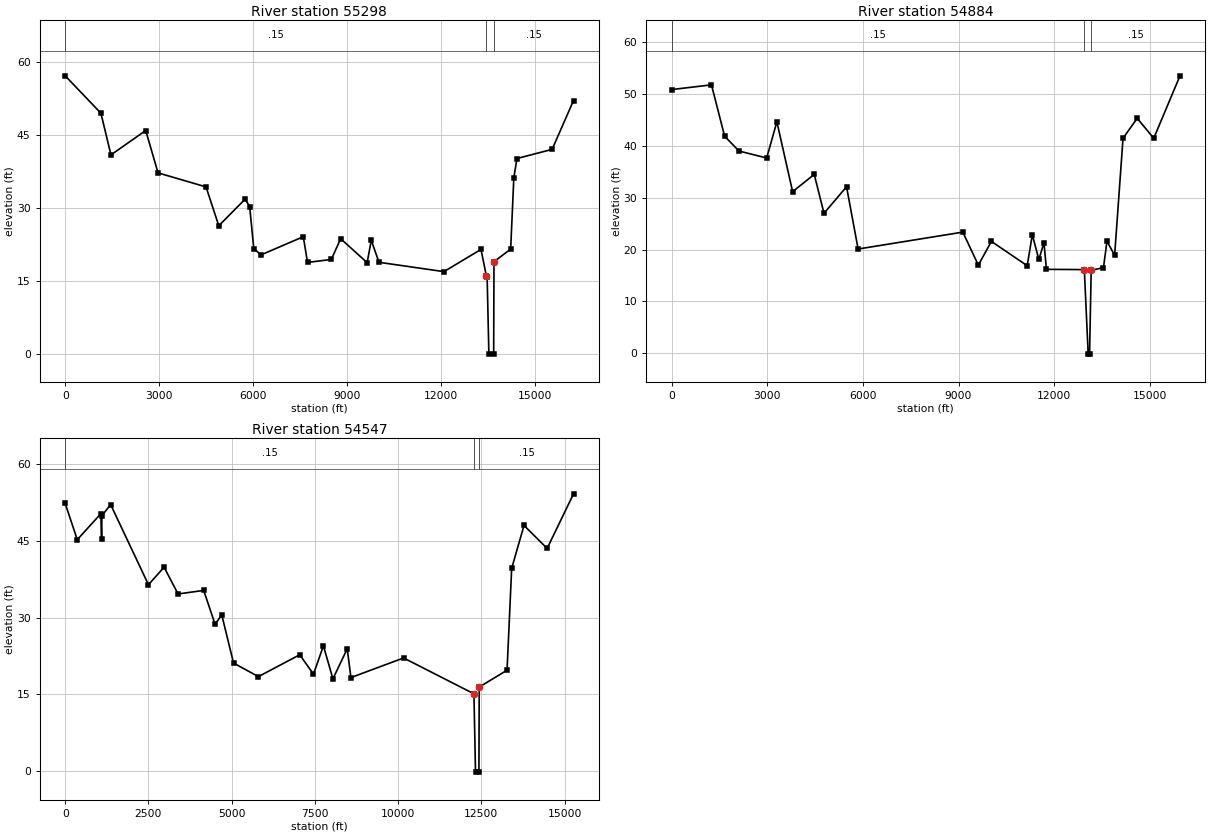
Type RM Length L Ch R = 1 ,55298   ,413.5,413.5,413.5
XS GIS Cut Line= 6
2393630.39708732641978.3491041592393038.05879676639382.142979573
2391507.54803687636191.8580229632392326.77242443632183.224190622
2393881.00177459628635.7356667982393455.58703222626647.612137168
#Sta/Elev= 30
       0   57.07  1140.5   49.39  1460.2   40.83  2570.8   45.84  2963.5   37.14
  4495.6   34.26  4903.1   26.28  5743.7   31.75    5889   30.21  6020.3   21.57
    6255   20.31  7600.3   24.03  7736.8   18.75  8495.2   19.36  8793.5   23.62
  9638.7   18.71  9771.3   23.29 10016.6   18.78 12089.7   16.86 13273.4   21.42
 13448.5   15.88 13470.1   15.7213525.62    -.08 13678.3    -.08 13688.3   18.91
 14221.2   21.49 14321.8   36.13 14422.5   40.09 15544.4   41.97   16228      52
#Mann= 3 ,0,0
       0     .15       0 13448.5     .05       0 13688.3     .15       0
#XS Ineff= 2 , 0
Permanent Ineff=
       F       F
Bank Sta=13448.5,13688.3
XS Rating Curve= 0 ,0
Exp/Cntr(USF)=0,0
Exp/Cntr=0.3,0.1

Type RM Length L Ch R = 1 ,54884   ,337.1,337.1,337.1
XS GIS Cut Line= 6
2394322.68866886641777.0050034342391998.80223099636205.549074871
2393375.37076971631506.1219100392393873.98960343629768.717871241
2394107.03722327629266.5292095492393630.75489178626654.418297743
#Sta/Elev= 30
       0   50.86  1248.8   51.77  1661.7   41.86  2112.3   39.01  2980.9   37.66
  3300.9   44.64    3795   31.17  4473.2    34.5  4779.7      27  5487.2   32.12
  5849.8   20.11  9135.6   23.37  9621.9      17 10031.3   21.58 11155.7   16.89
 11316.1   22.88 11520.9   18.09 11681.4   21.31 11759.9   16.19 12947.9   16.14
13069.19    -.1613112.41    -.16 13163.216.00946 13548.6   16.52 13659.3   21.62
 13898.7   18.89 14162.2   41.47   14607   45.32 15126.2   41.47 15949.9   53.51
#Mann= 3 ,0,0
       0     .15       0 12947.9     .05       0 13163.2     .15       0
#XS Ineff= 2 , 0
Permanent Ineff=
       F       F
Bank Sta=12947.9,13163.2
XS Rating Curve= 0 ,0
Exp/Cntr(USF)=0,0
Exp/Cntr=0.3,0.1

Type RM Length L Ch R = 1 ,54547   ,303.1,303.1,303.1
BEGIN DESCRIPTION:
Black River 116.0
END DESCRIPTION:
XS GIS Cut Line= 6
2395142.88186549641258.0851607682392912.17520342636170.551597593
2394329.30743497629608.2887355732394366.78837151629469.897585245
2394114.36218134628404.560556833 2393806.5398177626669.562269123
#Sta/Elev= 30
       0   52.33   362.3   45.25  1070.8   50.33  1093.1   45.44  1101.8   49.95
  1365.3   52.11  2500.9   36.44  2970.2   39.87  3389.4   34.63  4160.6   35.33
    4501    28.7  4702.6   30.53  5056.2   21.12  5802.6   18.46  7044.6   22.74
  7457.4   18.95  7756.2   24.48  8041.5   18.03  8471.1    23.9  8581.9   18.28
   10165   22.11   1227715.1011712324.66    -.2212426.83    -.22 12435.9   16.42
 13272.1   19.72 13410.7   39.63 13781.3   48.04 14476.8   43.54 15268.9   54.22
#Mann= 3 ,0,0
       0     .15       0   12277     .05       0 12435.9     .15       0
#XS Ineff= 2 , 0
Permanent Ineff=
       F       F
Bank Sta=12277,12435.9
XS Rating Curve= 0 ,0
Exp/Cntr=0.3,0.1

--- BlackRiver.g02 (geometry) ---

Geom Title=Effective - D/S
Program Version=6.60

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
River Reach=Black River     ,Reach-1
Reach XY= 30
      2305773.84       681196.47      2312412.24       687633.18
        2324381.       691453.72      2325406.21       688357.39
      2328933.29        689430.5      2331492.41       683713.39
      2337542.82       681822.69      2336709.23       676981.34
      2344011.31       669550.03      2353987.76       667384.33
      2361226.97       638496.57      2365033.58       636721.76
      2373178.48       642661.58      2384964.09       636868.18
       2384545.7       633031.15      2392047.12       631251.57
      2392844.47        628073.6      2401232.93       624891.96
      2403209.15       626952.11      2406062.83       622679.21
      2409853.01       624137.64      2415245.44       617764.05
      2418903.15       621349.76      2422909.49       614220.09
       2429334.4        614985.4      2433124.69       611235.64
      2433563.43       614344.94      2437489.15       606939.38
      2441893.82       609667.84      2447668.66       602479.92

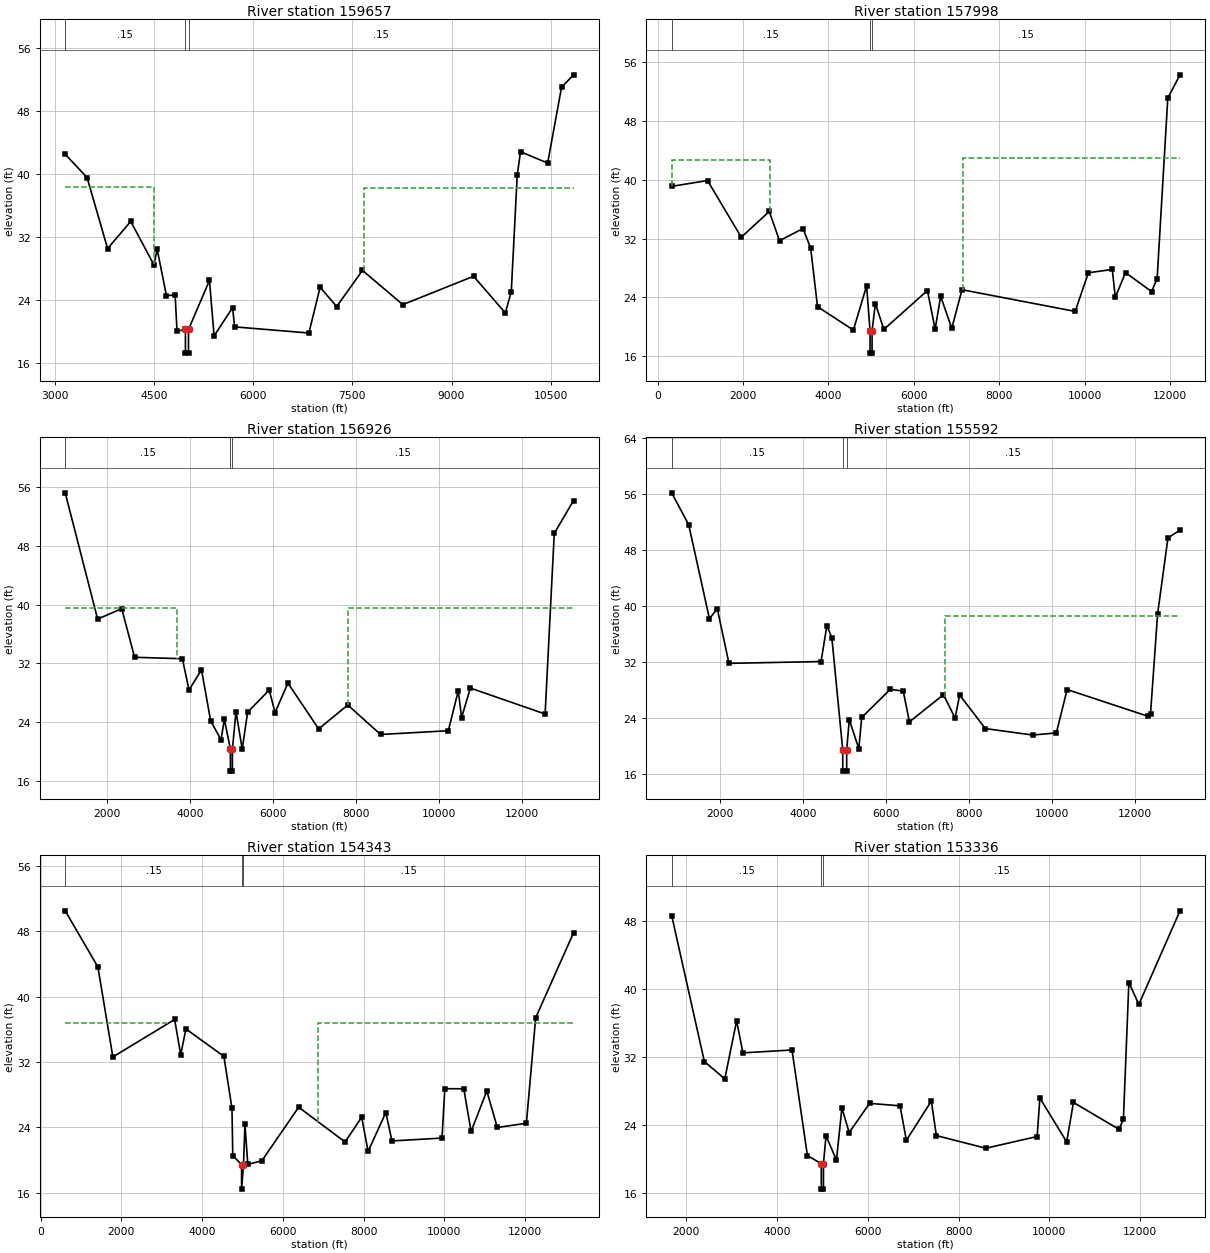
Type RM Length L Ch R = 1 ,159657  ,1659,1659,1659
BEGIN DESCRIPTION:
Black River 159.0
END DESCRIPTION:
XS GIS Cut Line= 4
       2369919.6       642918.25      2369933.86        641077.7
      2369959.26       636897.95      2370117.16       635240.99
#Sta/Elev= 30
  3159.1   42.53    3490   39.57    3800   30.57    4150   34.01    4500   28.51
    4550   30.47    4690   24.57    4820   24.72    4850   20.09  4976.8   20.31
  4976.9   17.31  5023.1   17.31  5023.2   20.31    5340   26.53    5410    19.5
    5690   23.08    5720   20.64  6842.9   19.86  7012.9   25.66  7262.9   23.22
  7652.9    27.8  8262.9   23.46  9332.9   27.06  9812.9    22.4  9902.9   25.11
  9992.9    39.9 10042.7   42.85 10452.7   41.41 10662.7   51.02   10844    52.6
#Mann= 3 ,-1,0
  3159.1     .15       0  4976.8     .05       0  5023.2     .15       0
#XS Ineff= 2 , 0
       0  4503.8   38.34  7669.6       0    38.3
Permanent Ineff=
       F       F
Bank Sta=4976.8,5023.2
XS Rating Curve= 0 ,0
Exp/Cntr=0.3,0.1

Type RM Length L Ch R = 1 ,157998  ,1072,1072,1072
BEGIN DESCRIPTION:
Black River 158.0
END DESCRIPTION:
XS GIS Cut Line= 4
      2370756.78       646803.79       2370931.1       644905.85
      2371095.51       642146.48      2371525.95       634923.59
#Sta/Elev= 30
   329.8    39.1  1169.8   39.89  1959.8   32.17  2615.7   35.68  2855.7    31.7
  3405.7   33.36  3585.7   30.68  3745.7   22.72  4585.7   19.54  4895.7   25.56
  4976.3    19.4  4976.4    16.4  5023.6    16.4  5023.7    19.4    5100   23.14
    5300   19.63    6320   24.92    6500   19.66    6630   24.13    6890   19.78
    7130   25.03    9780   22.08   10090   27.34   10650   27.79   10720      24
   10960   27.36   11570   24.78   11700   26.54   11950   51.12 12235.7   54.28
#Mann= 3 ,-1,0
   329.8     .15       0  4976.3     .05       0  5023.7     .15       0
#XS Ineff= 2 , 0
       0  2631.2   42.63  7158.5       0   42.93
Permanent Ineff=
       F       F
Bank Sta=4976.3,5023.7
XS Rating Curve= 0 ,0
Exp/Cntr=0.3,0.1

Type RM Length L Ch R = 1 ,156926  ,1334,1334,1334
BEGIN DESCRIPTION:
Black River 157.0
END DESCRIPTION:
XS GIS Cut Line= 3
      2371753.87       647003.37      2371641.95       643004.93
      2371563.94        634771.6
#Sta/Elev= 30
    1000   55.24    1780   38.02    2360   39.44    2670   32.81    3820   32.61
    3980   28.35    4280    31.1    4500   24.15    4750   21.54    4830   24.35
  4976.2   20.28  4976.4   17.28  5023.6   17.28  5023.8   20.28    5110   25.41
    5260   20.28    5390   25.32    5910   28.34    6050   25.27    6360   29.28
    7100   23.04    7800    26.3    8590   22.28   10220   22.79   10460   28.24
   10540   24.58   10750   28.61   12550   25.07   12770   49.72 13233.7   54.18
#Mann= 3 ,-1,0
    1000     .15       0  4976.2     .05       0  5023.8     .15       0
#XS Ineff= 2 , 0
       0  3692.7   39.51  7812.2       0   39.58
Permanent Ineff=
       F       F
Bank Sta=4976.2,5023.8
XS Rating Curve= 0 ,0
Exp/Cntr=0.3,0.1

Type RM Length L Ch R = 1 ,155592  ,1249,1249,1249
BEGIN DESCRIPTION:
Black River 156.0
END DESCRIPTION:
XS GIS Cut Line= 3
      2373596.23       646832.42      2372895.21       642721.66
       2371677.9       634733.68
#Sta/Elev= 30
   829.9   56.12  1239.9   51.58  1739.9   38.19  1929.9   39.61  2209.9   31.83
  4429.9   32.09  4569.9    37.2  4689.9   35.49  4952.5   19.48  4952.8   16.48
  5047.2   16.48  5047.5   19.48    5110   23.81    5340   19.67    5410   24.13
    6100   28.14    6410   27.87    6560    23.5    7380   27.37    7660   24.04
    7770   27.32    8390   22.54    9530   21.62   10100   21.92   10360    28.1
   12310   24.29   12370   24.65   12540   38.85   12790    49.7 13080.2   50.81
#Mann= 3 ,-1,0
   829.9     .15       0  4952.5     .05       0  5047.5     .15       0
#XS Ineff= 2 , 0
       0                  7405.6       0   38.62
Permanent Ineff=
       F       F
Bank Sta=4952.5,5047.5
XS Rating Curve= 0 ,0
Exp/Cntr=0.3,0.1

Type RM Length L Ch R = 1 ,154343  ,1007,1007,1007
BEGIN DESCRIPTION:
Black River 155.0
END DESCRIPTION:
XS GIS Cut Line= 3
      2375286.63       646357.57      2373995.08       642160.03
      2371810.85       634258.82
#Sta/Elev= 30
   608.3   50.49  1418.3   43.62  1788.3    32.6  3318.3   37.19  3468.3   32.88
  3598.3   36.03  4538.3   32.67  4738.3   26.32  4758.3   20.53  4976.2   19.42
  4976.4   16.42  5023.8   19.42    5060   24.37    5130   19.44    5480    19.9
    6390   26.45    7540   22.19    7950   25.22    8110   21.05    8550    25.8
    8700   22.32    9940   22.67   10010   28.72   10480    28.7   10660   23.48
   11050   28.43   11310   23.97   12030   24.48   12260    37.4 13197.6    47.8
#Mann= 3 ,-1,0
   608.3     .15       0  4976.2     .05       0  5023.8     .15       0
#XS Ineff= 2 , 0
       0  3129.5   36.77  6870.5       0   36.77
Permanent Ineff=
       F       F
Bank Sta=4976.2,5023.8
XS Rating Curve= 0 ,0
Exp/Cntr=0.3,0.1

Type RM Length L Ch R = 1 ,153336  ,675,675,675
BEGIN DESCRIPTION:
Black River 154.0
END DESCRIPTION:
XS GIS Cut Line= 3
      2375894.41       644572.19      2374717.87       641468.41
      2371867.82       634125.84
#Sta/Elev= 30
  1680.7    48.7  2400.7   31.52  2850.7   29.48  3110.7    36.3  3250.7   32.54
  4330.7   32.88  4670.7   20.45  4976.2   19.51  4976.4   16.51  5023.6   16.51
  5023.8   19.51    5080   22.78    5310   19.92    5430   26.06    5590   23.17
    6040    26.6    6710   26.31    6850   22.26    7400   26.87    7510   22.81
    8600   21.32    9730    22.7    9790   27.22   10380   22.07   10530   26.71
   11530   23.55   11630   24.72   11750   40.81   11970   38.24 12876.3   49.25
#Mann= 3 ,-1,0
  1680.7     .15       0  4976.2     .05       0  5023.8     .15       0
Bank Sta=4976.2,5023.8
XS Rating Curve= 0 ,0
Exp/Cntr=0.3,0.1

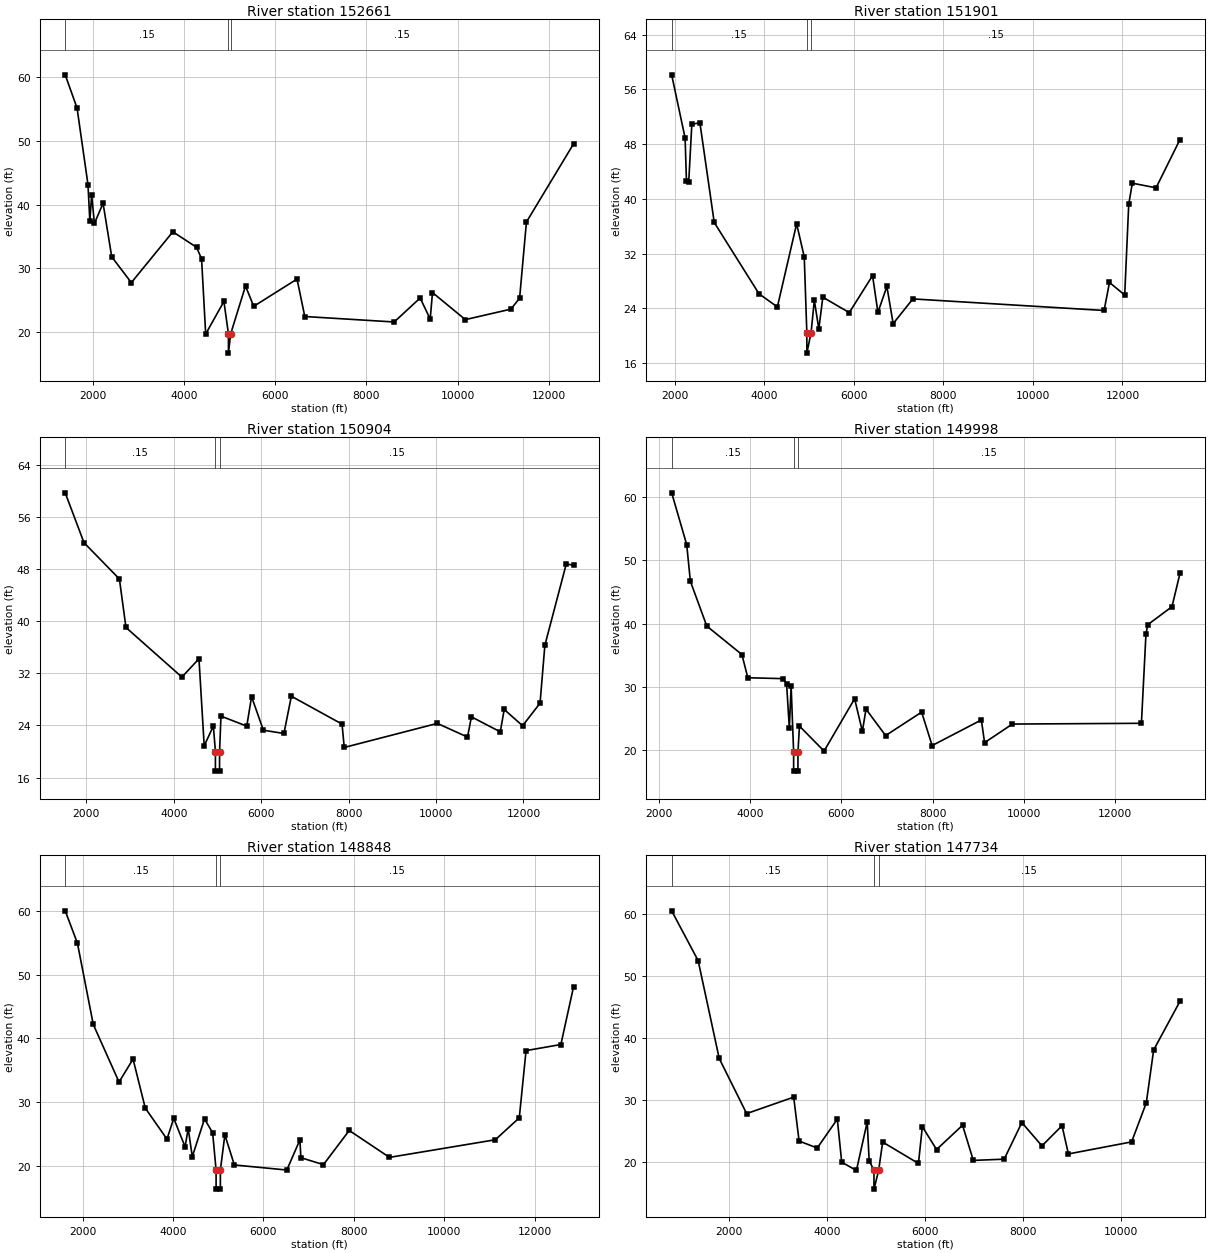
Type RM Length L Ch R = 1 ,152661  ,760,760,760
BEGIN DESCRIPTION:
Black River 153.0
END DESCRIPTION:
XS GIS Cut Line= 3
      2376521.18       644249.27      2375105.74       640935.72
       2371943.8       634087.88
#Sta/Elev= 30
  1396.8    60.4  1656.8   55.18  1896.8   43.12  1936.8   37.42  1976.8   41.58
  2036.8   37.06  2226.8   40.23  2416.8   31.82  2846.8   27.77  3756.8   35.75
  4276.8   33.32  4386.8    31.5  4476.8    19.7  4876.8   24.82  4976.2    19.7
  4976.4    16.7  5023.8    19.7    5350   27.24    5530   24.05    6480   28.33
    6650   22.45    8610   21.59    9180   25.36    9400   22.04    9450   26.21
   10170   21.96   11170   23.61   11360   25.33   11510   37.29 12542.6   49.55
#Mann= 3 ,-1,0
  1396.8     .15       0  4976.2     .05       0  5023.8     .15       0
Bank Sta=4976.2,5023.8
XS Rating Curve= 0 ,0
Exp/Cntr=0.3,0.1

Type RM Length L Ch R = 1 ,151901  ,997,997,997
BEGIN DESCRIPTION:
Black River 152.0
END DESCRIPTION:
XS GIS Cut Line= 3
      2376977.01       643964.36      2375807.09        641131.1
      2372285.68       633632.04
#Sta/Elev= 30
  1934.7   58.11  2234.7   48.87  2264.7   42.57  2314.7   42.38  2384.7   50.88
  2564.7   51.11  2884.7   36.54  3884.7   26.12  4294.7    24.2  4724.7   36.34
  4894.7   31.52  4952.5   20.45  4952.8   17.45  5047.5   20.45    5120   25.17
    5220   20.98    5310   25.62    5900   23.37    6420   28.77    6540   23.41
    6740   27.19    6880   21.76    7320   25.37   11590   23.68   11710   27.77
   12050   25.94   12140   39.19   12220   42.28   12750    41.6 13284.7   48.66
#Mann= 3 ,-1,0
  1934.7     .15       0  4952.5     .05       0  5047.5     .15       0
Bank Sta=4952.5,5047.5
XS Rating Curve= 0 ,0
Exp/Cntr=0.3,0.1

Type RM Length L Ch R = 1 ,150904  ,906,906,906
BEGIN DESCRIPTION:
Black River 151.0
END DESCRIPTION:
XS GIS Cut Line= 3
      2378230.57       643774.44      2376667.38       640661.04
      2372893.46       633442.09
#Sta/Elev= 30
  1516.2   59.78  1946.2   52.11  2756.2   46.53  2906.2   39.07  4186.2   31.44
  4576.2   34.26  4696.2   20.87  4906.2   23.92  4952.5   19.98  4952.8   16.98
  5047.2   16.98  5047.5   19.98    5080   25.44    5670    23.9    5780   28.43
    6050   23.27    6520   22.77    6690    28.5    7850   24.21    7900   20.62
   10030   24.32   10720   22.22   10810   25.33   11470   23.02   11560   26.46
   11980   23.96   12380   27.43   12490   36.33   12980   48.85 13145.9   48.64
#Mann= 3 ,-1,0
  1516.2     .15       0  4952.5     .05       0  5047.5     .15       0
Bank Sta=4952.5,5047.5
XS Rating Curve= 0 ,0
Exp/Cntr=0.3,0.1

Type RM Length L Ch R = 1 ,149998  ,1150,1150,1150
BEGIN DESCRIPTION:
Black River 150.0
END DESCRIPTION:
XS GIS Cut Line= 3
      2378876.37       643014.75       2377566.3       640628.63
      2373634.19       633176.16
#Sta/Elev= 30
  2277.9   60.69  2607.9   52.49  2687.9   46.71  3047.9   39.63  3817.9   35.13
  3947.9   31.46  4717.9   31.32  4797.9   30.55  4857.9   23.51  4897.9   30.13
  4952.5    19.7  4952.8    16.7  5047.2    16.7  5047.5    19.7    5080   23.82
    5620   19.87    6290   28.14    6460      23    6540   26.49    6970   22.32
    7760   26.03    7990   20.74    9070   24.79    9140    21.2    9750   24.14
   12580   24.26   12680    38.4   12720   39.85   13250   42.69 13426.2   47.96
#Mann= 3 ,-1,0
  2277.9     .15       0  4952.5     .05       0  5047.5     .15       0
Bank Sta=4952.5,5047.5
XS Rating Curve= 0 ,0
Exp/Cntr=0.3,0.1

Type RM Length L Ch R = 1 ,148848  ,1114,1114,1114
BEGIN DESCRIPTION:
Black River 149.0
END DESCRIPTION:
XS GIS Cut Line= 3
      2379389.19       642653.89      2374754.81       633613.05
      2373767.15        633176.2
#Sta/Elev= 30
  1616.5   60.06  1886.5   54.98  2236.5   42.21  2806.5   33.15  3116.5   36.76
  3386.5   29.06  3866.5   24.18  4016.5   27.45  4266.5   22.97  4336.5   25.83
  4426.5   21.42  4696.5   27.36  4876.5   25.17  4952.5   19.32  4952.8   16.32
  5047.2   16.32  5047.5   19.32  5146.5   24.85  5356.5   20.12  6516.5   19.32
  6806.5   24.07  6826.5   21.26  7326.5   20.17  7896.5   25.54  8786.5   21.31
 11126.5   24.08 11656.5   27.53 11805.9   38.09 12575.9   39.05 12855.9   48.11
#Mann= 3 ,-1,0
  1616.5     .15       0  4952.5     .05       0  5047.5     .15       0
Bank Sta=4952.5,5047.5
XS Rating Curve= 0 ,0
Exp/Cntr=0.3,0.1

Type RM Length L Ch R = 1 ,147734  ,1091,1091,1091
BEGIN DESCRIPTION:
Black River 148.0
END DESCRIPTION:
XS GIS Cut Line= 3
      2380053.94       642387.95      2378262.09       638616.36
      2375590.51       633024.25
#Sta/Elev= 30
   824.4   60.46  1364.4   52.45  1794.4   36.71  2354.4   27.84  3314.4   30.49
  3424.4   23.43  3794.4    22.3  4204.4   26.95  4294.4   20.02  4594.4   18.69
  4814.4   26.49  4854.4   20.29  4952.5   18.69  4952.8   15.69  5047.5   18.69
    5130   23.26    5860   19.82    5940   25.73    6230   22.06    6760   25.97
    6980   20.31    7610   20.51    7970    26.4    8380   22.65    8790   25.89
    8920   21.35   10210   23.29   10510   29.58   10660   38.08 11197.5   45.91
#Mann= 3 ,-1,0
   824.4     .15       0  4952.5     .05       0  5047.5     .15       0
Bank Sta=4952.5,5047.5
XS Rating Curve= 0 ,0
Exp/Cntr=0.3,0.1

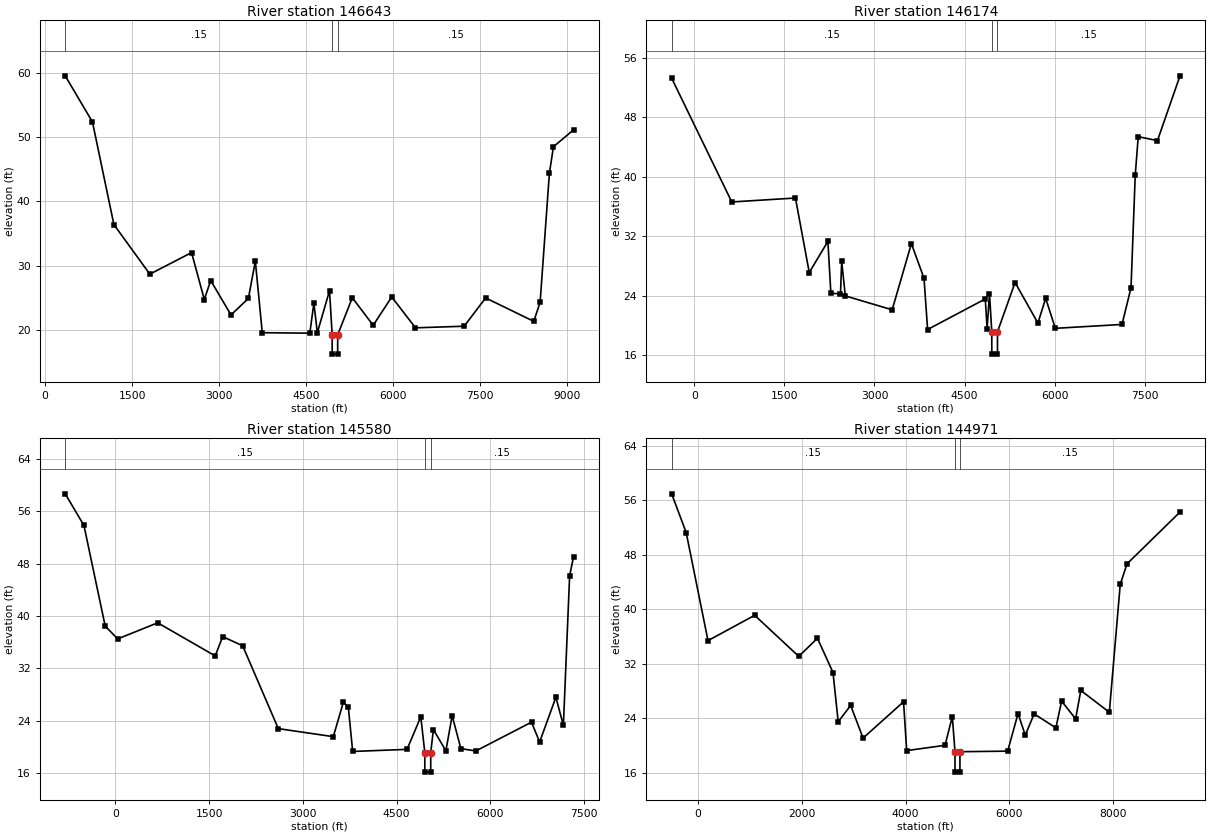
Type RM Length L Ch R = 1 ,146643  ,469,469,469
BEGIN DESCRIPTION:
Black River 147.0
END DESCRIPTION:
XS GIS Cut Line= 3
      2380889.65        641989.1      2378932.27        637767.5
      2376977.03       634144.88
#Sta/Elev= 30
   346.7    59.5   816.7   52.33  1186.7   36.37  1806.7   28.66  2526.7   32.01
  2746.7   24.71  2856.7   27.67  3206.7   22.32  3506.7   24.88  3626.7   30.67
  3746.7   19.55  4566.7   19.48  4636.7   24.15  4696.7   19.56  4906.7   26.08
  4952.4   19.22  4952.7   16.22  5047.3   16.22  5047.6   19.22    5300   24.99
    5660    20.7    5980   25.11    6390   20.31    7230   20.56    7600   24.96
    8430   21.32    8540   24.26    8700   44.35    8770   48.47  9116.6    51.1
#Mann= 3 ,-1,0
   346.7     .15       0  4952.4     .05       0  5047.6     .15       0
Bank Sta=4952.4,5047.6
XS Rating Curve= 0 ,0
Exp/Cntr=0.3,0.1

Type RM Length L Ch R = 1 ,146174  ,594,594,594
BEGIN DESCRIPTION:
Black River 146.0
END DESCRIPTION:
XS GIS Cut Line= 3
      2381862.12       642348.75      2379354.13       637594.18
       2377956.9        634843.4
#Sta/Elev= 30
  -375.5   53.26   624.5   36.62  1684.5   37.15  1914.5   27.13  2224.5   31.32
  2274.5   24.32  2434.5   24.29  2454.5   28.63  2514.5   23.99  3294.5   22.12
  3614.5   31.02  3824.5   26.36  3884.5   19.47  4844.5   23.58  4874.5   19.59
  4914.5   24.29  4952.4   19.16  4952.7   16.16  5047.3   16.16  5047.6   19.16
    5340   25.79    5720   20.34    5850   23.66    6010   19.63    7120   20.15
    7270   25.08    7340   40.19    7390    45.4    7710   44.87  8085.3   53.58
#Mann= 3 ,-1,0
  -375.5     .15       0  4952.4     .05       0  5047.6     .15       0
Bank Sta=4952.4,5047.6
XS Rating Curve= 0 ,0
Exp/Cntr=0.3,0.1

Type RM Length L Ch R = 1 ,145580  ,609,609,609
BEGIN DESCRIPTION:
Black River 145.0
END DESCRIPTION:
XS GIS Cut Line= 3
      2383082.53       642369.13      2379939.45       637492.82
      2378670.59       635535.76
#Sta/Elev= 30
  -801.5   58.66  -501.5   53.82  -161.5   38.43    38.5   36.48   678.5   38.94
  1598.5   33.88  1718.5   36.83  2038.5   35.42  2608.5   22.76  3488.5   21.53
  3648.5   26.78  3728.5   26.07  3798.5   19.27  4668.5   19.59  4888.5   24.57
  4952.4   19.11  4952.7   16.11  5047.3   16.11  5047.6   19.11    5090   22.61
    5290   19.38    5390   24.74    5530    19.7    5770   19.35    6660   23.75
    6790   20.71    7050   27.56    7170   23.25    7270   46.14  7332.4   49.03
#Mann= 3 ,-1,0
  -801.5     .15       0  4952.4     .05       0  5047.6     .15       0
Bank Sta=4952.4,5047.6
XS Rating Curve= 0 ,0
Exp/Cntr=0.3,0.1

Type RM Length L Ch R = 1 ,144971  ,1039,1039,1039
BEGIN DESCRIPTION:
Black River 144.0
END DESCRIPTION:
XS GIS Cut Line= 3
      2383123.19       642206.38      2380540.04       637365.53
      2378546.73       633541.62
#Sta/Elev= 30
  -509.4   56.97  -229.4   51.27   190.6   35.41  1090.6   39.13  1940.6    33.1
  2300.6   35.76  2600.6   30.73  2700.6   23.49  2940.6   25.89  3180.6    21.1
  3960.6   26.43  4020.6   19.26  4760.6   20.04  4900.6   24.26  4952.2    19.1
  4952.5    16.1  5047.5    16.1  5047.8    19.1  5967.5   19.18  6167.5   24.69
  6307.5   21.53  6477.5   24.65  6897.5    22.6  7007.5   26.53  7277.5   23.92
  7377.5    28.1  7927.5   24.89  8137.5   43.66  8267.5   46.68  9289.8   54.29
#Mann= 3 ,-1,0
  -509.4     .15       0  4952.2     .05       0  5047.8     .15       0
Bank Sta=4952.2,5047.8
XS Rating Curve= 0 ,0
Exp/Cntr=0.3,0.1