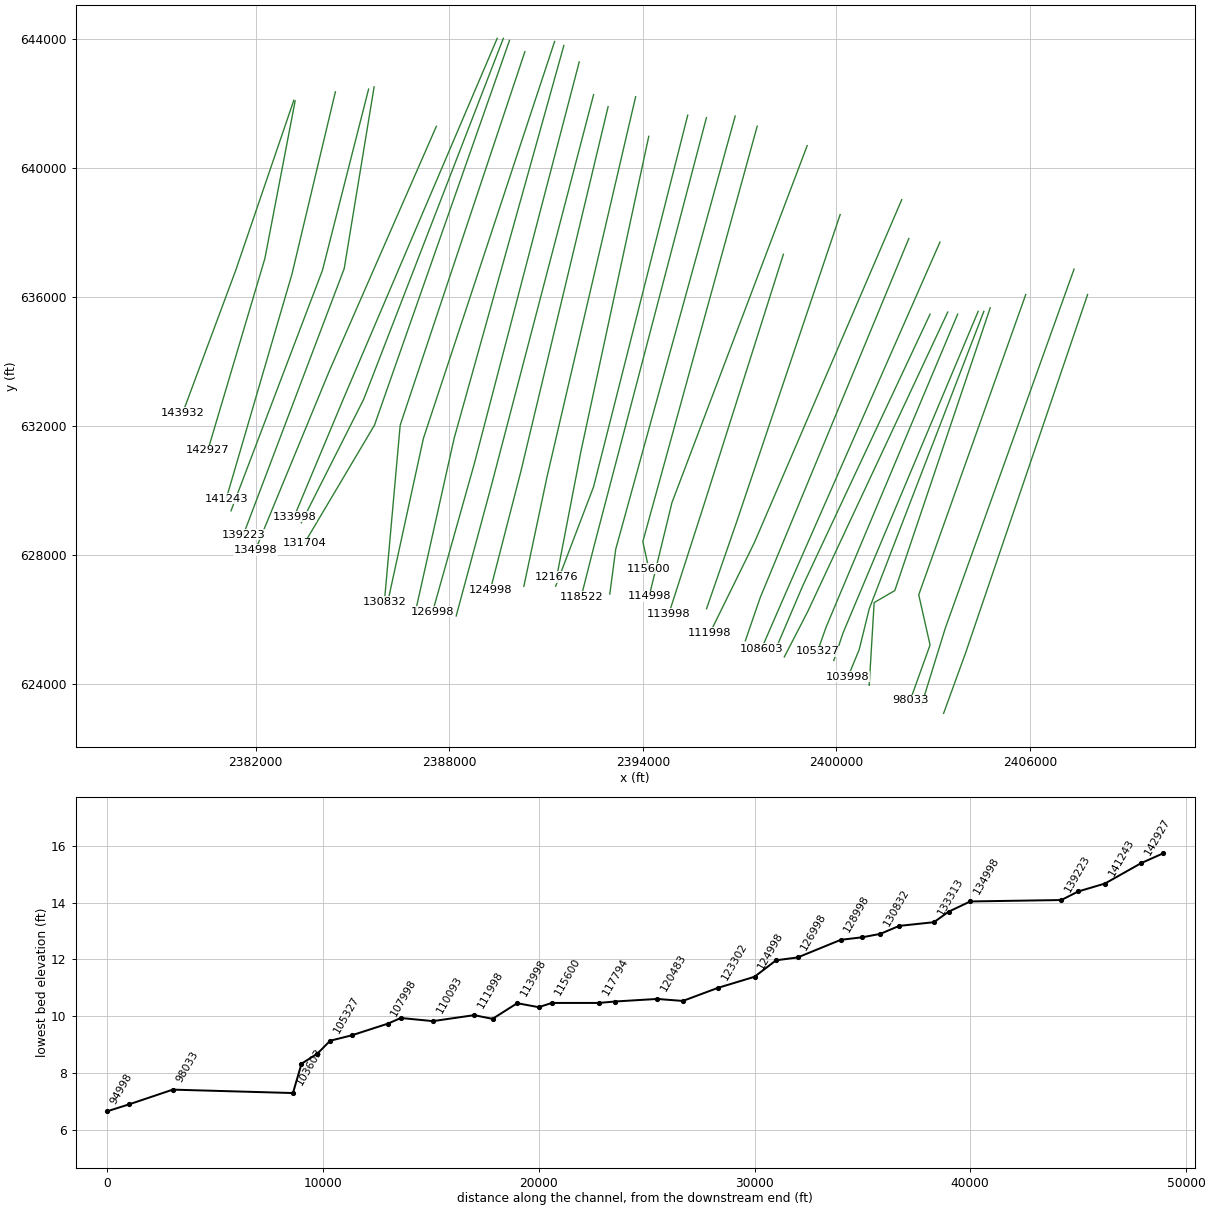
HEC-RAS study BlackRiver.prj: S-45-30 over Black River

--- BlackRiver.g02 (geometry) --- (continued)

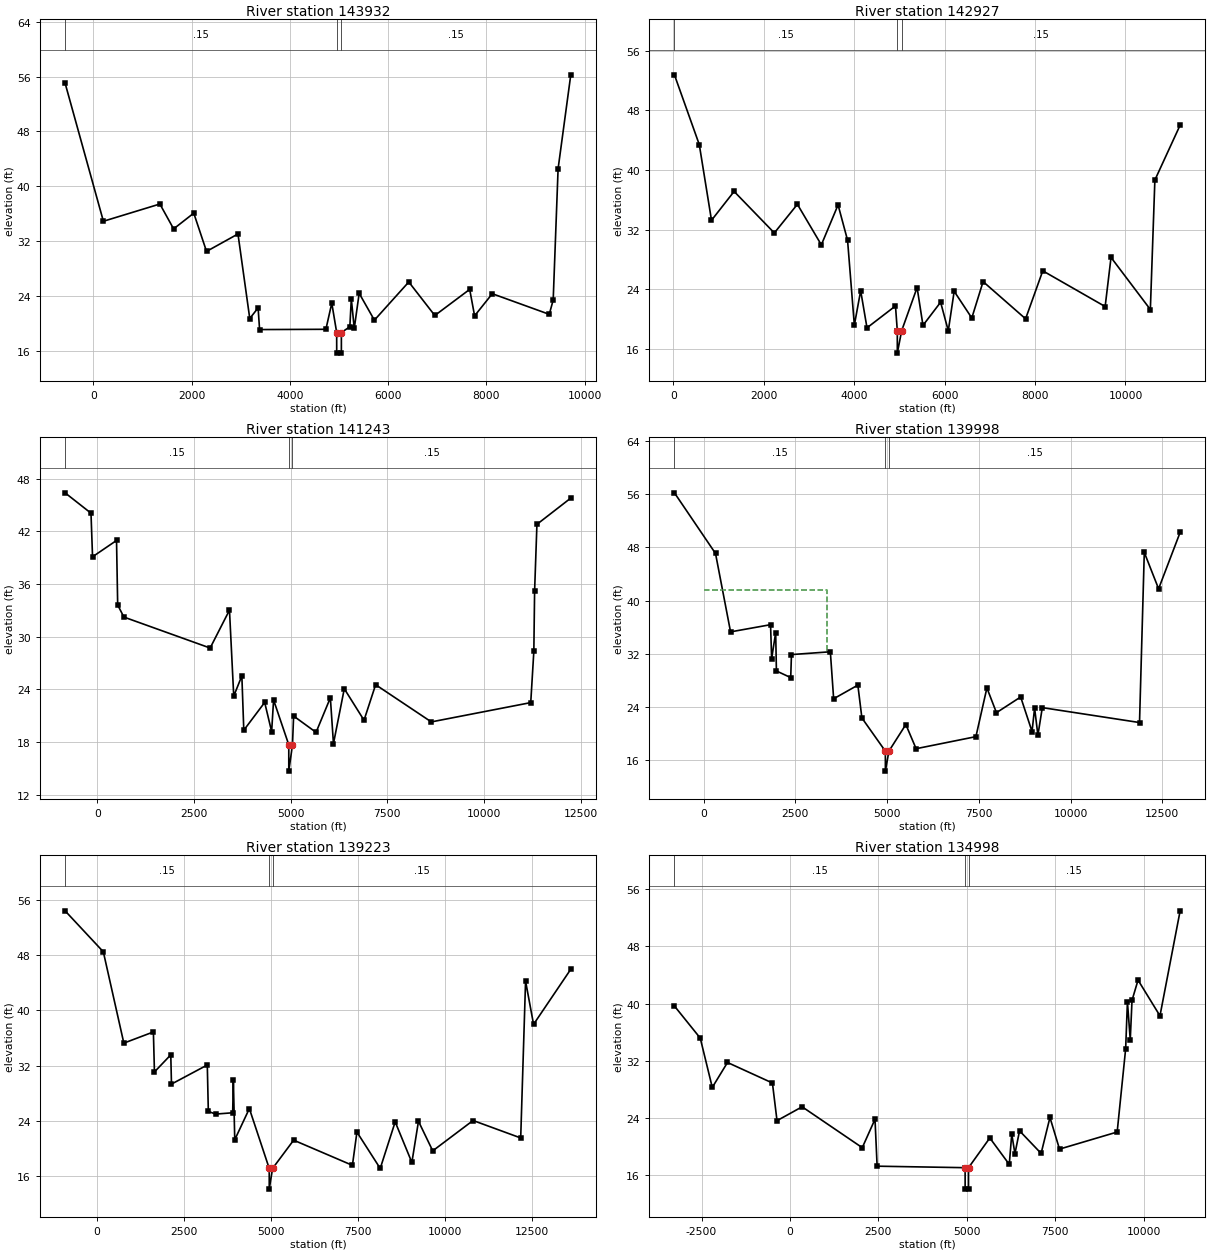
Type RM Length L Ch R = 1 ,143932  ,1005,1005,1005
BEGIN DESCRIPTION:
Black River 143.0
END DESCRIPTION:
XS GIS Cut Line= 3
      2383184.21       642104.67      2381383.15       636825.97
      2379739.94       632403.27
#Sta/Elev= 30
  -577.5   55.05   202.5   34.93  1352.5   37.44  1632.5   33.82  2042.5   36.11
  2302.5   30.54  2942.5   33.08  3182.5   20.77  3352.5   22.32  3382.5   19.16
  4732.5    19.2  4852.5   23.01  4952.2   18.73  4952.5   15.73  5047.5   15.73
  5047.8   18.73    5220   19.57    5250   23.63    5310   19.33    5410   24.44
    5720   20.53    6420   26.09    6950   21.21    7660   25.01    7760   21.16
    8120   24.38    9280   21.38    9360   23.46    9460   42.58  9718.1   56.25
#Mann= 3 ,-1,0
  -577.5     .15       0  4952.2     .05       0  5047.8     .15       0
Bank Sta=4952.2,5047.8
XS Rating Curve= 0 ,0
Exp/Cntr=0.3,0.1

Type RM Length L Ch R = 1 ,142927  ,1684,1684,1684
BEGIN DESCRIPTION:
Black River 142.0
END DESCRIPTION:
XS GIS Cut Line= 3
      2383224.88        642084.3      2382287.32       637195.08
      2380519.72       631243.32
#Sta/Elev= 30
    21.7   52.79   571.7   43.41   841.7   33.24  1341.7   37.12  2231.7   31.54
  2741.7   35.39  3271.7   29.94  3641.7   35.31  3851.7   30.56  4001.7   19.15
  4141.7   23.78  4281.7   18.79  4911.7   21.73  4952.2   18.39  4952.5   15.39
  5047.8   18.39    5390    24.2    5520   19.12    5910   22.23    6080   18.39
    6210    23.7    6600   20.11    6850      25    7790      20    8170   26.45
    9550   21.65    9680   28.25   10550   21.25   10650   38.65 11208.7   46.03
#Mann= 3 ,-1,0
    21.7     .15       0  4952.2     .05       0  5047.8     .15       0
Bank Sta=4952.2,5047.8
XS Rating Curve= 0 ,0
Exp/Cntr=0.3,0.1

Type RM Length L Ch R = 1 ,141243  ,1245,1245,1245
BEGIN DESCRIPTION:
Black River 141.0
END DESCRIPTION:
XS GIS Cut Line= 3
      2384472.22        642365.7      2383127.92       636715.46
      2381090.49       629741.96
#Sta/Elev= 30
  -830.8   46.39  -160.8   44.07  -120.8    39.1   499.2   40.96   529.2   33.61
   689.2   32.23  2919.2    28.7  3419.2   33.02  3529.2   23.22  3739.2   25.53
  3789.2   19.33  4329.2    22.5  4509.2   19.17  4559.2   22.78  4952.2   17.67
  4952.5   14.67  5047.8   17.67  5077.2   20.95  5657.2   19.09  6027.2   23.03
  6107.2    17.8  6387.2   24.06  6897.2   20.47  7197.2   24.52  8637.2   20.28
 11207.2   22.48 11287.2   28.32 11307.2   35.22 11367.2    42.8 12242.2   45.79
#Mann= 3 ,-1,0
  -830.8     .15       0  4952.2     .05       0  5047.8     .15       0
Bank Sta=4952.2,5047.8
XS Rating Curve= 0 ,0
Exp/Cntr=0.3,0.1

Type RM Length L Ch R = 1 ,139998  ,775,775,775
BEGIN DESCRIPTION:
Black River 140.0
END DESCRIPTION:
XS GIS Cut Line= 3
      2385501.46       642449.76      2384072.76       636830.64
       2381237.5       629363.82
#Sta/Elev= 30
  -797.9    56.2   322.1   47.09   732.1   35.31  1822.1   36.39  1852.1    31.3
  1962.1   35.21  1982.1   29.44  2372.1   28.44  2392.1    31.9  3452.1   32.32
  3542.1   25.26  4202.1   27.31  4312.1   22.38    4952   17.39  4952.3   14.39
    5048   17.39    5510   21.39    5790   17.76    7420   19.57    7720   26.89
    7980   23.17    8640   25.53    8950   20.34    9020   23.86    9110   19.78
    9230   23.93   11880   21.69   12010   47.25   12400   41.78   12987   50.26
#Mann= 3 ,-1,0
  -797.9     .15       0    4952     .05       0    5048     .15       0
#XS Ineff= 2 , 0
       0  3358.9   41.64               0
Permanent Ineff=
       F       F
Bank Sta=4952,5048
XS Rating Curve= 0 ,0
Exp/Cntr=0.3,0.1

Type RM Length L Ch R = 1 ,139223  ,4225,4225,4225
BEGIN DESCRIPTION:
Black River 139.0
END DESCRIPTION:
XS GIS Cut Line= 3
      2385672.27       642518.33      2384745.46        636880.3
      2381620.38       628621.59
#Sta/Elev= 30
  -919.4   54.44   180.6    48.5   770.6   35.26  1620.6   36.88  1650.6   31.08
  2120.6   33.56  2140.6   29.32  3170.6   32.09  3200.6   25.36  3410.6   24.97
  3900.6   25.16  3920.6   29.88  3960.6   21.25  4380.6   25.77    4952   17.09
  4952.3   14.09    5048   17.09  5654.3   21.19  7344.3   17.54  7474.3   22.36
  8144.3   17.09  8574.3   23.84  9054.3   17.96  9244.3   23.93  9654.3   19.64
 10814.3   24.04 12184.3   21.51 12324.3   44.25 12554.3   37.98 13624.5   45.97
#Mann= 3 ,-1,0
  -919.4     .15       0    4952     .05       0    5048     .15       0
Bank Sta=4952,5048
XS Rating Curve= 0 ,0
Exp/Cntr=0.3,0.1

Type RM Length L Ch R = 1 ,134998  ,1000,1000,1000
BEGIN DESCRIPTION:
Black River 135.0
END DESCRIPTION:
XS GIS Cut Line= 3
      2387601.91       641294.47      2384291.71       633720.54
      2381993.69        628145.6
#Sta/Elev= 30
 -3265.7   39.66 -2535.7   35.17 -2195.7   28.27 -1765.7   31.76  -495.7   28.89
  -365.7   23.62   344.3   25.56  2044.3   19.84  2404.3   23.82  2464.3   17.25
    4952   17.04  4952.3   14.04  5047.7   14.04    5048   17.04    5650    21.2
    6200    17.5    6270   21.74    6360      19    6490    22.2    7100   19.04
    7350   24.07    7620   19.64    9250   22.03    9490   33.67    9540   40.25
    9620   34.94    9670   40.45    9840   43.29   10460   38.29   11030   52.98
#Mann= 3 ,-1,0
 -3265.7     .15       0    4952     .05       0    5048     .15       0
Bank Sta=4952,5048
XS Rating Curve= 0 ,0
Exp/Cntr=0.3,0.1

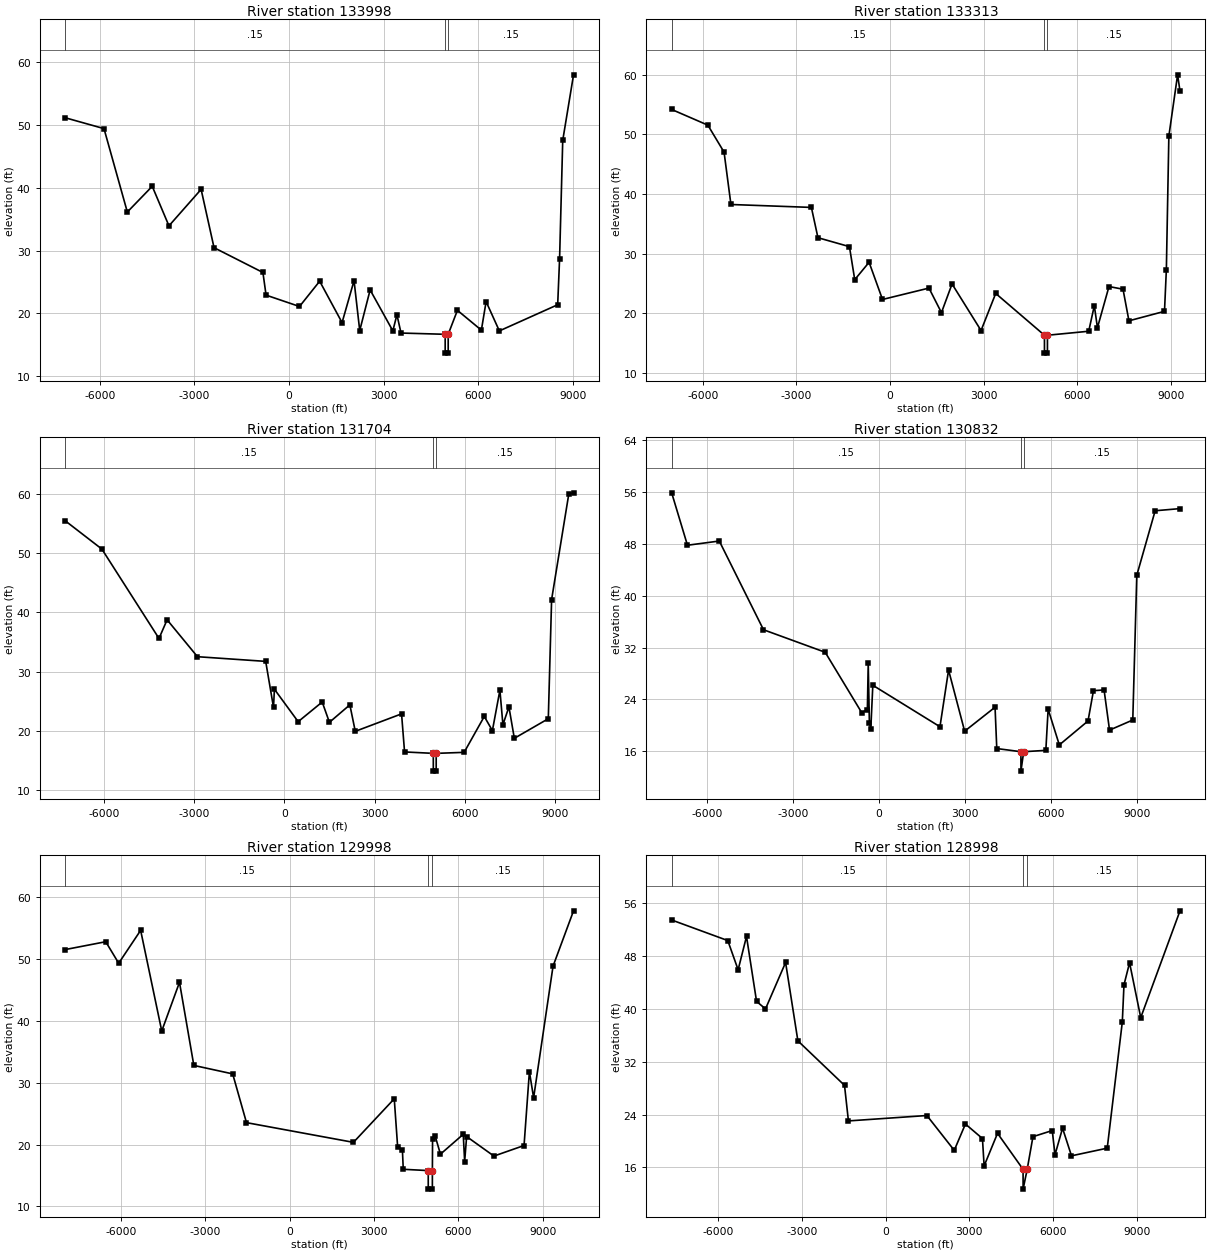
Type RM Length L Ch R = 1 ,133998  ,685,685,685
BEGIN DESCRIPTION:
Black River 134.0
END DESCRIPTION:
XS GIS Cut Line= 3
      2389486.97       644024.85      2384744.68       632895.06
      2383194.37       629183.21
#Sta/Elev= 30
   -7098   51.18   -5868   49.45   -5128   36.16   -4338   40.26   -3808   33.96
   -2788   39.77   -2378   30.48    -828   26.53    -728   22.92     332   21.11
     972   25.14    1682   18.54    2062   25.23    2242   17.28    2572   23.75
    3292   17.23    3422   19.79    3552   16.88    4952   16.68  4952.3   13.68
  5047.7   13.68    5048   16.68    5340    20.5    6100   17.34    6250   21.89
    6670   17.22    8520   21.39    8580   28.67    8680   47.57  9022.6   58.02
#Mann= 3 ,-1,0
   -7098     .15       0    4952     .05       0    5048     .15       0
Bank Sta=4952,5048
XS Rating Curve= 0 ,0
Exp/Cntr=0.3,0.1

Type RM Length L Ch R = 1 ,133313  ,1609,1609,1609
BEGIN DESCRIPTION:
Black River 133.0
END DESCRIPTION:
XS GIS Cut Line= 3
      2389677.65       644024.84      2385351.54       632829.58
      2383416.86       628992.58
#Sta/Elev= 30
   -7001   54.18   -5841   51.55   -5321   47.02   -5101   38.24   -2521   37.75
   -2311   32.67   -1301   31.17   -1131   25.63    -671   28.55    -241   22.31
    1249   24.22    1649    20.1    1989   24.91    2919    17.1    3389   23.32
    4952   16.31  4952.3   13.31  5047.7   13.31    5048   16.31    6371   16.98
    6551   21.27    6651   17.57    7021   24.48    7471   24.03    7661   18.73
    8801   20.32    8861   27.32    8941   49.72    9221   59.99  9298.2   57.26
#Mann= 3 ,-1,0
   -7001     .15       0    4952     .05       0    5048     .15       0
Bank Sta=4952,5048
XS Rating Curve= 0 ,0
Exp/Cntr=0.3,0.1

Type RM Length L Ch R = 1 ,131704  ,872,872,872
BEGIN DESCRIPTION:
Black River 132.0
END DESCRIPTION:
XS GIS Cut Line= 3
      2389868.34       643961.29      2385683.41        632021.5
      2383512.16        628356.9
#Sta/Elev= 30
 -7294.5   55.45 -6074.5   50.67 -4174.5   35.58 -3904.5   38.73 -2894.5    32.5
  -624.5   31.71  -364.5   23.94  -334.5   27.01   455.5   21.53  1255.5   24.85
  1495.5   21.42  2175.5   24.37  2355.5    19.9  3895.5   22.85  3995.5   16.42
  4951.9   16.18  4952.2   13.18  5047.8   13.18  5048.1   16.18  5977.5   16.35
  6647.5   22.41  6917.5   20.02  7167.5   26.85  7267.5   21.01  7467.5   24.03
  7647.5   18.72  8777.5   22.03  8887.5   42.15  9457.5   59.92    9617   60.17
#Mann= 3 ,-1,0
 -7294.5     .15       0  4951.9     .05       0  5048.1     .15       0
Bank Sta=4951.9,5048.1
XS Rating Curve= 0 ,0
Exp/Cntr=0.3,0.1

Type RM Length L Ch R = 1 ,130832  ,834,834,834
BEGIN DESCRIPTION:
Black River 131.0
END DESCRIPTION:
XS GIS Cut Line= 3
      2390345.07       643611.74      2386479.95       632019.32
      2385991.09        626545.4
#Sta/Elev= 30
 -7219.8   55.91 -6669.8   47.81 -5559.8   48.46 -4019.8   34.75 -1869.8   31.27
  -599.8   21.96  -399.8   22.37  -369.8   29.54  -329.8   20.38  -279.8   19.46
  -209.8   26.17  2130.2   19.76  2430.2   28.52  2990.2   19.07  4050.2   22.78
  4110.2   16.39  4951.9    15.9  4952.2    12.9  5048.1    15.9    5820   16.11
    5900   22.47    6290   16.95    7290   20.65    7480   25.34    7850   25.44
    8040   19.24    8850    20.8    8990   43.17    9630   53.14 10495.7   53.47
#Mann= 3 ,-1,0
 -7219.8     .15       0  4951.9     .05       0  5048.1     .15       0
Bank Sta=4951.9,5048.1
XS Rating Curve= 0 ,0
Exp/Cntr=0.3,0.1

Type RM Length L Ch R = 1 ,129998  ,1000,1000,1000
BEGIN DESCRIPTION:
Black River 130.0
END DESCRIPTION:
XS GIS Cut Line= 3
      2391266.72       643929.58      2387200.13       631612.53
      2386118.22       626640.79
#Sta/Elev= 30
   -7971   51.55   -6531   52.82   -6071   49.34   -5291   54.66   -4541   38.37
   -3911   46.25   -3401    32.8   -2021   31.43   -1531   23.54    2269   20.35
    3719    27.4    3839   19.64    4009   19.07    4039   15.99  4926.5   15.78
    4927   12.78    5073   12.78  5073.5   15.78    5080   20.85    5170    21.4
    5360   18.44    6170   21.65    6220   17.25    6290   21.29    7260   18.13
    8330   19.84    8520   31.79    8670   27.57    9360   48.86 10088.1   57.82
#Mann= 3 ,-1,0
   -7971     .15       0  4926.5     .05       0  5073.5     .15       0
Bank Sta=4926.5,5073.5
XS Rating Curve= 0 ,0
Exp/Cntr=0.3,0.1

Type RM Length L Ch R = 1 ,128998  ,2000,2000,2000
BEGIN DESCRIPTION:
Black River 129.0
END DESCRIPTION:
XS GIS Cut Line= 3
      2391552.72       643802.37       2388151.2       631609.14
      2386944.51        626195.8
#Sta/Elev= 30
 -7658.8   53.49 -5648.8   50.37 -5278.8   45.94 -4978.8      51 -4618.8   41.15
 -4298.8   40.01 -3578.8   47.05 -3138.8   35.17 -1468.8   28.42 -1328.8   23.03
  1481.2   23.85  2461.2   18.57  2861.2   22.56  3471.2   20.36  3531.2   16.21
  4011.2   21.15  4926.5   15.69    4927   12.69  5073.5   15.69    5280   20.64
    5970   21.57    6070    17.9    6340   21.93    6660   17.74    7940    18.9
    8480   38.02    8540   43.66    8740   47.01    9140   38.69 10546.2   54.88
#Mann= 3 ,-1,0
 -7658.8     .15       0  4926.5     .05       0  5073.5     .15       0
Bank Sta=4926.5,5073.5
XS Rating Curve= 0 ,0
Exp/Cntr=0.3,0.1

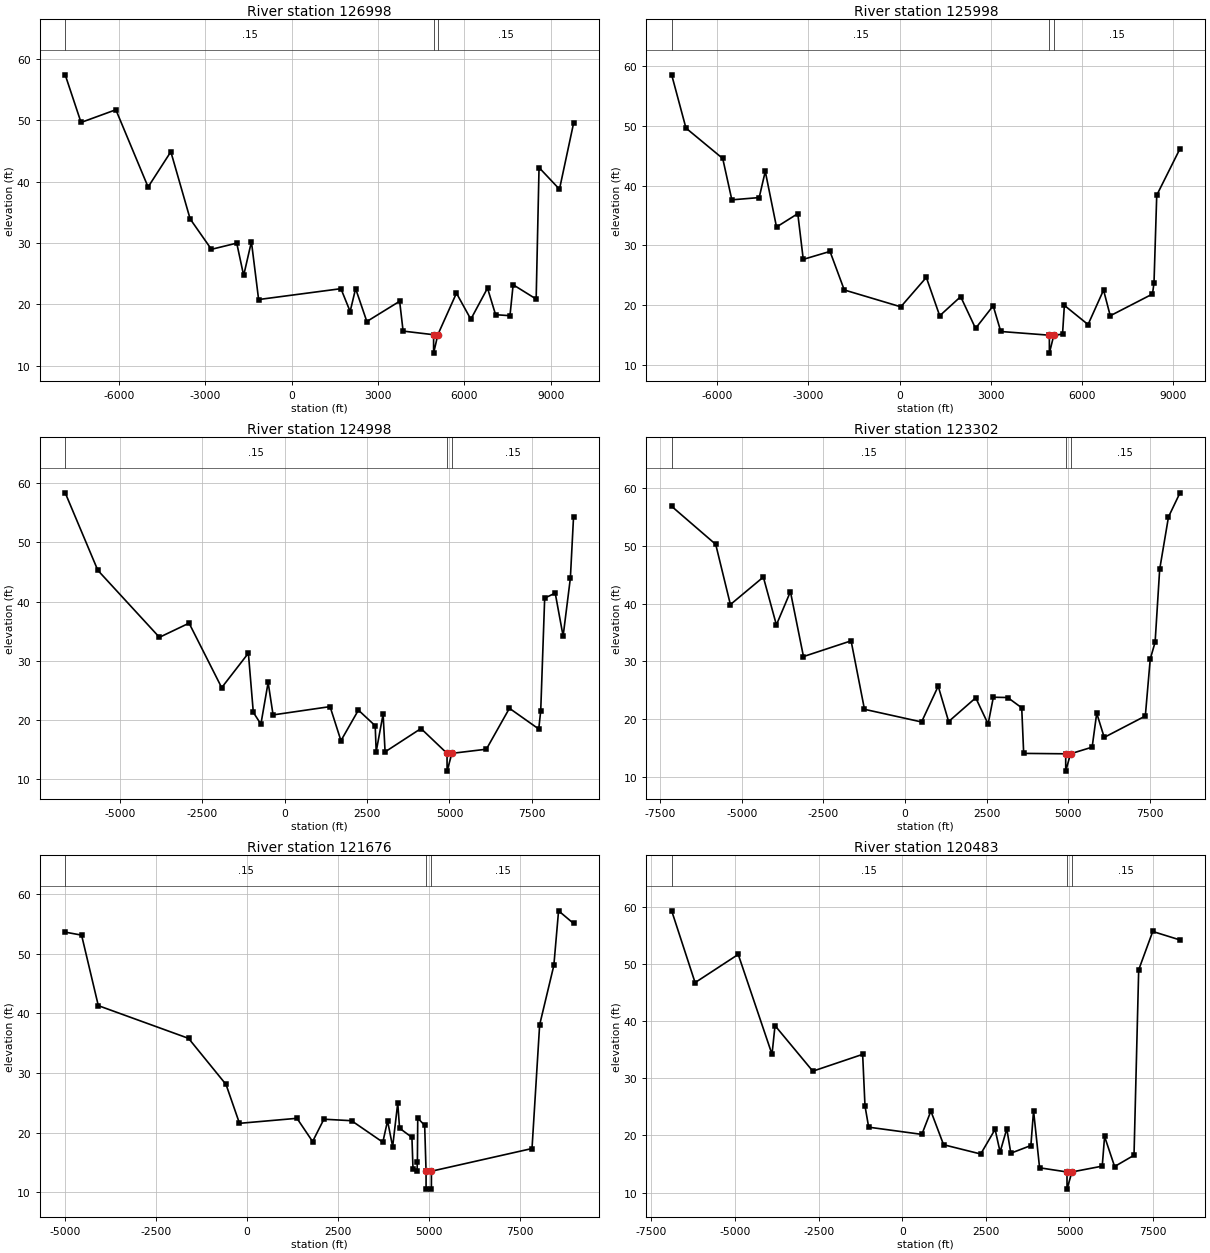
Type RM Length L Ch R = 1 ,126998  ,1000,1000,1000
BEGIN DESCRIPTION:
Black River 127.0
END DESCRIPTION:
XS GIS Cut Line= 3
      2392029.45       643293.94      2388780.58       630837.45
      2387484.79       626227.61
#Sta/Elev= 30
 -7873.2   57.41 -7323.2   49.65 -6113.2   51.72 -4993.2   39.13 -4203.2   44.88
 -3533.2   33.94 -2793.2   28.98 -1913.2   29.99 -1673.2   24.72 -1403.2   30.22
 -1153.2    20.8  1706.8   22.57  2026.8   18.85  2216.8   22.58  2606.8   17.22
  3746.8   20.52  3866.8   15.66  4926.5   15.07    4927   12.07  5073.5   15.07
    5720   21.84    6220   17.59    6800   22.66    7080   18.33    7580   18.17
    7690   23.21    8490   20.88    8590    42.3    9300   38.77  9788.5   49.49
#Mann= 3 ,-1,0
 -7873.2     .15       0  4926.5     .05       0  5073.5     .15       0
Bank Sta=4926.5,5073.5
XS Rating Curve= 0 ,0
Exp/Cntr=0.3,0.1

Type RM Length L Ch R = 1 ,125998  ,1000,1000,1000
BEGIN DESCRIPTION:
Black River 126.0
END DESCRIPTION:
XS GIS Cut Line= 3
      2392474.38       642276.92      2389315.17       630180.56
      2388215.75        626100.5
#Sta/Elev= 30
 -7502.1   58.54 -7032.1   49.63 -5822.1   44.54 -5522.1   37.62 -4622.1      38
 -4422.1   42.39 -4052.1   33.07 -3352.1   35.31 -3172.1   27.66 -2292.1   28.99
 -1822.1   22.54    37.9   19.72   877.9   24.64  1317.9   18.22  2007.9   21.42
  2497.9   16.11  3077.9   19.89  3327.9   15.59  4926.5   14.97    4927   11.97
  5073.5   14.97    5360   15.14    5420   19.96    6200   16.75    6710   22.52
    6930   18.22    8320   21.86    8370   23.72    8460   38.39  9225.6   46.18
#Mann= 3 ,-1,0
 -7502.1     .15       0  4926.5     .05       0  5073.5     .15       0
Bank Sta=4926.5,5073.5
XS Rating Curve= 0 ,0
Exp/Cntr=0.3,0.1

Type RM Length L Ch R = 1 ,124998  ,1696,1696,1696
BEGIN DESCRIPTION:
Black River 125.0
END DESCRIPTION:
XS GIS Cut Line= 3
      2392923.98       641903.65      2390213.69       630558.49
       2389274.4       626911.51
#Sta/Elev= 30
 -6664.4   58.37 -5674.4   45.29 -3804.4   33.98 -2904.4   36.37 -1914.4   25.48
 -1104.4    31.3  -954.4   21.31  -724.4   19.32  -504.4   26.36  -354.4   20.88
  1375.6   22.28  1705.6   16.53  2235.6   21.69  2745.6   19.05  2775.6   14.69
  2985.6   21.02  3045.6   14.64  4135.6   18.58  4926.5   14.39    4927   11.39
  5073.5   14.39    6120   15.09    6820      22    7710    18.5    7770   21.57
    7890    40.6    8210   41.44    8450   34.18    8670   43.97    8766   54.29
#Mann= 3 ,-1,0
 -6664.4     .15       0  4926.5     .05       0  5073.5     .15       0
Bank Sta=4926.5,5073.5
XS Rating Curve= 0 ,0
Exp/Cntr=0.3,0.1

Type RM Length L Ch R = 1 ,123302  ,1626,1626,1626
BEGIN DESCRIPTION:
Black River 124.0
END DESCRIPTION:
XS GIS Cut Line= 3
      2393777.38       642213.34      2391033.55       630429.82
      2390313.29       627022.17
#Sta/Elev= 30
 -7151.8   56.83 -5801.8   50.25 -5351.8   39.83 -4341.8   44.59 -3941.8   36.31
 -3511.8   42.07 -3111.8   30.83 -1651.8   33.55 -1241.8    21.7   508.2   19.51
  1018.2    25.7  1338.2   19.58  2168.2   23.69  2548.2   19.15  2708.2   23.79
  3148.2   23.74  3578.2   21.96  3638.2   14.07  4926.5      14    4927      11
  5073.5      14    5737   15.15    5877   21.03    6107   16.84    7367   20.54
    7517   30.38    7667   33.32    7807   45.93    8077      55  8429.9   59.17
#Mann= 3 ,-1,0
 -7151.8     .15       0  4926.5     .05       0  5073.5     .15       0
Bank Sta=4926.5,5073.5
XS Rating Curve= 0 ,0
Exp/Cntr=0.3,0.1

Type RM Length L Ch R = 1 ,121676  ,1193,1193,1193
BEGIN DESCRIPTION:
Black River 122.0
END DESCRIPTION:
XS GIS Cut Line= 3
      2394184.25       640984.68      2392083.78       631217.49
      2391330.26       627308.14
#Sta/Elev= 30
   -4992   53.58   -4542   53.08   -4082   41.27   -1602   35.79    -572   28.07
    -202   21.56    1378    22.4    1808   18.51    2118   22.25    2878      22
    3738    18.4    3868   21.98    4008   17.65    4148   24.96    4198   20.75
    4538    19.2    4568   13.84    4678   13.62    4688   15.12    4698   22.44
    4888   21.21  4926.4   13.54  4926.8   10.54  5073.2   10.54  5073.6   13.54
  7838.5   17.34  8048.5   38.06  8438.5      48  8568.5   57.15  8979.8   55.04
#Mann= 3 ,-1,0
   -4992     .15       0  4926.4     .05       0  5073.6     .15       0
Bank Sta=4926.4,5073.6
XS Rating Curve= 0 ,0
Exp/Cntr=0.3,0.1

Type RM Length L Ch R = 1 ,120483  ,1961,1961,1961
BEGIN DESCRIPTION:
Black River 121.0
END DESCRIPTION:
XS GIS Cut Line= 3
      2395392.01       641641.05      2392474.41       630110.86
      2391298.48       627022.13
#Sta/Elev= 30
 -6893.6   59.26 -6193.6   46.71 -4903.6   51.64 -3893.6   34.18 -3803.6   39.19
 -2673.6   31.23 -1183.6   34.17 -1113.6   25.15 -1003.6   21.44   586.4   20.18
   856.4   24.25  1236.4   18.37  2346.4   16.75  2776.4   21.06  2926.4    17.1
  3126.4   21.16  3246.4   16.89  3846.4   18.23  3926.4   24.32  4106.4   14.34
  4926.4   13.61  4926.8   10.61  5073.6   13.61    5980   14.63    6050   19.81
    6350   14.56    6930   16.53    7070   48.95    7490   55.65    8305   54.17
#Mann= 3 ,-1,0
 -6893.6     .15       0  4926.4     .05       0  5073.6     .15       0
Bank Sta=4926.4,5073.6
XS Rating Curve= 0 ,0
Exp/Cntr=0.3,0.1

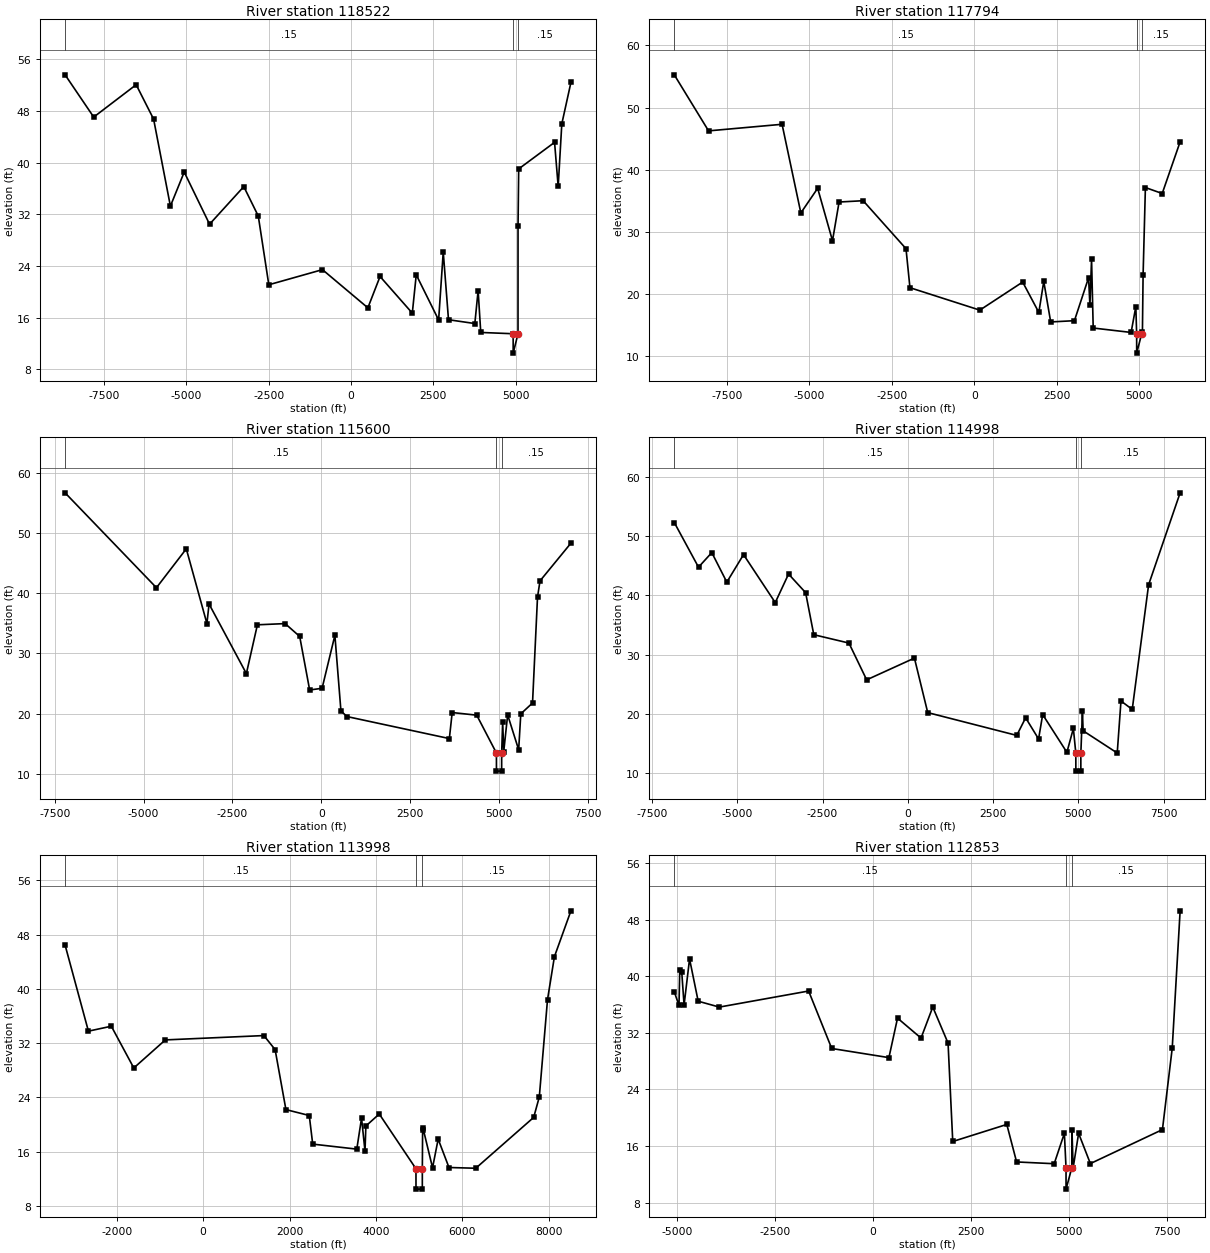
Type RM Length L Ch R = 1 ,118522  ,728,728,728
BEGIN DESCRIPTION:
Black River 119.0
END DESCRIPTION:
XS GIS Cut Line= 3
      2395970.95       641563.12      2392505.39       628336.96
      2392088.63       626691.88
#Sta/Elev= 30
 -8688.3   53.59 -7818.3   47.05 -6528.3   52.06 -5998.3   46.73 -5488.3   33.27
 -5068.3   38.54 -4298.3   30.47 -3258.3   36.29 -2818.3   31.74 -2498.3    21.1
  -868.3   23.44   511.7   17.53   881.7   22.38  1861.7   16.71  1981.7   22.64
  2661.7   15.65  2801.7   26.17  2961.7   15.69  3761.7    15.1  3861.7   20.21
  3941.7   13.72  4926.4   13.52  4926.8   10.52  5073.6   13.52  5074.4   30.24
  5094.4   39.03  6184.4   43.14  6294.4   36.31  6404.4      46  6681.4   52.41
#Mann= 3 ,-1,0
 -8688.3     .15       0  4926.4     .05       0  5073.6     .15       0
Bank Sta=4926.4,5073.6
XS Rating Curve= 0 ,0
Exp/Cntr=0.3,0.1

Type RM Length L Ch R = 1 ,117794  ,2194,2194,2194
BEGIN DESCRIPTION:
Black River 118.0
END DESCRIPTION:
XS GIS Cut Line= 3
      2396862.33       641614.77      2393160.27       628171.82
      2392976.48       626780.29
#Sta/Elev= 30
 -9101.9   55.26 -8061.9   46.24 -5831.9    47.3 -5261.9   33.03 -4751.9      37
 -4301.9   28.56 -4101.9   34.79 -3371.9      35 -2071.9   27.28 -1951.9      21
   168.1   17.39  1468.1   21.91  1958.1   17.02  2108.1   22.01  2318.1   15.49
  3038.1   15.69  3468.1   22.61  3508.1   18.14  3558.1    25.6  3608.1   14.51
  4758.1    13.8  4901.5   17.96  4926.4   13.47  4926.8   10.47  5073.6   13.47
  5101.5   13.95  5121.5   23.03  5191.5   37.12  5701.5   36.16  6245.1   44.48
#Mann= 3 ,-1,0
 -9101.9     .15       0  4926.4     .05       0  5073.6     .15       0
Bank Sta=4926.4,5073.6
XS Rating Curve= 0 ,0
Exp/Cntr=0.3,0.1

Type RM Length L Ch R = 1 ,115600  ,602,602,602
BEGIN DESCRIPTION:
Black River 116.0
END DESCRIPTION:
XS GIS Cut Line= 3
      2397544.99       641299.73      2394000.46       628408.12
      2394184.25        627567.9
#Sta/Elev= 30
 -7208.3   56.63 -4638.3   40.89 -3798.3   47.34 -3218.3   34.95 -3158.3   38.19
 -2108.3   26.65 -1798.3   34.74 -1018.3   34.94  -608.3   32.81  -328.3   23.93
    21.7   24.21   381.7      33   551.7   20.46   721.7   19.52  3601.7   15.87
  3681.7   20.19  4371.7   19.75  4926.4   13.47  4926.8   10.47  5073.2   10.47
  5073.6   13.47  5101.7   18.65  5131.7   13.72  5241.7    19.8  5551.7   14.01
  5611.7   19.97  5941.7   21.77  6081.7    39.3  6151.7   42.02  7021.8   48.28
#Mann= 3 ,-1,0
 -7208.3     .15       0  4926.4     .05       0  5073.6     .15       0
Bank Sta=4926.4,5073.6
XS Rating Curve= 0 ,0
Exp/Cntr=0.3,0.1

Type RM Length L Ch R = 1 ,114998  ,1000,1000,1000
BEGIN DESCRIPTION:
Black River 115.0
END DESCRIPTION:
XS GIS Cut Line= 3
      2399094.08       640695.82       2394902.3       629616.79
      2394197.38       626717.25
#Sta/Elev= 30
 -6845.5   52.29 -6135.5   44.75 -5745.5   47.21 -5305.5   42.22 -4815.5   46.87
 -3885.5   38.77 -3495.5   43.59 -2995.5   40.45 -2755.5   33.35 -1725.5   31.94
 -1205.5   25.73   194.5    29.4   584.5    20.2  3194.5   16.35  3454.5   19.32
  3834.5   15.75  3954.5   19.87  4664.5   13.49  4854.5   17.53  4926.4   13.32
  4926.8   10.32  5073.2   10.32  5073.6   13.32    5120   20.39    5140   17.13
    6140   13.38    6250   22.16    6580   20.74    7060   41.78    7984    57.3
#Mann= 3 ,-1,0
 -6845.5     .15       0  4926.4     .05       0  5073.6     .15       0
Bank Sta=4926.4,5073.6
XS Rating Curve= 0 ,0
Exp/Cntr=0.3,0.1

Type RM Length L Ch R = 1 ,113998  ,1145,1145,1145
BEGIN DESCRIPTION:
Black River 114.0
END DESCRIPTION:
XS GIS Cut Line= 3
      2398356.31       637324.63      2395882.35       629514.07
      2394806.51       626171.12
#Sta/Elev= 30
   -3193   46.46   -2653   33.76   -2123   34.49   -1603   28.33    -873   32.47
    1407   33.11    1667   31.04    1917   22.19    2457   21.32    2537    17.1
    3557   16.36    3667   20.93    3747   16.07    3767   19.77    4077   21.54
  4926.4   13.46  4926.8   10.46  5073.2   10.46  5073.6   13.46    5080   19.19
    5090   19.43    5310   13.61    5440   17.84    5690   13.65    6310   13.54
    7650   21.04    7780   24.05    7970   38.41    8130   44.75  8511.8   51.51
#Mann= 3 ,-1,0
   -3193     .15       0  4926.4     .05       0  5073.6     .15       0
Bank Sta=4926.4,5073.6
XS Rating Curve= 0 ,0
Exp/Cntr=0.3,0.1

Type RM Length L Ch R = 1 ,112853  ,855,855,855
BEGIN DESCRIPTION:
Black River 113.0
END DESCRIPTION:
XS GIS Cut Line= 3
      2400116.49       638558.21      2396914.12       629038.84
      2395975.01       626325.01
#Sta/Elev= 30
 -5075.8   37.79 -4955.8   35.86 -4935.8   40.93 -4885.8   40.62 -4825.8   35.92
 -4685.8   42.43 -4465.8   36.46 -3925.8   35.63 -1645.8    37.9 -1055.8   29.78
   404.2   28.49   624.2   34.07  1224.2   31.25  1524.2   35.64  1914.2   30.54
  2034.2   16.64  3414.2   19.05  3664.2   13.75  4624.2    13.5  4884.2    17.8
  4926.4   12.91  4926.8    9.91  5073.6   12.91  5077.8   18.26  5107.8   12.91
  5247.8   17.79  5547.8   13.52  7387.8   18.32  7637.8   29.82  7839.5   49.23
#Mann= 3 ,-1,0
 -5075.8     .15       0  4926.4     .05       0  5073.6     .15       0
Bank Sta=4926.4,5073.6
XS Rating Curve= 0 ,0
Exp/Cntr=0.3,0.1

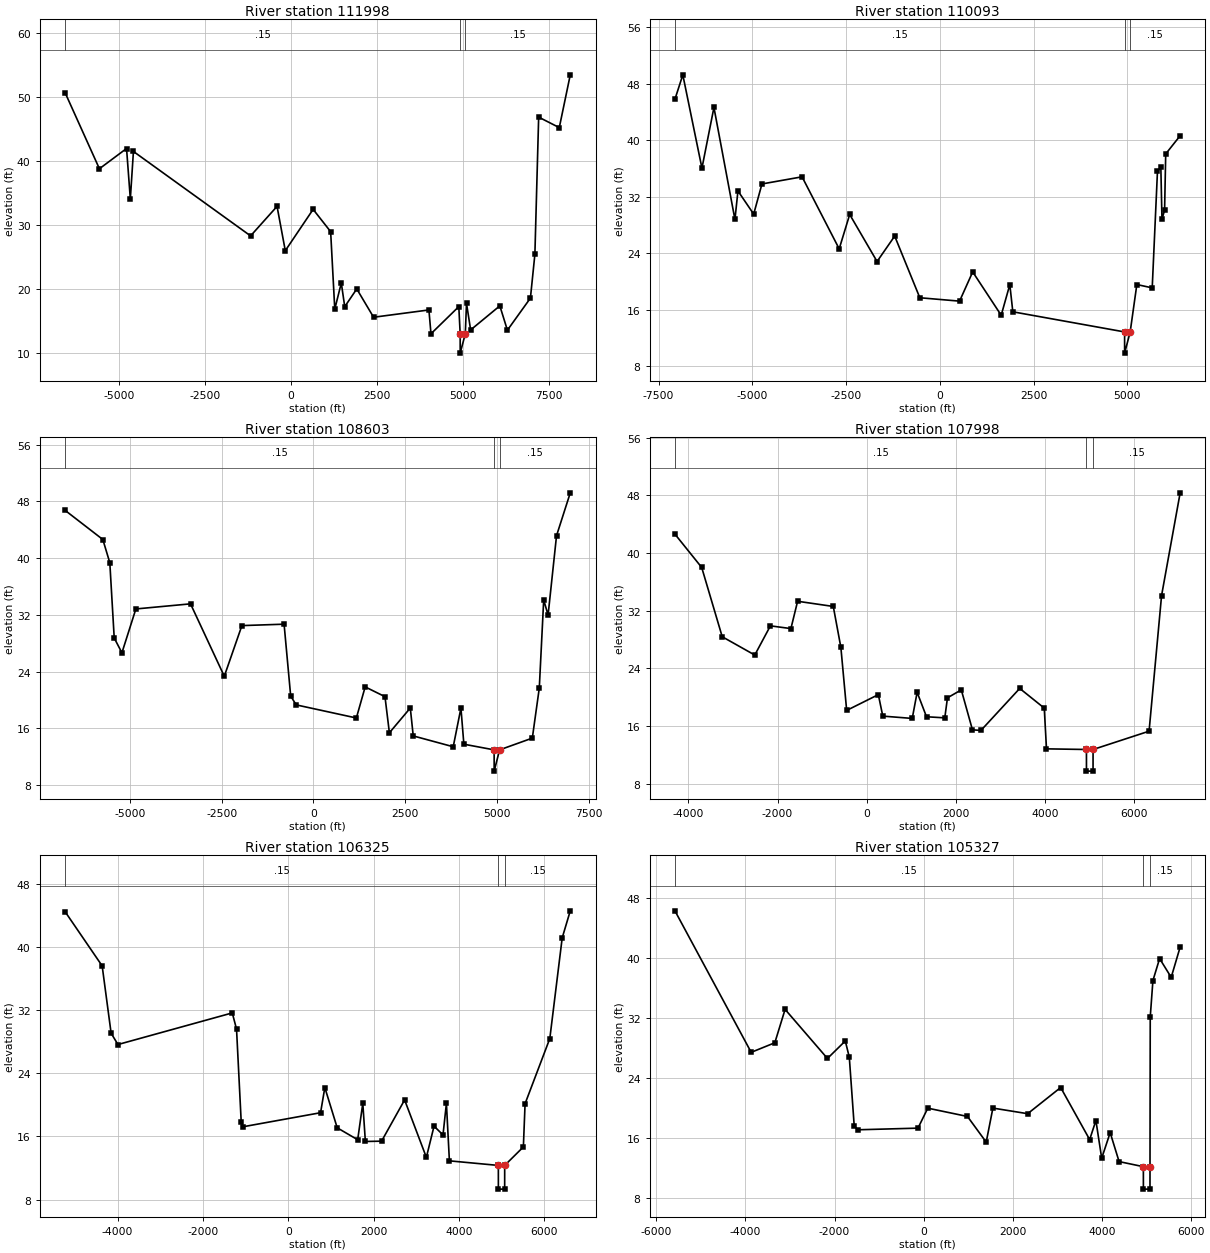
Type RM Length L Ch R = 1 ,111998  ,1905,1905,1905
BEGIN DESCRIPTION:
Black River 112.0
END DESCRIPTION:
XS GIS Cut Line= 3
      2402024.75       639018.84      2397459.67       628382.84
      2396080.62       625573.25
#Sta/Elev= 30
 -6574.3   50.71 -5574.3   38.82 -4784.3   41.98 -4674.3    34.1 -4584.3   41.52
 -1174.3   28.34  -404.3   32.95  -164.3   26.03   645.7   32.48  1155.7      29
  1275.7    16.9  1465.7   20.99  1565.7   17.29  1915.7   20.06  2405.7   15.64
  4015.7   16.78  4075.7   13.06  4885.7    17.3  4925.8   13.04  4926.2   10.04
  5074.3   13.04    5110    17.8    5230   13.66    6080   17.42    6300   13.62
    6970   18.63    7100   25.46    7210   46.88    7810   45.24  8129.8   53.48
#Mann= 3 ,-1,0
 -6574.3     .15       0  4925.8     .05       0  5074.3     .15       0
Bank Sta=4925.8,5074.3
XS Rating Curve= 0 ,0
Exp/Cntr=0.3,0.1

Type RM Length L Ch R = 1 ,110093  ,1490,1490,1490
BEGIN DESCRIPTION:
Black River 110.0
END DESCRIPTION:
XS GIS Cut Line= 3
       2402244.1       637812.49      2397637.94       626669.97
      2397177.32       625331.99
#Sta/Elev= 30
   -7065   45.77   -6855   49.23   -6345   36.02   -6025   44.61   -5465   28.75
   -5385   32.79   -4965   29.51   -4745   33.78   -3675   34.79   -2685   24.59
   -2405   29.46   -1675    22.8   -1205    26.4    -535   17.67     525   17.19
     875   21.33    1635   15.19    1865   19.53    1945   15.68  4925.8   12.83
  4926.2    9.83  5074.3   12.83    5252   19.54    5662   19.07    5802   35.55
    5892   36.16    5922    28.8    5992   30.07    6022   38.03  6407.1   40.61
#Mann= 3 ,-1,0
   -7065     .15       0  4925.8     .05       0  5074.3     .15       0
Bank Sta=4925.8,5074.3
XS Rating Curve= 0 ,0
Exp/Cntr=0.3,0.1

Type RM Length L Ch R = 1 ,108603  ,605,605,605
BEGIN DESCRIPTION:
Black River 109.0
END DESCRIPTION:
XS GIS Cut Line= 3
      2403209.17       637702.76      2398471.43       626911.25
      2397681.81       625090.72
#Sta/Elev= 30
 -6769.5   46.75 -5739.5   42.63 -5549.5   39.35 -5429.5   28.73 -5219.5   26.64
 -4839.5   32.83 -3349.5   33.55 -2429.5   23.33 -1949.5   30.48  -799.5   30.68
  -619.5   20.53  -469.5   19.29  1170.5   17.44  1410.5   21.83  1950.5   20.45
  2070.5   15.35  2640.5   18.85  2720.5   14.91  3810.5   13.38  4020.5   18.84
  4100.5   13.74  4925.8   12.94  4926.2    9.94  5074.3   12.94  5966.2    14.6
  6156.2   21.66  6276.2    34.1  6396.2   31.97  6626.2   43.17  7000.6   49.22
#Mann= 3 ,-1,0
 -6769.5     .15       0  4925.8     .05       0  5074.3     .15       0
Bank Sta=4925.8,5074.3
XS Rating Curve= 0 ,0
Exp/Cntr=0.3,0.1

Type RM Length L Ch R = 1 ,107998  ,1673,1673,1673
BEGIN DESCRIPTION:
Black River 108.0
END DESCRIPTION:
XS GIS Cut Line= 3
      2402902.12       635465.55       2398958.7         627043.
      2398164.35       625178.45
#Sta/Elev= 30
   -4300   42.61   -3700   37.99   -3240   28.38   -2510   25.84   -2160   29.89
   -1700   29.51   -1550    33.3    -750   32.58    -580   26.91    -450   18.16
     260   20.35     360   17.37    1020   17.05    1130   20.67    1340   17.28
    1750   17.13    1810   19.91    2120   21.01    2370   15.47    2560   15.38
    3430   21.21    3980   18.48    4030   12.83  4925.8   12.74  4926.2    9.74
  5073.8    9.74  5074.3   12.74    6330   15.28    6610   34.09  7026.7   48.34
#Mann= 3 ,-1,0
   -4300     .15       0  4925.8     .05       0  5074.3     .15       0
Bank Sta=4925.8,5074.3
XS Rating Curve= 0 ,0
Exp/Cntr=0.3,0.1

Type RM Length L Ch R = 1 ,106325  ,998,998,998
BEGIN DESCRIPTION:
Black River 107.0
END DESCRIPTION:
XS GIS Cut Line= 3
      2403450.44       635531.29      2399107.52       626231.29
      2398383.68       624827.48
#Sta/Elev= 30
 -5231.9   44.45 -4361.9   37.58 -4151.9   29.06 -3991.9   27.63 -1311.9   31.63
 -1211.9   29.58 -1101.9   17.78 -1061.9   17.22   758.1      19   858.1   22.19
  1148.1   17.09  1628.1   15.58  1748.1    20.2  1808.1   15.36  2188.1    15.4
  2728.1   20.62  3238.1   13.35  3418.1    17.3  3628.1   16.19  3708.1   20.19
  3778.1   12.91  4925.8   12.33  4926.2    9.33  5073.8    9.33  5074.3   12.33
  5512.2   14.67  5552.2   20.14  6132.2   28.39  6422.2   41.12  6611.6   44.55
#Mann= 3 ,-1,0
 -5231.9     .15       0  4925.8     .05       0  5074.3     .15       0
Bank Sta=4925.8,5074.3
XS Rating Curve= 0 ,0
Exp/Cntr=0.3,0.1

Type RM Length L Ch R = 1 ,105327  ,587,587,587
BEGIN DESCRIPTION:
Black River 106.0
END DESCRIPTION:
XS GIS Cut Line= 3
      2403757.52        635465.5       2399677.8       625748.74
       2399414.6         625003.
#Sta/Elev= 30
 -5578.8   46.33 -3868.8   27.42 -3338.8    28.7 -3108.8   33.16 -2158.8    26.6
 -1758.8   28.94 -1668.8   26.77 -1558.8    17.6 -1478.8   17.07  -128.8   17.29
    91.2   19.96   981.2   18.85  1401.2   15.42  1551.2   19.97  2331.2   19.22
  3071.2   22.72  3721.2   15.76  3861.2   18.31  3991.2   13.27  4181.2   16.69
  4381.2   12.82  4925.7   12.14  4926.1    9.14  5073.9    9.14  5074.3   12.14
  5079.7   32.14  5139.7   37.01  5289.7   39.95  5549.7   37.44  5750.5   41.49
#Mann= 3 ,-1,0
 -5578.8     .15       0  4925.7     .05       0  5074.3     .15       0
Bank Sta=4925.7,5074.3
XS Rating Curve= 0 ,0
Exp/Cntr=0.3,0.1

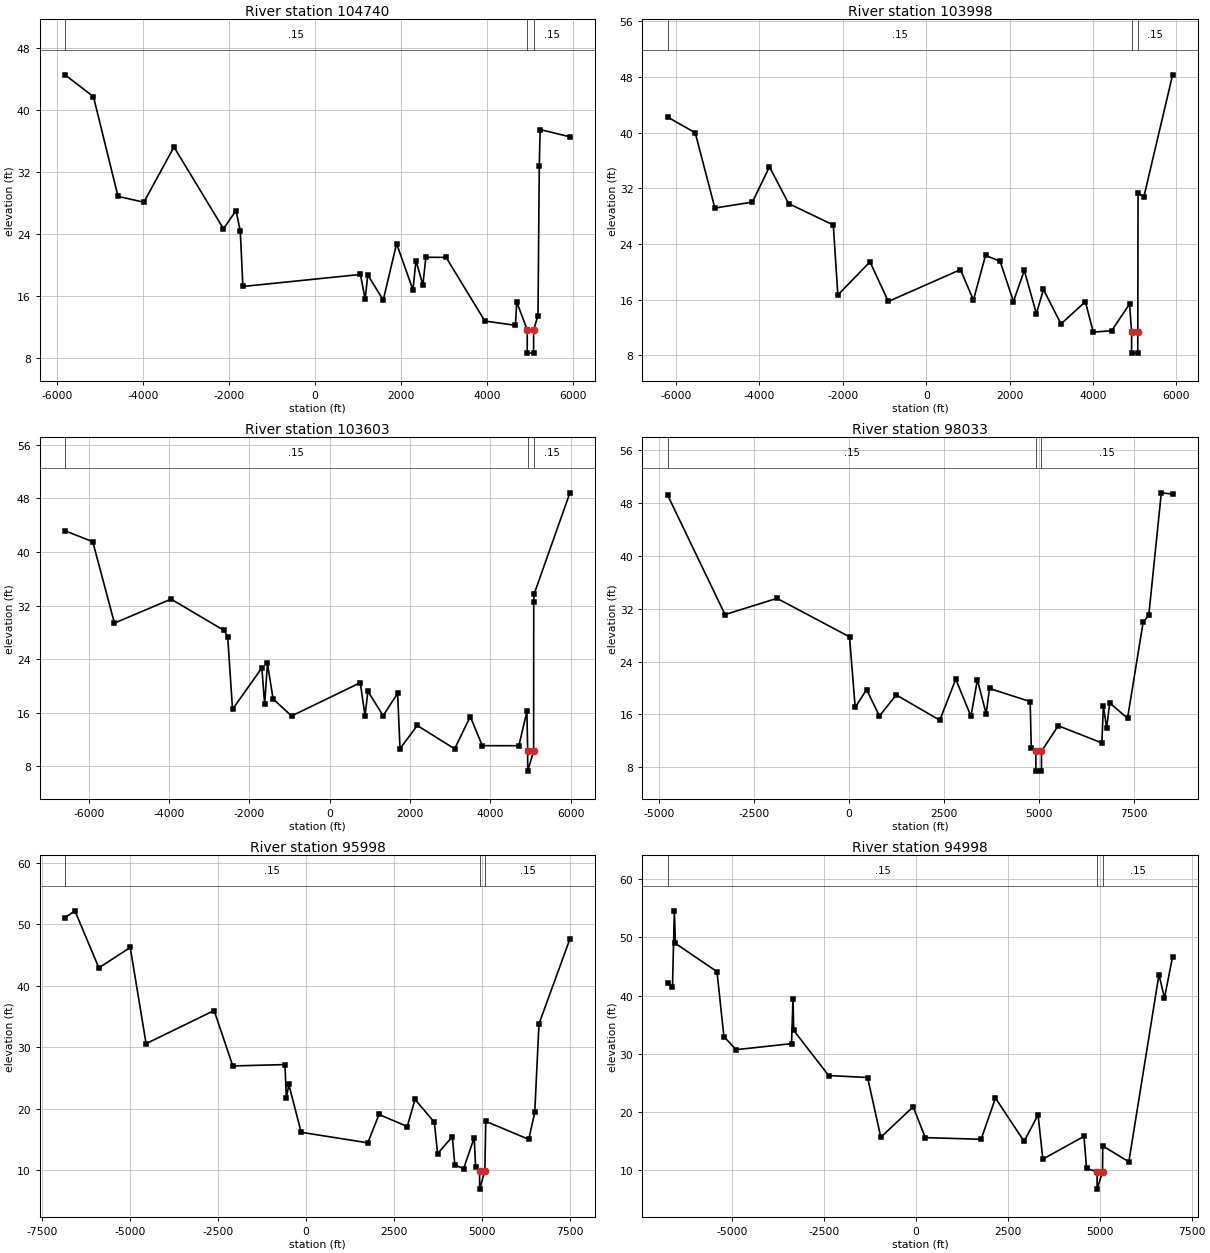
Type RM Length L Ch R = 1 ,104740  ,742,742,742
BEGIN DESCRIPTION:
Black River 105.0
END DESCRIPTION:
XS GIS Cut Line= 3
      2404393.62       635553.26      2400204.22       625573.27
      2399919.09       624717.88
#Sta/Elev= 30
   -5808    44.6   -5148   41.78   -4578   28.92   -3978   28.16   -3278   35.29
   -2128   24.73   -1838   27.09   -1738   24.45   -1678   17.29    1052   18.84
    1162   15.63    1222   18.78    1582   15.54    1892   22.82    2272   16.84
    2342   20.63    2502    17.5    2572   21.06    3042   21.04    3942   12.83
    4652   12.28    4682    15.3  4925.7   11.69  4926.1    8.69  5073.9    8.69
  5074.3   11.69  5175.6   13.54  5205.6    32.8  5225.6   37.54  5917.3    36.6
#Mann= 3 ,-1,0
   -5808     .15       0  4925.7     .05       0  5074.3     .15       0
Bank Sta=4925.7,5074.3
XS Rating Curve= 0 ,0
Exp/Cntr=0.3,0.1

Type RM Length L Ch R = 1 ,103998  ,395,395,395
BEGIN DESCRIPTION:
Black River 104.0
END DESCRIPTION:
XS GIS Cut Line= 4
       2404569.1       635553.28      2401015.78       626319.03
      2400705.06       625053.12      2400357.77        624213.4
#Sta/Elev= 30
 -6197.8   42.22 -5537.8   39.98 -5067.8   29.17 -4167.8   30.02 -3757.8   35.08
 -3297.8    29.8 -2227.8   26.74 -2117.8   16.68 -1347.8   21.44  -907.8   15.75
   822.2   20.32  1132.2   15.95  1422.2   22.36  1772.2   21.53  2092.2   15.74
  2352.2    20.2  2642.2   14.01  2812.2   17.47  3232.2   12.52  3816.5   15.72
  4006.5   11.35  4446.5   11.54  4876.5   15.39  4925.7   11.33  4926.1    8.33
  5073.9    8.33  5074.3   11.33    5080   31.26    5220   30.79  5908.7    48.3
#Mann= 3 ,-1,0
 -6197.8     .15       0  4925.7     .05       0  5074.3     .15       0
Bank Sta=4925.7,5074.3
XS Rating Curve= 0 ,0
Exp/Cntr=0.3,0.1

Type RM Length L Ch R = 1 ,103603  ,5570,5570,5570
BEGIN DESCRIPTION:
Black River 100.0
END DESCRIPTION:
XS GIS Cut Line= 4
      2404766.48       635662.87      2401808.92       626888.13
      2401169.32       626516.43      2401015.78       623950.15
#Sta/Elev= 30
 -6592.4   43.16 -5902.4   41.54 -5362.4   29.39 -3952.4   32.97 -2632.4   28.29
 -2542.4   27.34 -2422.4   16.52 -1692.4   22.71 -1622.4   17.29 -1552.4   23.37
 -1412.4   18.07  -952.4   15.53   757.6   20.49   877.6   15.57   947.6   19.22
  1327.6   15.57  1687.6    18.9  1747.6   10.65  2177.6   14.11  3107.4   10.63
  3497.1   15.43  3797.1    11.1  4707.1   11.09  4907.1   16.21  4925.7    10.3
  4926.1     7.3  5074.3    10.3  5077.1   32.59  5087.1   33.73    5978   48.83
#Mann= 3 ,-1,0
 -6592.4     .15       0  4925.7     .05       0  5074.3     .15       0
Bank Sta=4925.7,5074.3
XS Rating Curve= 0 ,0
Exp/Cntr=0.3,0.1

Type RM Length L Ch R = 1 ,98033   ,2035,2035,2035
BEGIN DESCRIPTION:
Black River 97.0
END DESCRIPTION:
XS GIS Cut Line= 4
      2405868.07       636074.79      2402551.16       626757.71
       2402902.1       625200.39      2402287.95       623489.55
#Sta/Elev= 30
 -4774.7   49.13 -3264.7    31.1 -1894.7   33.55    15.3   27.73   165.3   17.06
   465.3   19.75   805.3   15.76  1245.3   18.95  2395.3   15.12  2815.3   21.33
  3215.3   15.72  3385.3   21.24  3615.3   16.11  3705.3   19.92  4775.3   17.94
  4805.3   10.91  4925.7   10.42  4926.1    7.42  5073.9    7.42  5074.3   10.42
  5515.2   14.28  6665.2   11.69  6705.2   17.27  6791.6   13.92  6871.6   17.73
  7341.6   15.42  7751.6    29.9  7901.6   31.03  8231.6   49.51  8529.3   49.32
#Mann= 3 ,-1,0
 -4774.7     .15       0  4925.7     .05       0  5074.3     .15       0
Bank Sta=4925.7,5074.3
XS Rating Curve= 0 ,0
Exp/Cntr=0.3,0.1

Type RM Length L Ch R = 1 ,95998   ,1000,1000,1000
BEGIN DESCRIPTION:
Black River 96.0
END DESCRIPTION:
XS GIS Cut Line= 3
      2407364.67       636862.51      2403372.88       625717.94
      2402638.62       623340.75
#Sta/Elev= 30
 -6837.9   51.04 -6557.9   52.15 -5877.9   42.88 -4987.9   46.19 -4537.9   30.55
 -2607.9   35.94 -2077.9   26.93  -597.9   27.15  -557.9   21.69  -487.9   23.93
  -137.9   16.14  1752.1   14.43  2072.1   19.04  2872.1   17.08  3092.1   21.49
  3642.1   17.77  3732.1   12.67  4152.1   15.42  4222.1   10.82  4472.1   10.23
  4772.1   15.27  4812.1   10.54  4925.7     9.9  4926.1     6.9  5074.3     9.9
    5100   17.93    6320   14.99    6490   19.39    6610   33.76    7488   47.58
#Mann= 3 ,-1,0
 -6837.9     .15       0  4925.7     .05       0  5074.3     .15       0
Bank Sta=4925.7,5074.3
XS Rating Curve= 0 ,0
Exp/Cntr=0.3,0.1

Type RM Length L Ch R = 1 ,94998   ,1000,1000,1000
BEGIN DESCRIPTION:
Black River 95.0
END DESCRIPTION:
XS GIS Cut Line= 3
      2407784.76       636074.83      2403998.48       624940.39
      2403321.27       623078.21
#Sta/Elev= 30
 -6760.6   42.07 -6630.6   41.52 -6580.6   54.58 -6550.6   48.97 -5420.6   44.11
 -5230.6   32.92 -4900.6   30.67 -3390.6   31.71 -3350.6    39.4 -3330.6   33.99
 -2380.6   26.22 -1320.6   25.88  -960.6   15.59   -80.6   20.84   249.4   15.53
  1769.4   15.24  2159.4   22.35  2939.4   14.88  3319.4   19.45  3449.4   11.83
  4569.4   15.74  4639.4   10.22  4925.7    9.66  4926.1    6.66  5074.3    9.66
    5080    14.1    5790   11.36    6610   43.58    6760   39.58  6981.5   46.69
#Mann= 3 ,-1,0
 -6760.6     .15       0  4925.7     .05       0  5074.3     .15       0
Bank Sta=4925.7,5074.3
XS Rating Curve= 0 ,0
Exp/Cntr=0.3,0.1