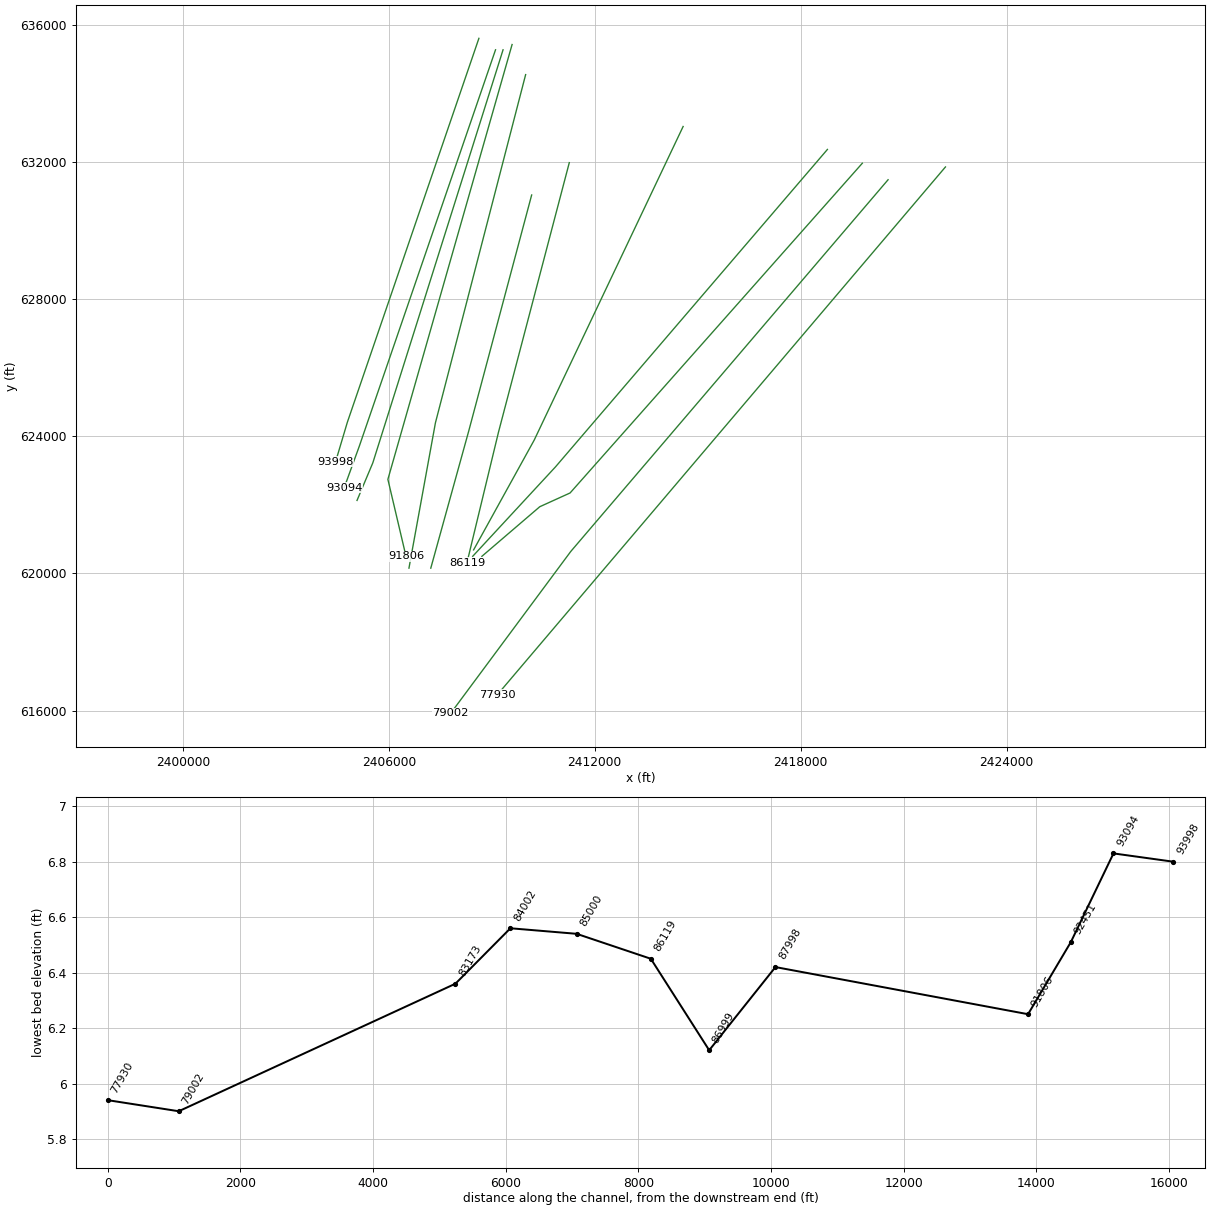
HEC-RAS study BlackRiver.prj: S-45-30 over Black River

--- BlackRiver.g02 (geometry) --- (continued)

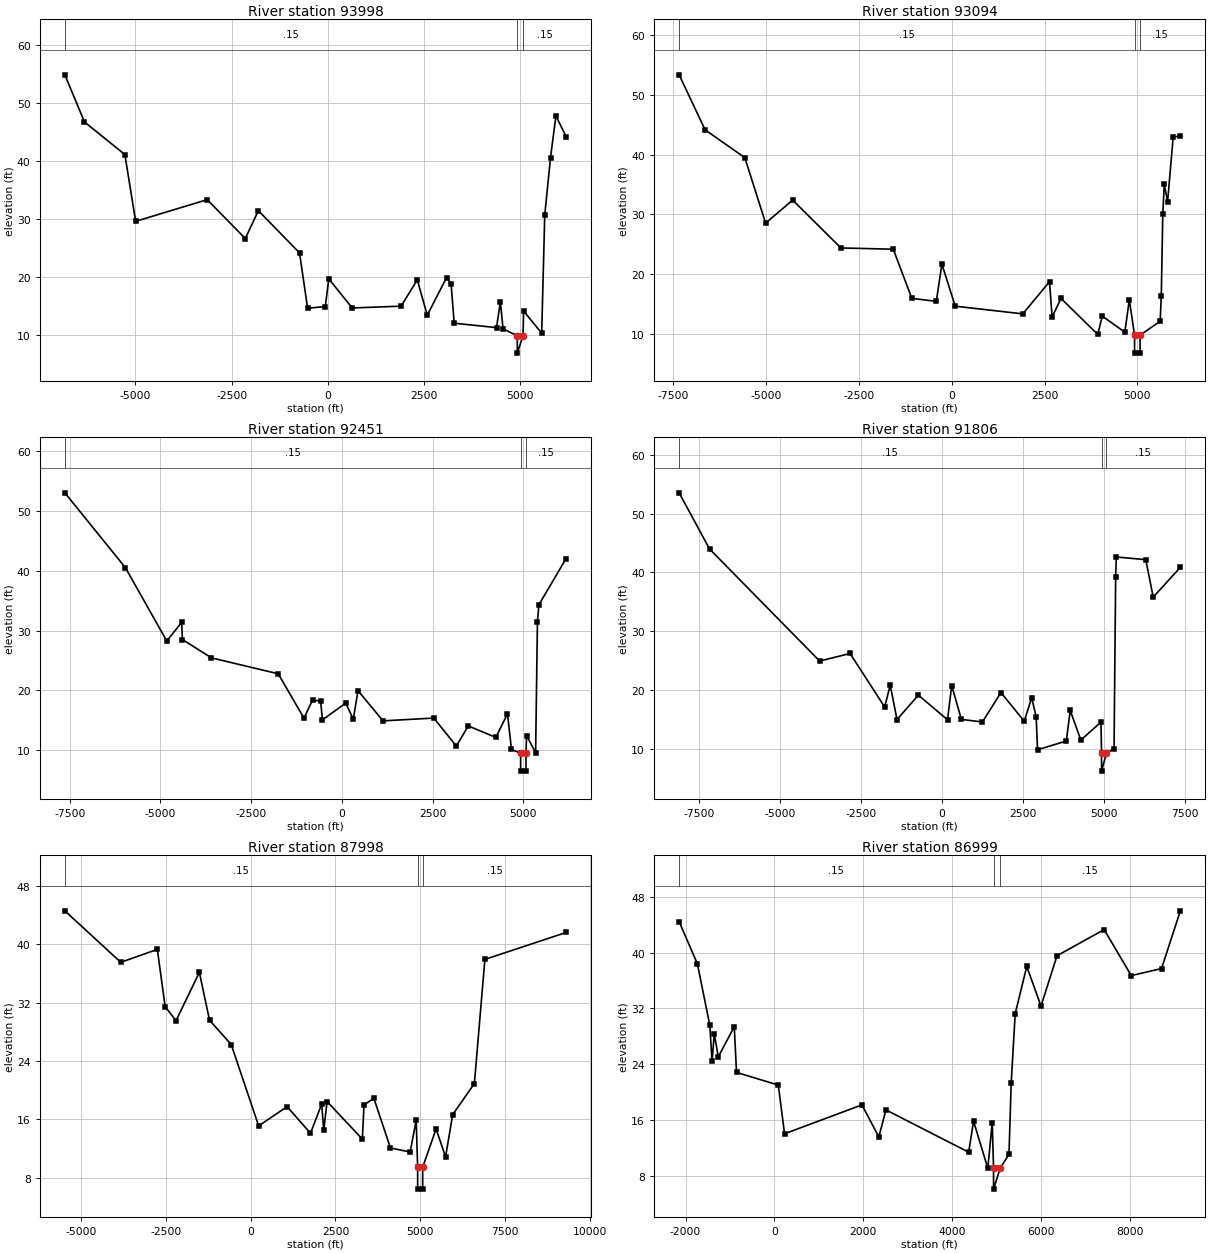
Type RM Length L Ch R = 1 ,93998   ,904,904,904
BEGIN DESCRIPTION:
Black River 94.0
END DESCRIPTION:
XS GIS Cut Line= 3
      2408624.93       635602.18      2404791.01       624406.33
      2404450.27       623261.98
#Sta/Elev= 30
 -6834.1    54.8 -6324.1   46.67 -5274.1   41.05 -4994.1   29.53 -3134.1   33.27
 -2144.1   26.57 -1804.1   31.37  -734.1   24.09  -524.1   14.54   -64.1   14.84
    25.9   19.61   635.9   14.59  1905.9    14.9  2325.9   19.44  2585.9   13.34
  3085.9   19.81  3205.9   18.72  3285.9   11.96  4385.9    11.2  4485.9   15.65
  4555.9   10.98  4925.7     9.8  4926.1     6.8  5074.3     9.8    5090   14.07
    5560   10.24    5640   30.67    5790   40.52    5930   47.72    6194   44.15
#Mann= 3 ,-1,0
 -6834.1     .15       0  4925.7     .05       0  5074.3     .15       0
Bank Sta=4925.7,5074.3
XS Rating Curve= 0 ,0
Exp/Cntr=0.3,0.1

Type RM Length L Ch R = 1 ,93094   ,643,643,643
BEGIN DESCRIPTION:
Black River 93.0
END DESCRIPTION:
XS GIS Cut Line= 3
      2409109.42        635268.1      2405139.37       623708.88
       2404700.7       622502.54
#Sta/Elev= 30
 -7345.9   53.32 -6645.9   44.13 -5575.9   39.48 -5015.9   28.55 -4285.9   32.39
 -2985.9    24.4 -1575.9   24.19 -1075.9   15.98  -415.9   15.48  -265.9    21.7
    94.1   14.67  1914.1   13.39  2634.1   18.76  2704.1   12.88  2944.1   15.97
  3934.1    9.95  4054.1   13.02  4664.1   10.33  4784.1   15.73  4925.7    9.83
  4926.1    6.83  5073.9    6.83  5074.3    9.83  5616.1   12.15  5646.1   16.41
  5686.1   30.05  5726.1   35.01  5816.1   32.14  5966.1   42.95  6159.7   43.08
#Mann= 3 ,-1,0
 -7345.9     .15       0  4925.7     .05       0  5074.3     .15       0
Bank Sta=4925.7,5074.3
XS Rating Curve= 0 ,0
Exp/Cntr=0.3,0.1

Type RM Length L Ch R = 1 ,92451   ,645,645,645
BEGIN DESCRIPTION:
Black River 92.0
END DESCRIPTION:
XS GIS Cut Line= 3
      2409328.77        635268.1      2405534.18       623226.33
      2405073.57       622129.63
#Sta/Elev= 30
 -7636.2   53.07 -5966.2   40.54 -4826.2   28.27 -4416.2   31.41 -4396.2   28.53
 -3596.2   25.46 -1756.2    22.8 -1046.2   15.38  -806.2   18.43  -586.2    18.2
  -536.2   15.08   103.8   17.89   313.8   15.21   443.8   19.97  1133.8   14.92
  2533.8   15.39  3153.8    10.7  3483.8   14.07  4243.8   12.15  4563.8   16.11
  4673.8   10.14  4925.7    9.51  4926.1    6.51  5073.9    6.51  5074.3    9.51
  5089.3   12.47  5339.3     9.6  5389.3    31.5  5429.3   34.34  6178.8   42.07
#Mann= 3 ,-1,0
 -7636.2     .15       0  4925.7     .05       0  5074.3     .15       0
Bank Sta=4925.7,5074.3
XS Rating Curve= 0 ,0
Exp/Cntr=0.3,0.1

Type RM Length L Ch R = 1 ,91806   ,3808,3808,3808
BEGIN DESCRIPTION:
Black River 91.0
END DESCRIPTION:
XS GIS Cut Line= 3
      2409591.97       635421.63      2405972.86       622743.79
      2406499.29       620506.48
#Sta/Elev= 30
   -8123   53.52   -7183   43.98   -3783   24.95   -2843   26.23   -1773   17.14
   -1603   20.87   -1393   15.01    -733   19.16     167   14.97     297   20.78
     597   15.03    1247    14.6    1817    19.6    2537   14.73    2767   18.71
    2907   15.46    2947    9.88    3837   11.36    3957   16.55    4287   11.53
    4907   14.57  4925.6    9.25    4926    6.25  5074.4    9.25  5311.3   10.08
  5361.3   39.16  5381.3   42.62  6291.3   42.17  6521.3    35.8  7359.7   40.87
#Mann= 3 ,-1,0
   -8123     .15       0  4925.6     .05       0  5074.4     .15       0
Bank Sta=4925.6,5074.4
XS Rating Curve= 0 ,0
Exp/Cntr=0.3,0.1

Type RM Length L Ch R = 1 ,87998   ,999,999,999
BEGIN DESCRIPTION:
Black River 88.0
END DESCRIPTION:
XS GIS Cut Line= 3
      2409986.78       634544.28      2407358.19       624392.47
      2406587.01       620155.58
#Sta/Elev= 30
 -5486.6   44.58 -3836.6   37.52 -2756.6   39.29 -2526.6   31.45 -2206.6   29.51
 -1516.6   36.14 -1216.6   29.58  -576.6   26.25   233.4   15.09  1073.4   17.73
  1763.4   14.08  2093.4   18.09  2153.4   14.49  2253.4   18.43  3293.4   13.28
  3343.4   17.97  3633.4   18.88  4123.4   12.06  4703.4   11.51  4883.4   15.85
  4925.6    9.42    4926    6.42    5074    6.42  5074.4    9.42    5470   14.67
    5750   10.84    5960   16.64    6600   20.89    6910   37.92  9306.5   41.61
#Mann= 3 ,-1,0
 -5486.6     .15       0  4925.6     .05       0  5074.4     .15       0
Bank Sta=4925.6,5074.4
XS Rating Curve= 0 ,0
Exp/Cntr=0.3,0.1

Type RM Length L Ch R = 1 ,86999   ,880,880,880
BEGIN DESCRIPTION:
Black River 87.0
END DESCRIPTION:
XS GIS Cut Line= 3
      2410162.24       631034.79      2408327.35       624148.72
      2407223.09       620155.54
#Sta/Elev= 30
 -2143.7   44.44 -1733.7   38.41 -1453.7   29.58 -1403.7   24.41 -1353.7   28.37
 -1263.7   25.07  -903.7   29.39  -853.7   22.84    86.3   21.03   226.3   14.05
  1966.3   18.19  2346.3    13.6  2506.3   17.47  4366.3   11.41  4476.3   15.85
  4796.3    9.12  4896.3   15.66  4925.6    9.12    4926    6.12  5074.4    9.12
  5272.6    11.1  5322.6   21.36  5412.6   31.27  5672.6   38.02  5992.6   32.34
  6352.6   39.56  7412.6    43.3  8022.6   36.71  8702.6   37.72  9125.7   45.99
#Mann= 3 ,-1,0
 -2143.7     .15       0  4925.6     .05       0  5074.4     .15       0
Bank Sta=4925.6,5074.4
XS Rating Curve= 0 ,0
Exp/Cntr=0.3,0.1

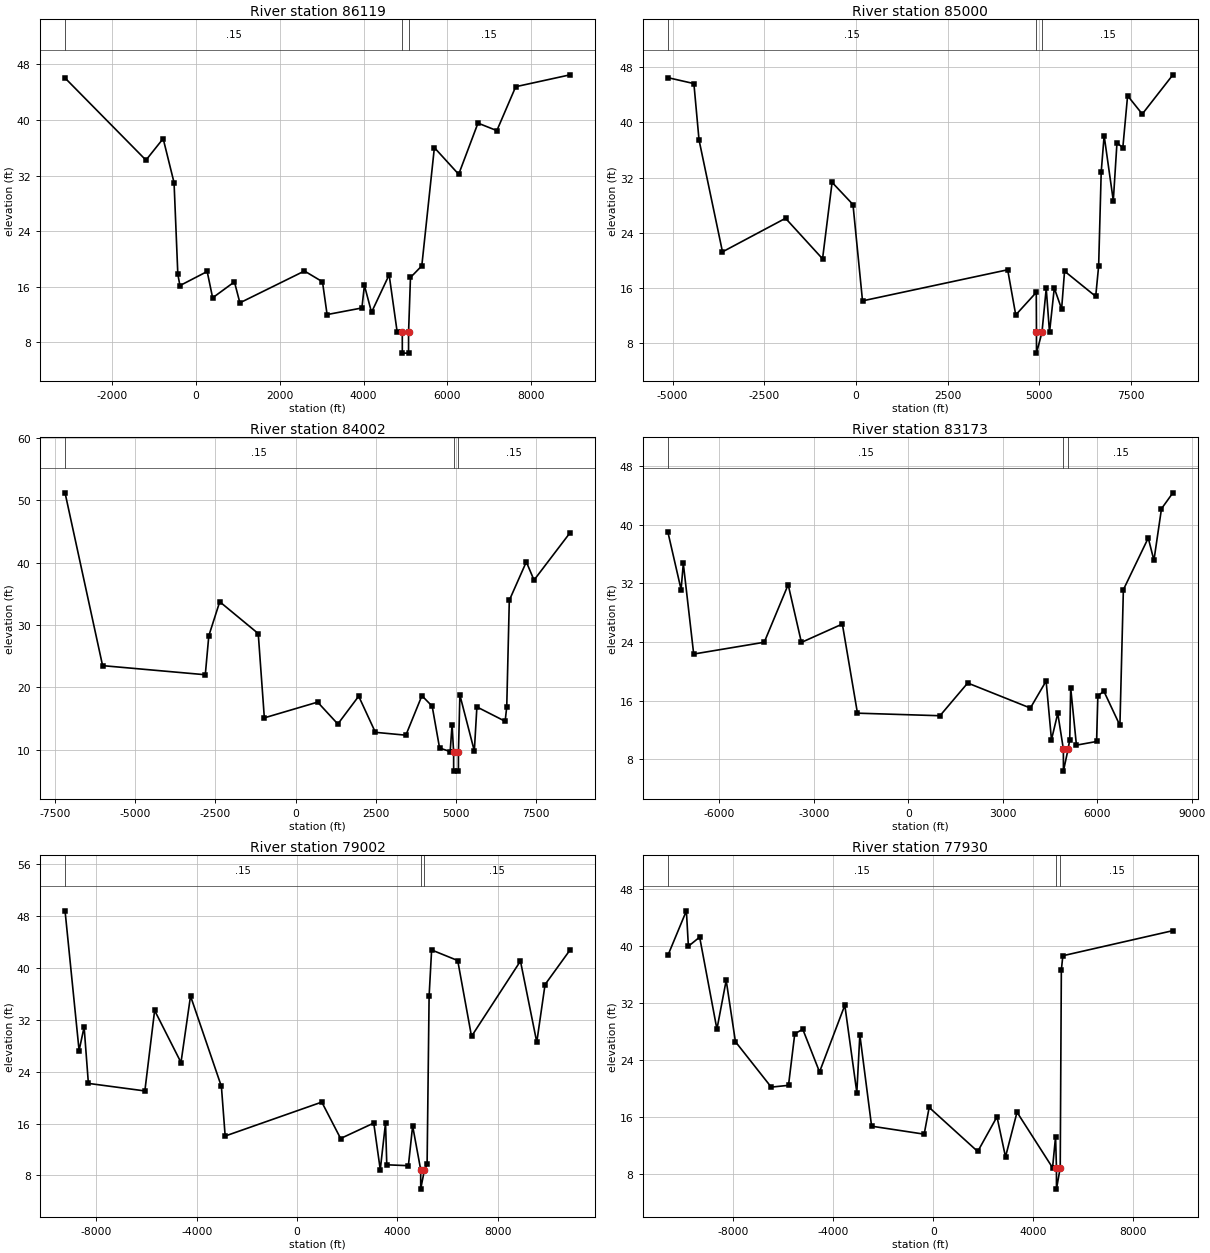
Type RM Length L Ch R = 1 ,86119   ,1119,1119,1119
BEGIN DESCRIPTION:
Black River 86.0
END DESCRIPTION:
XS GIS Cut Line= 3
      2411258.96       631978.01      2409197.16       624125.63
      2408275.93        620309.1
#Sta/Elev= 30
 -3118.4   46.05 -1188.4   34.23  -778.4   37.33  -518.4   30.99  -428.4   17.81
  -378.4   16.17   271.6    18.2   401.6   14.41   921.6   16.71  1051.6   13.69
  2591.6   18.27  3021.6   16.72  3131.6      12  3961.6   12.95  4021.6    16.2
  4191.6   12.33  4611.6   17.72  4801.6    9.55  4925.2    9.45  4925.7    6.45
  5074.3    6.45  5074.8    9.45  5120.2   17.34  5390.2   19.01  5690.2   36.03
  6270.2   32.19  6730.2   39.56  7180.2   38.48  7630.2    44.8  8926.3   46.51
#Mann= 3 ,-1,0
 -3118.4     .15       0  4925.2     .05       0  5074.8     .15       0
Bank Sta=4925.2,5074.8
XS Rating Curve= 0 ,0
Exp/Cntr=0.3,0.1

Type RM Length L Ch R = 1 ,85000   ,998,998,998
BEGIN DESCRIPTION:
Black River 85.0
END DESCRIPTION:
XS GIS Cut Line= 3
      2414576.01       633032.23       2410236.2       623888.38
      2408470.64        620687.6
#Sta/Elev= 30
 -5130.2    46.5 -4420.2   45.64 -4280.2   37.47 -3640.2   21.23 -1920.2    26.1
  -910.2   20.22  -650.2   31.31   -80.2   28.09   179.8   14.12  4139.8   18.63
  4359.8   12.08  4919.8   15.35  4925.2    9.54  4925.7    6.54  5074.8    9.54
  5191.3   15.92  5281.3    9.54  5411.3   15.98  5611.3   12.94  5691.3   18.43
  6541.3   14.77  6621.3   19.17  6691.3   32.81  6771.3   38.09  7021.3   28.65
  7121.3   37.04  7281.3   36.34  7411.3   43.88  7811.3   41.22  8646.7   46.91
#Mann= 3 ,-1,0
 -5130.2     .15       0  4925.2     .05       0  5074.8     .15       0
Bank Sta=4925.2,5074.8
XS Rating Curve= 0 ,0
Exp/Cntr=0.3,0.1

Type RM Length L Ch R = 1 ,84002   ,829,829,829
BEGIN DESCRIPTION:
Black River 84.0
END DESCRIPTION:
XS GIS Cut Line= 3
      2418780.14       632362.76      2410856.66       623108.09
      2408443.85       620500.13
#Sta/Elev= 30
 -7183.2   51.17 -6013.2   23.47 -2813.2   22.01 -2703.2   28.26 -2363.2   33.71
 -1163.2   28.61  -973.2    15.1   686.8   17.62  1316.8   14.11  1966.8   18.57
  2486.8   12.78  3436.8   12.32  3936.8   18.65  4256.8   16.96  4486.8   10.27
  4816.8    9.69  4876.8   13.98  4925.2    9.56  4925.7    6.56  5074.3    6.56
  5074.8    9.56    5120   18.75    5570    9.79    5650   16.85    6530   14.55
    6580   16.86    6660   33.94    7190    40.1    7430   37.18  8552.9   44.77
#Mann= 3 ,-1,0
 -7183.2     .15       0  4925.2     .05       0  5074.8     .15       0
Bank Sta=4925.2,5074.8
XS Rating Curve= 0 ,0
Exp/Cntr=0.3,0.1

Type RM Length L Ch R = 1 ,83173   ,4171,4171,4171
BEGIN DESCRIPTION:
Black River 83.0
END DESCRIPTION:
XS GIS Cut Line= 4
      2419797.74       631961.14      2411282.32       622347.82
      2410398.65       621946.15      2408711.67       620500.17
#Sta/Elev= 30
 -7633.1   39.04 -7213.1   31.17 -7143.1   34.74 -6813.1   22.36 -4573.1   23.97
 -3813.1   31.84 -3393.1   23.95 -2093.1   26.46 -1613.1   14.28  1006.9   13.93
  1886.9    18.4  3876.9   14.98  4376.9   18.67  4546.9   10.65  4746.9   14.26
  4925.2    9.36  4925.7    6.36  5074.8    9.36  5126.9   10.66  5156.9   17.75
  5339.3    9.91  5979.3   10.41  6019.3   16.63    6210   17.29    6720   12.61
    6830   31.15    7620   38.22    7800   35.16    8040   42.22  8401.9   44.39
#Mann= 3 ,-1,0
 -7633.1     .15       0  4925.2     .05       0  5074.8     .15       0
Bank Sta=4925.2,5074.8
XS Rating Curve= 0 ,0
Exp/Cntr=0.3,0.1

Type RM Length L Ch R = 1 ,79002   ,1072,1072,1072
BEGIN DESCRIPTION:
Black River 79.0
END DESCRIPTION:
XS GIS Cut Line= 3
      2420547.47       631479.07      2411301.24       620641.36
       2407801.2       615921.13
#Sta/Elev= 30
   -9246   48.78   -8686   27.25   -8486   30.88   -8316   22.19   -6066   21.03
   -5676   33.43   -4626   25.41   -4246   35.65   -3016   21.72   -2866   14.08
     984   19.31    1734    13.7    3054   16.08    3314     8.9    3524   16.09
    3574    9.65    4434    9.51    4604   15.64  4924.6     8.9  4925.1     5.9
  5075.4     8.9    5180    9.73    5260   35.63    5360   42.75    6400   41.12
    6950   29.44    8900   41.04    9550   28.54    9880   37.42 10876.3   42.75
#Mann= 3 ,-1,0
   -9246     .15       0  4924.6     .05       0  5075.4     .15       0
Bank Sta=4924.6,5075.4
XS Rating Curve= 0 ,0
Exp/Cntr=0.3,0.1

Type RM Length L Ch R = 1 ,77930   ,0,0,0
BEGIN DESCRIPTION:
Black River 78.0
END DESCRIPTION:
XS GIS Cut Line= 3
       2422219.5       631852.47      2412125.65       619957.09
      2409164.65        616467.6
#Sta/Elev= 30
-10600.8   38.72 -9860.8   44.98 -9780.8   40.01 -9330.8   41.29 -8640.8   28.38
 -8270.8   35.23 -7900.8   26.62 -6470.8   20.25 -5780.8    20.5 -5530.8   27.73
 -5210.8   28.37 -4540.8   22.38 -3530.8   31.74 -3050.8   19.49 -2930.8   27.59
 -2460.8   14.77  -360.8   13.65  -160.8    17.4  1779.2   11.22  2549.2   16.09
  2889.2   10.46  3349.2   16.73  4769.2    8.94  4889.2    13.3  4924.6    8.94
  4925.1    5.94  5075.4    8.94    5120   36.67    5180   38.68  9576.5    42.2
#Mann= 3 ,-1,0
-10600.8     .15       0  4924.6     .05       0  5075.4     .15       0
Bank Sta=4924.6,5075.4
XS Rating Curve= 0 ,0
Exp/Cntr=0.3,0.1
LCMann Table=0

--- BlackRiver.g05 (geometry) ---

Geom Title=Existing
Program Version=6.60

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
River Reach=Black River     ,Reach-1

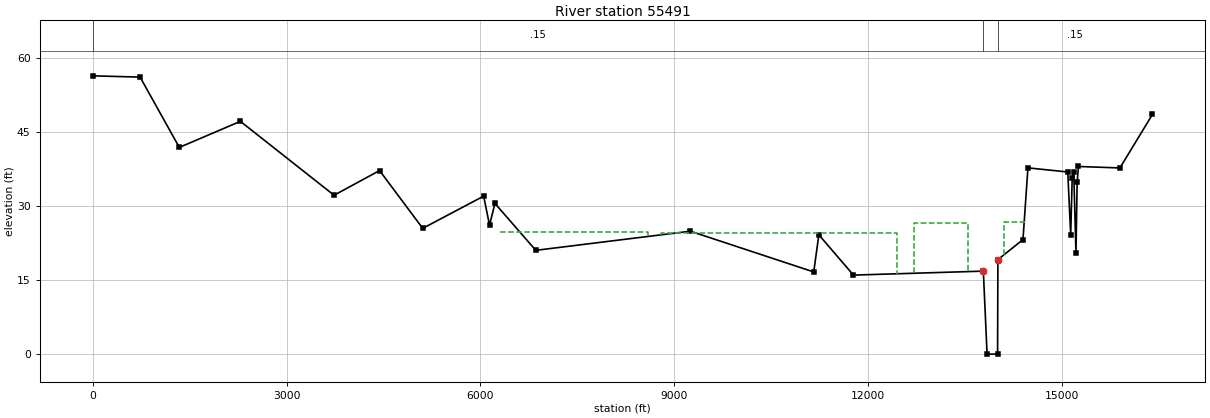
Type RM Length L Ch R = 1 ,55491   ,200.8,200.8,200.8
BEGIN DESCRIPTION:
Black River 118.0
END DESCRIPTION:
XS GIS Cut Line= 6
2393432.63647658642101.5866659632392829.92725322639252.634513813
2391255.92538498636193.9854142632392147.82003084 632121.22054437
2393705.31246644628597.7499796052393304.95174855626641.986105873
#Sta/Elev= 30
       0   56.43   732.7   56.17  1339.8    41.9  2285.4   47.19  3735.4   32.19
  4440.1    37.2    5108   25.47  6051.6   32.01  6142.4   26.12    6226   30.53
  6858.8   21.01  9251.8   24.89 11161.5   16.62 11240.6   24.16 11776.4   15.98
 13787.116.7875313845.22    -.0614007.88    -.06 14012.6   19.12 14400.8   23.18
 14477.7   37.75   15094   36.91 15139.9   24.16   15163   35.75 15186.5   36.96
 15221.3   20.42 15239.6   34.88 15260.2   38.03 15901.6   37.73 16405.1   48.59
#Mann= 3 ,0,0
       0     .15       0 13787.1     .05       0 14012.6     .15       0
#XS Ineff= 4 ,-1
    6310    8590   24.82    8800   12447   24.49   12717   13545   26.59
   14100   14448   26.76
Permanent Ineff=
       F       F       F       F
Bank Sta=13787.1,14012.6
XS Rating Curve= 0 ,0
Exp/Cntr=0.5,0.3