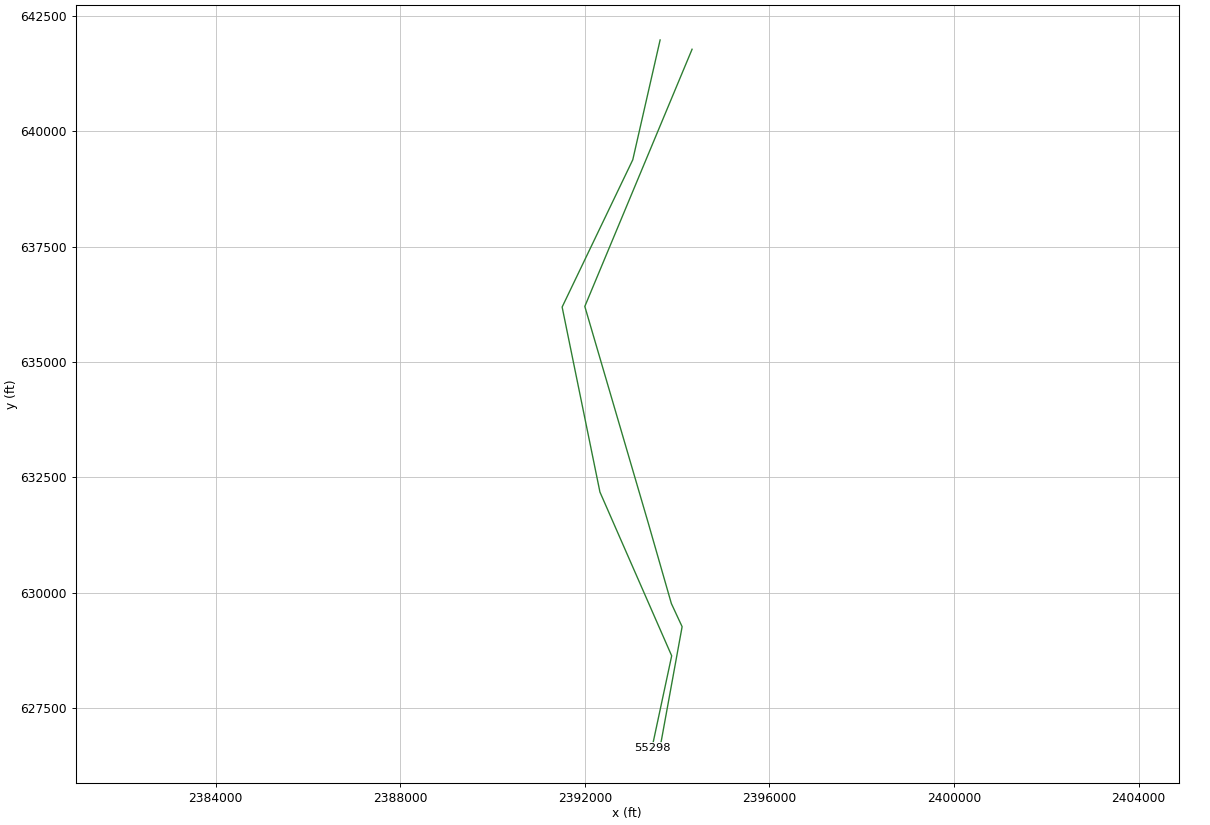
HEC-RAS study BlackRiver.prj: S-45-30 over Black River

--- BlackRiver.g05 (geometry) --- (continued)

Type RM Length L Ch R = 4 ,55421   ,,,
Node Name=Bridge S-45-30
Bridge Culvert-0,0,0,0, 0
Deck Dist Width WeirC Skew NumUp NumDn MinLoCord MaxHiCord MaxSubmerge Is_Ogee
65,27.5,2.6,0, 60, 60, , , 0.98, 0, 2,2,,
       0   375.1   459.1   627.2   822.2     839  1044.1  1344.2  1555.1  1709.7
  1928.2  2234.2  2328.3  2570.3    2931  3091.5  3109.9  3354.2  3671.1  3689.4
  3884.9    3991  4164.6  4279.7  4537.6  4729.6  5091.6  5357.5    5430    5627
    5821    6140    6260    6628    7094    7854    8347    8650    8650    8740
    8740    9651   11982   12507   12507   12657   12657   13605   13605   14040
   14040   14352   14532   14853   15176 15443.8 15531.2 15655.4 15805.9 16312.9
   56.41   56.65   56.46   55.12    52.5   51.82   48.17   45.04   44.17   45.13
   44.46   45.27      45   43.28   39.31   38.43   37.96   38.15   35.61   35.87
   34.89   34.75   35.65   35.31   33.37   31.31   28.92   29.81   31.05   31.35
   29.89   25.42    26.4   26.69   25.11   24.82    26.6    26.8  29.383  29.383
    26.8   24.49      25   26.61  29.193  29.223   26.64   26.63  29.213  29.213
   26.63   27.61   28.97   32.53   36.91   38.81   40.04   40.62   42.63   47.82
                                                                                
                                                                                
                                                                                
                                                                   24.91   24.91
                                   24.91   24.91                   25.76   25.76
                                                                                
       0   375.1   627.2   822.2     839  1044.1  1344.2  1555.1  1709.7  1928.2
  2234.2  2328.3  2570.3    2931  3091.5  3109.9  3354.2  3671.1  3689.4  3884.9
    3991  4164.6  4279.7  4537.6  4729.6  5091.6  5357.5    5430    5627    5821
    6140    6260    6628    7094    7854    8347    8610    8610    8700    8700
    9651   11982   12184   12333   12333   12483   12483   13310   13310   13745
   13745   14219   14532   14853   15176 15443.8 15531.2 15655.4 15805.9 16312.9
   56.41   56.65   55.12    52.5   51.82   48.17   45.04   44.17   45.13   44.46
   45.27      45   43.28   39.31   38.43   37.96   38.15   35.61   35.87   34.89
   34.75   35.65   35.31   33.37   31.31   28.92   29.81   31.05   31.35   29.89
   25.42    26.4   26.69   25.11   24.82    26.6    26.8  29.383  29.383    26.8
   24.49      25   25.44   26.61  29.193  29.223   26.64   26.63  29.213  29.213
   26.63   27.02   28.97   32.53   36.91   38.81   40.04   40.62   42.63   47.82
                                                                                
                                                                                
                                                                                
                                                           24.91   24.91
                                   24.91   24.91                   25.76   25.76
                                                                                
Pier Skew, UpSta & Num, DnSta & Num=  ,8680, 2 ,8640, 2 , 0 , 0 , 0 ,,
     1.5     1.5
       0   24.91
     1.5     1.5
       0   24.91
Pier Skew, UpSta & Num, DnSta & Num=  ,8710, 2 ,8670, 2 , 0 , 0 , 0 ,,
     1.5     1.5
       0   24.91
     1.5     1.5
       0   24.91
Pier Skew, UpSta & Num, DnSta & Num=  ,12537, 2 ,12363, 2 , 0 , 0 , 0 ,,
     1.5     1.5
       0   24.91
     1.5     1.5
       0   24.91
Pier Skew, UpSta & Num, DnSta & Num=  ,12567, 2 ,12393, 2 , 0 , 0 , 0 ,,
     1.5     1.5
       0   24.91
     1.5     1.5
       0   24.91
Pier Skew, UpSta & Num, DnSta & Num=  ,12597, 2 ,12423, 2 , 0 , 0 , 0 ,,
     1.5     1.5
       0   24.91
     1.5     1.5
       0   24.91
Pier Skew, UpSta & Num, DnSta & Num=  ,12627, 2 ,12453, 2 , 0 , 0 , 0 ,,
     1.5     1.5
       0   24.91
     1.5     1.5
       0   24.91
Pier Skew, UpSta & Num, DnSta & Num=  ,13620, 2 ,13325, 2 , 0 , 0 , 0 ,,
     7.5     7.5
      -1    27.2
     7.5     7.5
      -1    27.2
Pier Skew, UpSta & Num, DnSta & Num=  ,13635, 2 ,13340, 2 , 0 , 0 , 0 ,,
     7.5     7.5
      -1    27.2
     7.5     7.5
      -1    27.2
Pier Skew, UpSta & Num, DnSta & Num=  ,13650, 2 ,13355, 2 , 0 , 0 , 0 ,,
     7.5     7.5
      -1    27.2
     7.5     7.5
      -1    27.2
Pier Skew, UpSta & Num, DnSta & Num=  ,13665, 2 ,13370, 2 , 0 , 0 , 0 ,,
     7.5     7.5
      -1    27.2
     7.5     7.5
      -1    27.2
Pier Skew, UpSta & Num, DnSta & Num=  ,13680, 2 ,13385, 2 , 0 , 0 , 0 ,,
     7.5     7.5
      -1    27.2
     7.5     7.5
      -1    27.2
Pier Skew, UpSta & Num, DnSta & Num=  ,13695, 2 ,13400, 2 , 0 , 0 , 0 ,,
     7.5     7.5
      -1    27.2
     7.5     7.5
      -1    27.2
Pier Skew, UpSta & Num, DnSta & Num=  ,13710, 2 ,13415, 2 , 0 , 0 , 0 ,,
     7.5     7.5
      -1    27.2
     7.5     7.5
      -1    27.2
Pier Skew, UpSta & Num, DnSta & Num=  ,13725, 2 ,13430, 2 , 0 , 0 , 0 ,,
     7.5     7.5
      -1    27.2
     7.5     7.5
      -1    27.2
Pier Skew, UpSta & Num, DnSta & Num=  ,13740, 2 ,13445, 2 , 0 , 0 , 0 ,,
     7.5     7.5
      -1    27.2
     7.5     7.5
      -1    27.2
Pier Skew, UpSta & Num, DnSta & Num=  ,13755, 2 ,13460, 2 , 0 , 0 , 0 ,,
     7.5     7.5
      -1    27.2
     7.5     7.5
      -1    27.2
Pier Skew, UpSta & Num, DnSta & Num=  ,13770, 2 ,13475, 2 , 0 , 0 , 0 ,,
     7.5     7.5
      -1    27.2
     7.5     7.5
      -1    27.2
Pier Skew, UpSta & Num, DnSta & Num=  ,13785, 2 ,13490, 2 , 0 , 0 , 0 ,,
     7.5     7.5
      -1    27.2
     7.5     7.5
      -1    27.2
Pier Skew, UpSta & Num, DnSta & Num=  ,13800, 2 ,13505, 2 , 0 , 0 , 0 ,,
     7.5     7.5
      -1    27.2
     7.5     7.5
      -1    27.2
Pier Skew, UpSta & Num, DnSta & Num=  ,13815, 2 ,13520, 2 , 0 , 0 , 0 ,,
     7.5     7.5
      -1    27.2
     7.5     7.5
      -1    27.2
Pier Skew, UpSta & Num, DnSta & Num=  ,13830, 2 ,13535, 2 , 0 , 0 , 0 ,,
     7.5     7.5
      -1    27.2
     7.5     7.5
      -1    27.2
Pier Skew, UpSta & Num, DnSta & Num=  ,13845, 2 ,13550, 2 , 0 , 0 , 0 ,,
     7.5     7.5
      -1    27.2
     7.5     7.5
      -1    27.2
Pier Skew, UpSta & Num, DnSta & Num=  ,13860, 2 ,13565, 2 , 0 , 0 , 0 ,,
     7.5     7.5
      -1    27.2
     7.5     7.5
      -1    27.2
Pier Skew, UpSta & Num, DnSta & Num=  ,13875, 2 ,13580, 2 , 0 , 0 , 0 ,,
     7.5     7.5
      -1    27.2
     7.5     7.5
      -1    27.2
Pier Skew, UpSta & Num, DnSta & Num=  ,13890, 2 ,13595, 2 , 0 , 0 , 0 ,,
     7.5     7.5
      -1    27.2
     7.5     7.5
      -1    27.2
Pier Skew, UpSta & Num, DnSta & Num=  ,13905, 2 ,13610, 2 , 0 , 0 , 0 ,,
     7.5     7.5
      -1    27.2
     7.5     7.5
      -1    27.2
Pier Skew, UpSta & Num, DnSta & Num=  ,13920, 2 ,13625, 2 , 0 , 0 , 0 ,,
     7.5     7.5
      -1    27.2
     7.5     7.5
      -1    27.2
Pier Skew, UpSta & Num, DnSta & Num=  ,13935, 2 ,13640, 2 , 0 , 0 , 0 ,,
     7.5     7.5
      -1    27.2
     7.5     7.5
      -1    27.2
Pier Skew, UpSta & Num, DnSta & Num=  ,13950, 2 ,13655, 2 , 0 , 0 , 0 ,,
     7.5     7.5
      -1    27.2
     7.5     7.5
      -1    27.2
Pier Skew, UpSta & Num, DnSta & Num=  ,13965, 2 ,13670, 2 , 0 , 0 , 0 ,,
     7.5     7.5
      -1    27.2
     7.5     7.5
      -1    27.2
Pier Skew, UpSta & Num, DnSta & Num=  ,13980, 2 ,13685, 2 , 0 , 0 , 0 ,,
     7.5     7.5
      -1    27.2
     7.5     7.5
      -1    27.2
Pier Skew, UpSta & Num, DnSta & Num=  ,13995, 2 ,13700, 2 , 0 , 0 , 0 ,,
     7.5     7.5
      -1    27.2
     7.5     7.5
      -1    27.2
Pier Skew, UpSta & Num, DnSta & Num=  ,14010, 2 ,13715, 2 , 0 , 0 , 0 ,,
     7.5     7.5
      -1    27.2
     7.5     7.5
      -1    27.2
Pier Skew, UpSta & Num, DnSta & Num=  ,14025, 2 ,13730, 2 , 0 , 0 , 0 ,,
     7.5     7.5
      -1    27.2
     7.5     7.5
      -1    27.2
Abutment Skew #Up #Dn= , 2 , 2
    8650    8700
   24.91    -.09
    8610    8660
   24.91    -.09
Abutment Skew #Up #Dn= , 2 , 2
    8690    8740
    -.09   24.91
    8650    8700
    -.09   24.91
Abutment Skew #Up #Dn= , 2 , 2
   12507   12557
   24.91    -.09
   12333   12383
   24.91    -.09
Abutment Skew #Up #Dn= , 2 , 2
   12607   12657
    -.09   24.91
   12433   12483
    -.09   24.91
Abutment Skew #Up #Dn= , 2 , 2
   13605   13620
    25.5    17.7
   13310   13325
    25.5    17.7
Abutment Skew #Up #Dn= , 2 , 2
   14025   14040
      18    25.5
   13730   13745
      18    25.5
BR Coef=-1 , 1 , 0 ,, 0 ,,,0.8,0,2,0,
WSPro=,,,, 1 ,,,, 0 ,,,, 0 ,,,,-1 ,-1 ,-1 , 0 , 0 , 0 , 0 , 0
BR Coef=-1 ,-1 , 0 ,, 0 ,,,0.8,0,2,0,
WSPro=,,,, 1 ,,,, 0 ,,,, 0 ,,,,-1 ,-1 ,-1 , 0 , 0 , 0 , 0 , 0
BR Coef=-1 ,-1 , 0 ,, 0 ,,,0.8,0,1.2,0,
WSPro=,,,, 1 ,,,, 0 ,,,, 0 ,,,,-1 ,-1 ,-1 , 0 , 0 , 0 , 0 , 0
BC Mult= 3 ,0,10990,0,10990
BC Mult= 3 ,10490,13300,10490,13100
BC Mult= 3 ,12800,16406,12600,16229
BC Design=,, 0 ,, 0 ,,28,13620,13325,15,5
BC Use User HTab Curves=0
BC User HTab FreeFlow(D)= 0

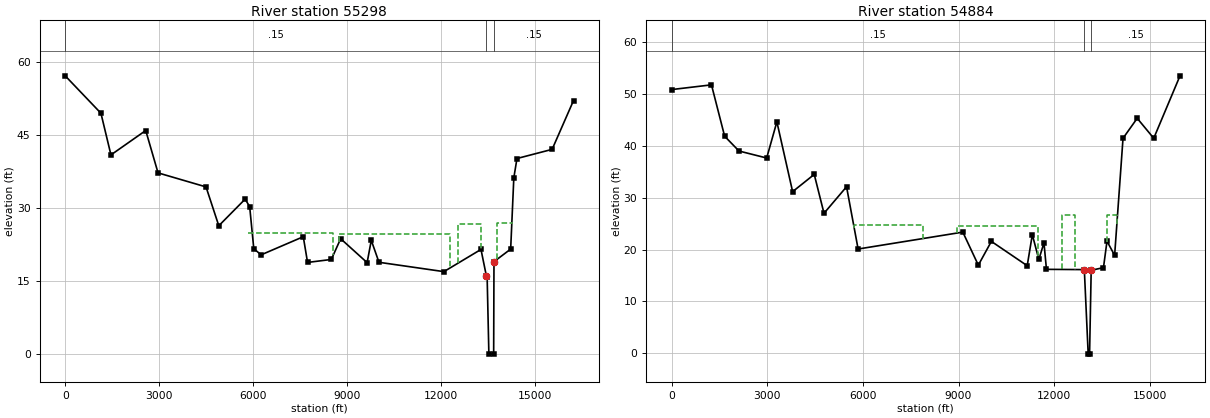
Type RM Length L Ch R = 1 ,55298   ,413.5,413.5,413.5
XS GIS Cut Line= 6
2393630.39708732641978.3491041592393038.05879676639382.142979573
2391507.54803687636191.8580229632392326.77242443632183.224190622
2393881.00177459628635.7356667982393455.58703222626647.612137168
#Sta/Elev= 30
       0   57.07  1140.5   49.39  1460.2   40.83  2570.8   45.84  2963.5   37.14
  4495.6   34.26  4903.1   26.28  5743.7   31.75    5889   30.21  6020.3   21.57
    6255   20.31  7600.3   24.03  7736.8   18.75  8495.2   19.36  8793.5   23.62
  9638.7   18.71  9771.3   23.29 10016.6   18.78 12089.7   16.86 13273.4   21.42
 13448.5   15.88 13470.1   15.7213525.62    -.08 13678.3    -.08 13688.3   18.91
 14221.2   21.49 14321.8   36.13 14422.5   40.09 15544.4   41.97   16228      52
#Mann= 3 ,0,0
       0     .15       0 13448.5     .05       0 13688.3     .15       0
#XS Ineff= 4 ,-1
    5850    8560   24.82    8750   12283   24.49   12533   13260   26.59
   13795   14306   26.76
Permanent Ineff=
       F       F       F       F
Bank Sta=13448.5,13688.3
XS Rating Curve= 0 ,0
Exp/Cntr(USF)=0,0
Exp/Cntr=0.5,0.3

Type RM Length L Ch R = 1 ,54884   ,337.1,337.1,337.1
XS GIS Cut Line= 6
2394322.68866886641777.0050034342391998.80223099636205.549074871
2393375.37076971631506.1219100392393873.98960343629768.717871241
2394107.03722327629266.5292095492393630.75489178626654.418297743
#Sta/Elev= 30
       0   50.86  1248.8   51.77  1661.7   41.86  2112.3   39.01  2980.9   37.66
  3300.9   44.64    3795   31.17  4473.2    34.5  4779.7      27  5487.2   32.12
  5849.8   20.11  9135.6   23.37  9621.9      17 10031.3   21.58 11155.7   16.89
 11316.1   22.88 11520.9   18.09 11681.4   21.31 11759.9   16.19 12947.9   16.14
13069.19    -.1613112.41    -.16 13163.216.00946 13548.6   16.52 13659.3   21.62
 13898.7   18.89 14162.2   41.47   14607   45.32 15126.2   41.47 15949.9   53.51
#Mann= 3 ,0,0
       0     .15       0 12947.9     .05       0 13163.2     .15       0
#XS Ineff= 4 ,-1
    5727    7890   24.82    8942   11489   24.49   12239   12665   26.59
   13674   13968   26.76
Permanent Ineff=
       F       F       F       F
Bank Sta=12947.9,13163.2
XS Rating Curve= 0 ,0
Exp/Cntr(USF)=0,0
Exp/Cntr=0.5,0.3