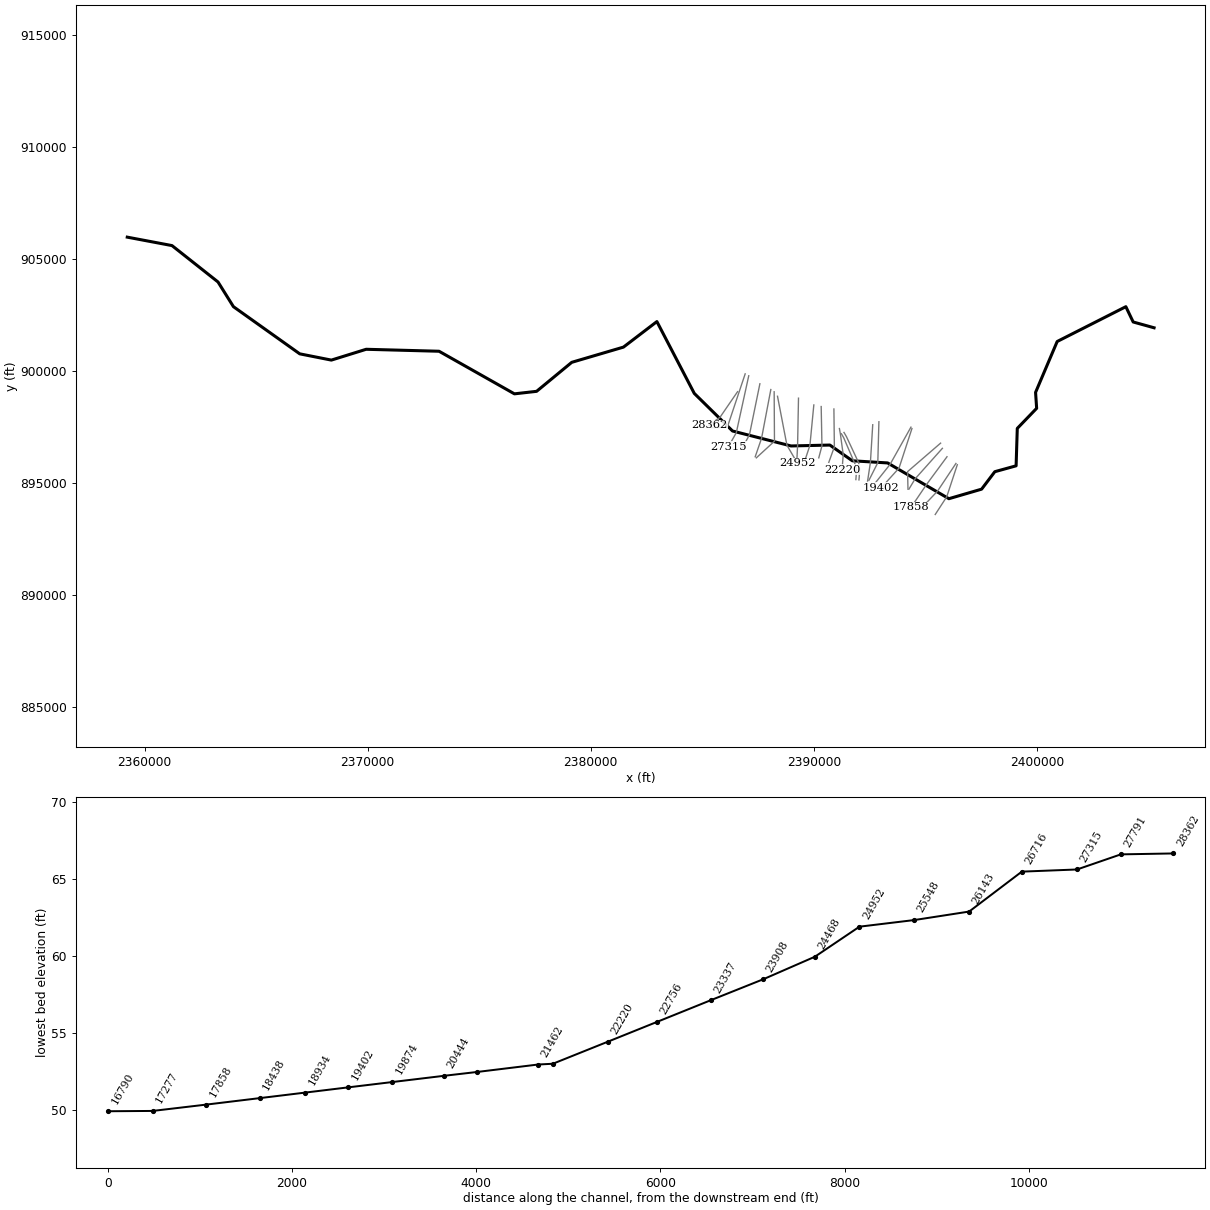
--- BackSwamp.prj (project) ---

Proj Title=S-16-495 over Back Swamp
Current Plan=p01
Default Exp/Contr=0.3,0.1
English Units
Geom File=g01
Geom File=g02
Geom File=g03
Geom File=g05
Flow File=f01
Flow File=f02
Flow File=f04
Plan File=p01
Plan File=p03
Plan File=p06
Plan File=p07
Plan File=p02
Y Axis Title=Elevation
X Axis Title(PF)=Main Channel Distance
X Axis Title(XS)=Station
BEGIN DESCRIPTION:
END DESCRIPTION:
DSS File=dss
DSS Export Rating Curves= 0
DSS Export Rating Curve Sorted= 0
DSS Export Volume Flow Curves= 0
DXF OffsetX= 0
DXF OffsetY= 0
DXF ScaleX= 1
DXF ScaleY= 10

--- BackSwamp.p01 (plan) ---

Plan Title=Existing Conditions
Program Version=6.60
Short Identifier=Existing
Geom File=g01
Flow File=f01
Subcritical Flow
K Sum by GR= 0
Std Step Tol= 0.01
Critical Tol= 0.01
Num of Std Step Trials= 20
Max Error Tol= 0.3
Flow Tol Ratio= 0.001
Split Flow NTrial= 30
Split Flow Tol= 0.02
Split Flow Ratio= 0.02
Log Output Level= 0
Friction Slope Method= 1
Unsteady Friction Slope Method= 2
Unsteady Bridges Friction Slope Method= 1
Parabolic Critical Depth
Global Vel Dist= 0 , 0 , 0
Global Log Level= 0
CheckData=True
Encroach Param=-1 ,0,0, 0
Flow Ratio Tolerance=0.1
Flow Ratio Min Ratio=0.5
Flow Ratio Max Ratio=4
Flow Ratio Max Iterations= 10
Computation Interval=1MIN
Output Interval=1HOUR
Instantaneous Interval=1HOUR
Mapping Interval=1HOUR
Computation Time Step Use Courant=        0
Computation Time Step Use Time Series=    0
Computation Time Step Count To Double=0
Computation Time Step Max Doubling=0
Computation Time Step Max Halving=0
Computation Time Step Residence Courant=0
Run HTab= 0
Run UNet= 0
Run Sediment= 0
Run PostProcess= 0
Run WQNet= 0
Run RASMapper= 0
UNET Theta= 1
UNET Theta Warmup= 1
UNET ZTol= 0.02
UNET ZSATol= 0.02
UNET MxIter= 20
UNET Max Iter WO Improvement= 0
UNET MaxInSteps= 0
UNET DtIC= 0
UNET DtMin= 0
UNET MaxCRTS= 20
UNET WFStab= 2
UNET SFStab= 1
UNET WFX= 1
UNET SFX= 1
UNET Gravity=32.17405
UNET 1D Methodology=Finite Difference
UNET DSS MLevel= 4
UNET Pardiso=0
UNET DZMax Abort= 100
UNET Use Existing IB Tables=-1
UNET Froude Reduction=False
UNET Froude Limit= 0.8
UNET Froude Power= 4
UNET D1 Cores= 0
UNET WindReference=Eulerian
UNET WindDragFormulation=Hsu (1988)
UNET D2 Coriolis=0
UNET D2 Cores= 0
UNET D2 Theta= 1
UNET D2 Theta Warmup= 1
UNET D2 Z Tol= 0.01
UNET D2 Volume Tol= 0.01
UNET D2 Max Iterations= 20
UNET D2 Advanced Convergence=0
UNET D2 WS Max Tol=0.15
UNET D2 WS RMS Tol=0.002
UNET D2 WS Stall Tol=1
UNET D2 Equation= 0
UNET D2 RampUpFraction=0.1
UNET D2 TimeSlices= 1
UNET D2 Turbulence Formulation=None
UNET D2 Eddy Viscosity=0.3
UNET D2 Transverse Eddy Viscosity=0.1
UNET D2 Smagorinsky Mixing=0.05
UNET D2 BCVolumeCheck=0
UNET D2 Cores=0
UNET D2 SolverType=PARDISO (Direct)
UNET D2 Minimum Iterations= 3
UNET D2 Maximum Iterations= 30
UNET D2 Restart Number= 10
UNET D2 Relaxation Coeff=1.3
UNET D2 SOR Precondition Iterations= 10
UNET D2 ILUT Maximum Fill= 8
UNET D2 ILUT Tolerance=1E-08
UNET D2 Convergence Tolerance=0.00001
PS Theta= 1
PS WS Tol= 0.01
PS Volume Tol= 0.01
PS Max Iterations= 20
PS Equation= 0
PS Advance Time Step=-1
PS Target Courant=0.9
PS Time Slices= 1
PS Iterate With 2D=0
PS Project Initial WSE from DS=-1
PS Ramp Up Initial WSE from US=-1
PS Cores=0
UNET D1D2 MaxIter= 0
UNET D1D2 ZTol=0.01
UNET D1D2 QTol=0.1
UNET D1D2 MinQTol=1
DSS File=dss
Write IC File= 0
Write IC File at Fixed DateTime=0
Write IC File at Sim End=0
Echo Input=False
Echo Parameters=False
Echo Output=False
Write Detailed= 0
HDF Write Warmup=0
HDF Write Time Slices=0
HDF Flush=0
HDF Compression= 1
HDF Chunk Size= 1
HDF Spatial Parts= 1
HDF Use Max Rows=0
HDF Fixed Rows= 1
Calibration Method= 0
Calibration Iterations= 20
Calibration Max Change=0.05
Calibration Tolerance=0.2
Calibration Maximum=1.5
Calibration Minimum=0.5
Calibration Optimization Method= 1
WQ AD Non Conservative
WQ ULTIMATE=-1
WQ Max Comp Step=1HOUR
WQ Output Interval=15MIN
WQ Output Selected Increments= 0
WQ Create Restart=0
WQ Fixed Restart=0
WQ System Summary=0
WQ Write To DSS=0
Sorting and Armoring Iterations= 10
XS Update Threshold= 0.02
Bed Roughness Predictor= 0
Processes Affected by Predictor=Sediment Only
Hydraulics Update Threshold= 0.02
Energy Slope Method= 1
Volume Change Method= 1
Sediment Retention Method= 0
Sediment TS Multiplier= 1
Warm Up Method= 0
XS Weighting Method= 0
Number of US Weighted Cross Sections= 1
Number of DS Weighted Cross Sections= 1
Upstream XS Weight=0
Main XS Weight=1
Downstream XS Weight=0
Number of DS XS's Weighted with US Boundary= 1
Upstream Boundary Weight= 1
Weight of XSs Associated with US Boundary= 0
Number of US XS's Weighted with DS Boundary= 1
Downstream Boundary Weight= 0.5
Weight of XSs Associated with DS Boundary= 0.5
Percentile Method= 0
Sediment Output Level= 3
Mass or Volume Output= 0
Output Increment Type= 1
Profile and TS Output Increment= 1
Transport Output Increment 1
XS Output Flag= 0
XS Output Increment= 10
Read HDF5 Sediment Hotstart= 0
Sediment Hotstart Type= 0
Write Gradation File= 0
Read Gradation Hotstart= 0
Write HDF5 File= 1
Write Binary Output= 1
Write DSS Sediment File= 0
DSS Sediment Output Type= 1
SV Curve= 0
Specific Gage Flag= 0
Subcell Erosion Methods= 0
Subcell Deposition Methods= 0
Advection Scheme= 1
Matrix Solver= 0
Implicit Weighting Factor= 1
Maximum Outer Loop Convergence Iterations= 5
Convergence Maximum Absolute= 0.001
Convergence RMSE= 0.0001
Grain Fractions Max Abs Error= 0.001
Max Subgrid Regions= 1
Max Subgrid Length Scale= 3.402823E+38
Initial Layer Thickness= 3
Min Layer Thickness= 0.1
Max Layer Thickness= 6
Number of Layers= 5

--- BackSwamp.p02 (plan) ---

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Plan Title=Natural Conditions
Short Identifier=Natural
Geom File=g02
Flow File=f01

--- BackSwamp.p03 (plan) ---

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Plan Title=Sensitivity Analysis
Short Identifier=Sensitivity
Geom File=g01
Flow File=f02

--- BackSwamp.p06 (plan) ---

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Plan Title=Duplicate Effective
Short Identifier=DE
Geom File=g03
Flow File=f04

--- BackSwamp.p07 (plan) ---

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Plan Title=Proposed Conditions
Short Identifier=Proposed
Geom File=g05
Flow File=f01

--- BackSwamp.f01 (steady flow) ---

Flow Title=USGS Regression Equations
Program Version=6.60
Number of Profiles= 6
Profile Names=2-year,10-year,25-year,50-year,100-year,500-year
River Rch & RM=Back Swamp,Reach-1         ,28362
     527    1410    1990    2520    3050    4400
Boundary for River Rch & Prof#=Back Swamp,Reach-1         , 1
Up Type= 0
Dn Type= 3
Dn Slope=0.0012
Boundary for River Rch & Prof#=Back Swamp,Reach-1         , 2
Up Type= 0
Dn Type= 3
Dn Slope=0.0012
Boundary for River Rch & Prof#=Back Swamp,Reach-1         , 3
Up Type= 0
Dn Type= 3
Dn Slope=0.0012
Boundary for River Rch & Prof#=Back Swamp,Reach-1         , 4
Up Type= 0
Dn Type= 3
Dn Slope=0.0012
Boundary for River Rch & Prof#=Back Swamp,Reach-1         , 5
Up Type= 0
Dn Type= 3
Dn Slope=0.0012
Boundary for River Rch & Prof#=Back Swamp,Reach-1         , 6
Up Type= 0
Dn Type= 3
Dn Slope=0.0012
DSS Import GetInterval= 0
DSS Import GetPeak= 0
DSS Import FillOption= 0

--- BackSwamp.f02 (steady flow) ---

Flow Title=USGS Regression Equations-Sensitivity
Program Version=6.60
Number of Profiles= 3
Profile Names=-3ft,100-Year,+3ft
River Rch & RM=Back Swamp,Reach-1         ,28362
    3050    3050    3050
Boundary for River Rch & Prof#=Back Swamp,Reach-1         , 1
Up Type= 0
Dn Type= 1
Dn Known WS=42.66
Boundary for River Rch & Prof#=Back Swamp,Reach-1         , 2
Up Type= 0
Dn Type= 1
Dn Known WS=45.66
Boundary for River Rch & Prof#=Back Swamp,Reach-1         , 3
Up Type= 0
Dn Type= 1
Dn Known WS=48.66
DSS Import GetInterval= 0
DSS Import GetPeak= 0
DSS Import FillOption= 0

--- BackSwamp.f04 (steady flow) ---

Flow Title=Duplicate Effective Flowrates
Program Version=6.60
Number of Profiles= 1
Profile Names=100-year
River Rch & RM=Back Swamp,Reach-1         ,60711
     914
River Rch & RM=Back Swamp,Reach-1         ,52533
    1130
River Rch & RM=Back Swamp,Reach-1         ,41908
    1210
River Rch & RM=Back Swamp,Reach-1         ,34298
    1236
River Rch & RM=Back Swamp,Reach-1         ,33816
    2303
River Rch & RM=Back Swamp,Reach-1         ,29419
    2531
River Rch & RM=Back Swamp,Reach-1         ,21026
    2769
River Rch & RM=Back Swamp,Reach-1         ,9837
    2811
River Rch & RM=Back Swamp,Reach-1         ,5108
    3581
Boundary for River Rch & Prof#=Back Swamp,Reach-1         , 1
Up Type= 0
Dn Type= 3
Dn Slope=0.0002
DSS Import GetInterval= 0
DSS Import GetPeak= 0
DSS Import FillOption= 0

--- BackSwamp.g01 (geometry) ---

Geom Title=Existing Conditions
Program Version=6.60

River Reach=Back Swamp      ,Reach-1
Reach XY= 30
      2359218.28       905979.01      2361224.34       905602.08
      2363287.65       903977.68      2363979.12       902875.05
      2366951.81        900769.2      2368370.71       900489.72
      2369930.23       900972.58      2373199.02       900884.68
      2376578.32       898983.23      2377572.85       899095.21
      2379149.53       900390.34      2381467.28       901069.37
      2382966.55       902209.57      2384643.09       899002.79
      2386358.22       897323.99       2388982.5       896656.21
      2390723.13       896696.66      2391729.65       895994.31
      2393312.74       895898.18      2396059.42       894301.61
      2397526.81       894728.05      2398119.24       895507.63
       2399073.3        895769.9      2399126.16       897439.84
      2399994.15       898337.02       2399946.2       899047.71
      2400915.59       901320.17      2403994.05       902874.11
      2404323.13       902191.25      2405259.74       901932.39

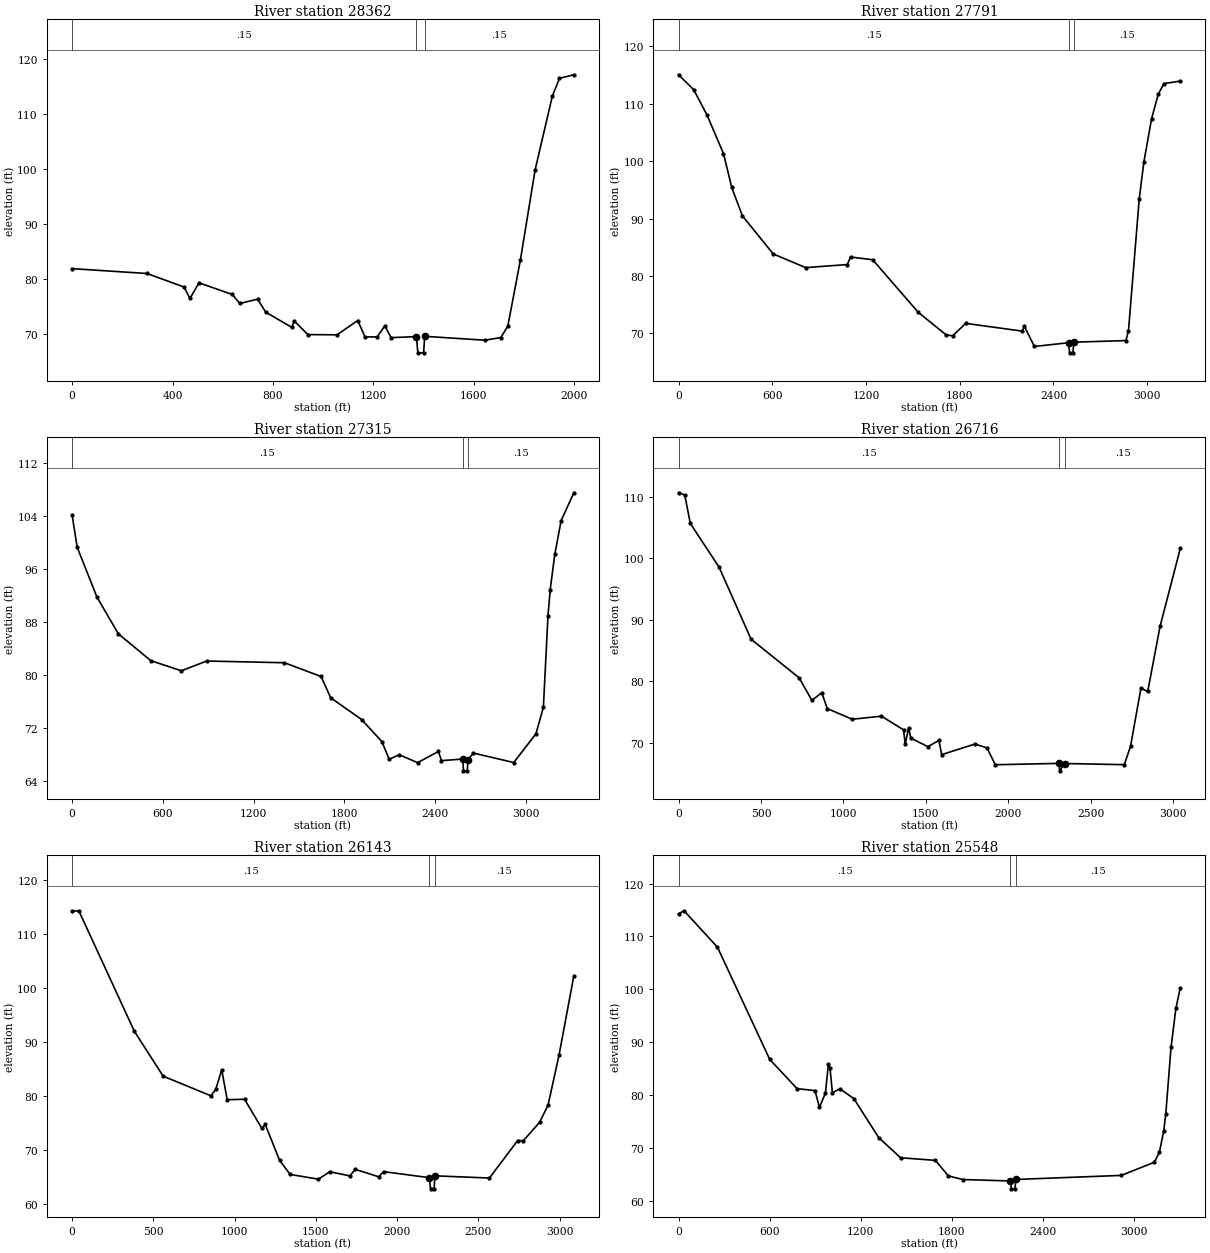
Type RM Length L Ch R = 1 ,28362   ,330.7,571.2,416.1
BEGIN DESCRIPTION:
Back Swamp 35.0
END DESCRIPTION:
XS GIS Cut Line= 3
      2386584.41       899080.47       2385797.5       897937.58
      2385299.37       897584.61
#Sta/Elev= 30
       0   81.91  298.23   81.03  445.62   78.58  469.52   76.51  505.38   79.34
  638.02   77.23  667.99   75.59  738.77   76.38  771.09   74.02  875.24   71.25
  883.82   72.46  938.88   69.95 1055.12   69.91 1137.48    72.5 1166.66   69.53
 1215.34   69.53 1245.53   71.56 1270.24    69.4  1371.1  69.582  1376.9   66.64
 1399.86   66.64  1404.1  69.637 1644.11   68.93 1707.65   69.42 1735.22    71.5
 1785.32    83.5  1843.8   99.82 1912.42  113.19 1940.66  116.43 1998.11  117.07
#Mann= 3 ,0,0
       0     .15       0  1371.1     .05       0  1404.1     .15       0
Bank Sta=1371.1,1404.1
XS Rating Curve= 0 ,0
Exp/Cntr=0.3,0.1

Type RM Length L Ch R = 1 ,27791   ,371.1,476.1,706.3
BEGIN DESCRIPTION:
Back Swamp 34.0
END DESCRIPTION:
XS GIS Cut Line= 3
        2386925.         899875.      2386124.03       897493.28
      2385424.97         897475.
#Sta/Elev= 30
       0  115.06   96.97  112.47  183.52  107.97  287.78  101.32  340.47   95.42
  408.53   90.48  605.85   83.83  813.66   81.44  1080.1   81.97 1100.87   83.29
  1242.8   82.81 1533.58   73.67 1713.59   69.69 1755.13   69.56 1838.21   71.72
 2201.69   70.36 2212.08    71.3 2277.85   67.69  2496.3  68.341  2503.3   66.58
 2524.87   66.58  2529.3  68.438 2863.87   68.72 2880.29   70.47 2949.21   93.46
 2978.75   99.86 3027.99  107.38 3070.66  111.66 3106.76  113.52 3212.09  113.96
#Mann= 3 ,-1,0
       0     .15       0  2496.3     .05       0  2529.3     .15       0
Bank Sta=2496.3,2529.3
XS Rating Curve= 0 ,0
Exp/Cntr=0.3,0.1

Type RM Length L Ch R = 1 ,27315   ,589.3,599.3,607.5
BEGIN DESCRIPTION:
Back Swamp 33.0
END DESCRIPTION:
XS GIS Cut Line= 3
        2387085.       899789.94      2386527.28       897249.94
        2386175.         896625.
#Sta/Elev= 30
       0  104.17   33.89   99.27  164.91   91.75     306   86.24  520.99   82.19
  722.55   80.67  890.51   82.14 1404.49   81.88 1646.36   79.81 1710.18    76.6
  1915.1   73.32 2049.47   69.98  2096.5   67.34 2163.69   68.02 2284.62   66.83
 2422.35   68.52 2442.51   67.14  2583.4  67.378 2588.12    65.6 2613.13    65.6
  2617.7  67.264 2653.04   68.28 2920.54   66.85 3067.43   71.19  3116.4   75.18
 3146.88   88.97  3161.6   92.91 3191.73   98.19 3233.59  103.28  3317.9  107.48
#Mann= 3 ,-1,0
       0     .15       0  2583.4     .05       0  2617.7     .15       0
Bank Sta=2583.4,2617.7
XS Rating Curve= 0 ,0
Exp/Cntr=0.3,0.1

Type RM Length L Ch R = 1 ,26716   ,559.3,572.2,612.6
BEGIN DESCRIPTION:
Back Swamp 32.0
END DESCRIPTION:
XS GIS Cut Line= 3
      2387584.75         899433.        2387117.       897156.04
      2386774.98       896524.97
#Sta/Elev= 30
       0  110.63   37.86  110.26   71.36  105.65   245.8   98.55  439.82   86.84
  731.24   80.57  808.28   76.92  868.58   78.13   901.6   75.58 1052.81   73.84
 1230.34   74.34 1364.33   72.12 1374.37   69.77 1394.47   72.41 1407.87   70.79
 1511.71   69.38  1578.7   70.41 1595.45   68.09 1796.52   69.81 1870.12   69.19
 1920.37   66.45  2307.3  66.671 2310.48   65.46  2341.7  66.651 2702.74   66.46
 2740.66   69.48 2803.51   78.89 2844.56   78.35 2919.76   88.97  3042.3   101.6
#Mann= 3 ,-1,0
       0     .15       0  2307.3     .05       0  2341.7     .15       0
Bank Sta=2307.3,2341.7
XS Rating Curve= 0 ,0
Exp/Cntr=0.3,0.1

Type RM Length L Ch R = 1 ,26143   ,449.9,595.5,409.7
BEGIN DESCRIPTION:
Back Swamp 31.0
END DESCRIPTION:
XS GIS Cut Line= 3
      2388075.01       899175.04      2387659.88       896999.69
        2387375.       896175.01
#Sta/Elev= 30
       0  114.28   42.79   114.2  383.09   92.01  560.12   83.71  854.07   80.07
   883.9   81.27  920.88   84.86  954.28   79.35 1061.18   79.43 1168.07   74.03
 1188.11   74.79 1277.01   68.12 1341.76   65.53 1515.43   64.66 1585.61   66.03
  1709.2   65.26 1742.61   66.47 1886.24    65.1  1916.3   66.05  2197.4  64.939
 2205.19   62.89 2227.54   62.87  2231.8  65.276 2567.64   64.87 2741.21   71.79
 2775.92   71.76 2876.59   75.18 2928.66   78.38 2995.72   87.58  3087.1  102.26
#Mann= 3 ,-1,0
       0     .15       0  2197.4     .05       0  2231.8     .15       0
Bank Sta=2197.4,2231.8
XS Rating Curve= 0 ,0
Exp/Cntr=0.3,0.1

Type RM Length L Ch R = 1 ,25548   ,461.2,595.8,1027.1
BEGIN DESCRIPTION:
Back Swamp 30.0
END DESCRIPTION:
XS GIS Cut Line= 3
        2388225.       899074.98      2388238.78       896869.33
      2387425.03       896125.03
#Sta/Elev= 30
       0  114.28   36.71  114.85  256.55  107.97  601.08   86.78  781.55   81.25
  899.67   80.88   929.2   77.69  968.57   80.44  988.26    85.9   998.7   85.12
 1014.51   80.48 1063.73   81.22  1155.6   79.37 1319.66   72.01 1464.03   68.19
 1693.72    67.7 1779.03   64.76 1874.18   64.08  2188.5  63.807 2194.49   62.32
 2219.03   62.34    2223   64.09 2919.29   64.86 3137.18   67.34 3170.54   69.24
 3199.43    73.3 3212.77   76.53 3247.17   89.05 3279.47   96.45 3308.49  100.32
#Mann= 3 ,-1,0
       0     .15       0  2188.5     .05       0    2223     .15       0
Bank Sta=2188.5,2223
XS Rating Curve= 0 ,0
Exp/Cntr=0.3,0.1

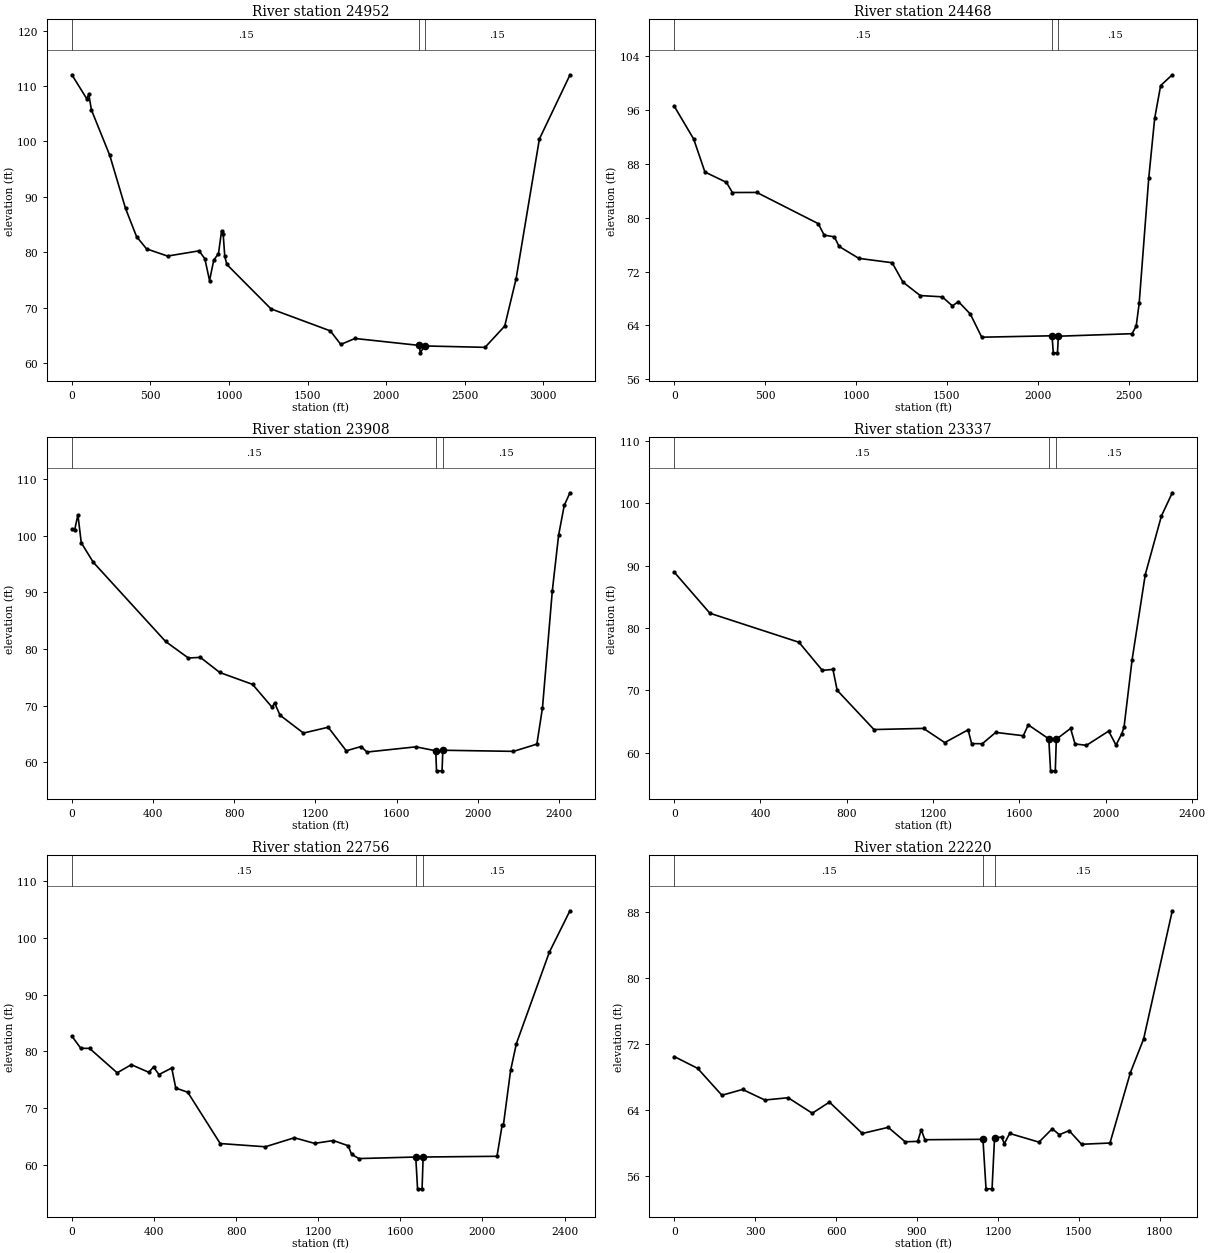
Type RM Length L Ch R = 1 ,24952   ,637.6,484.4,306.4
BEGIN DESCRIPTION:
Back Swamp 29.0
END DESCRIPTION:
XS GIS Cut Line= 3
      2388375.01       898874.96      2388797.49         896688.
      2389275.02       895874.96
#Sta/Elev= 30
       0  112.03   94.33  107.72   107.7  108.48  124.41  105.69  241.37   97.48
  341.63   87.92   411.8   82.84   475.3   80.64  608.97   79.34  809.48   80.28
  846.24   78.87  876.31   74.92  903.05   78.61  933.12   79.78  953.18   83.92
   963.2   83.24  973.23   79.28   986.5   77.82  1267.3   69.82 1644.93   65.85
 1711.76   63.41 1801.99   64.48 2211.19   63.23 2217.91   61.89  2244.8  63.134
 2629.99   62.88 2755.19   66.72 2827.49   75.23 2975.89  100.45  3170.3  111.99
#Mann= 3 ,-1,0
       0     .15       0 2211.19     .05       0  2244.8     .15       0
Bank Sta=2211.19,2244.8
XS Rating Curve= 0 ,0
Exp/Cntr=0.3,0.1

Type RM Length L Ch R = 1 ,24468   ,609.3,560.2,493.7
BEGIN DESCRIPTION:
Back Swamp 28.0
END DESCRIPTION:
XS GIS Cut Line= 3
        2389316.       898790.46      2389275.58       896694.35
       2389244.6        896050.8
#Sta/Elev= 30
       0   96.54   107.1   91.66  168.93   86.77  287.07   85.24  319.89   83.73
  454.44   83.74  792.46   79.11  825.28    77.4  881.07   77.16  907.32   75.73
 1015.62   73.96  1199.4   73.31 1258.47   70.44 1353.64   68.44 1475.06   68.25
 1530.85    66.9 1563.67   67.54  1629.3    65.7 1692.16   62.26  2079.1  62.471
 2085.94   59.94 2108.91   59.94  2113.9  62.407 2519.07   62.78 2542.06   63.89
 2558.49   67.27 2611.04   85.81 2643.89   94.74 2676.74    99.6 2740.79   101.2
#Mann= 3 ,-1,0
       0     .15       0  2079.1     .05       0  2113.9     .15       0
Bank Sta=2079.1,2113.9
XS Rating Curve= 0 ,0
Exp/Cntr=0.3,0.1

Type RM Length L Ch R = 1 ,23908   ,469.8,570.2,565.4
BEGIN DESCRIPTION:
Back Swamp 27.0
END DESCRIPTION:
XS GIS Cut Line= 3
      2390003.14       898487.09      2389828.27       896685.65
        2389625.         896075.
#Sta/Elev= 30
       0  101.11   13.24  100.96   29.72   103.7   46.21   98.76  105.54   95.31
  461.57   81.33  573.65   78.41  632.99   78.52  728.59   75.85  890.12   73.75
  985.72   69.73  998.91   70.46 1025.28   68.31 1140.66   65.15 1262.63   66.18
 1351.64   62.02 1424.17   62.77 1453.83    61.8 1694.48   62.72  1792.5  62.022
 1796.22   58.48 1823.58   58.48  1827.3  62.116 2175.47   61.92 2290.54    63.2
 2318.21   69.59 2366.62   90.24 2397.74  100.11 2425.41  105.35  2453.5  107.59
#Mann= 3 ,-1,0
       0     .15       0  1792.5     .05       0  1827.3     .15       0
Bank Sta=1792.5,1827.3
XS Rating Curve= 0 ,0
Exp/Cntr=0.3,0.1

Type RM Length L Ch R = 1 ,23337   ,566.7,581.3,537
BEGIN DESCRIPTION:
Back Swamp 26.0
END DESCRIPTION:
XS GIS Cut Line= 3
      2390333.33       898415.64      2390367.74       896661.68
      2390225.01       896125.04
#Sta/Elev= 30
       0   88.97  165.43   82.38  578.38   77.73  686.68   73.22   735.9   73.38
  755.59   70.03  926.25   63.74 1155.97   63.92 1254.42   61.65 1362.72   63.69
 1379.13   61.49 1428.36   61.46 1490.71   63.28  1618.7   62.75 1641.67   64.49
  1736.8  62.248 1745.17   57.12 1767.07   57.12  1771.8  62.184 1838.09   63.92
 1858.47   61.43  1911.7   61.21 2014.47   63.49  2048.6   61.25 2075.76   63.09
 2085.94   64.15 2123.29   74.94  2184.4   88.59  2259.1   97.96 2309.59  101.69
#Mann= 3 ,-1,0
       0     .15       0  1736.8     .05       0  1771.8     .15       0
Bank Sta=1736.8,1771.8
XS Rating Curve= 0 ,0
Exp/Cntr=0.3,0.1

Type RM Length L Ch R = 1 ,22756   ,635.1,536.5,573.7
BEGIN DESCRIPTION:
Back Swamp 25.0
END DESCRIPTION:
XS GIS Cut Line= 3
2390903.77896756898307.257179529      2390924.35       896614.94
        2390675.       895925.01
#Sta/Elev= 30
       0   82.66   43.34   80.51      86    80.5  220.53   76.19  289.44   77.62
  374.76   76.28  397.73   77.22  423.98   75.88  486.33   77.03  506.01    73.5
  564.39   72.76  722.59   63.71  942.44   63.14 1083.54   64.73 1181.98   63.74
 1273.86   64.24 1346.05   63.32 1362.45   61.81 1398.15   61.061675.083  61.332
 1683.79   55.72 1705.81   55.72 1711.04  61.333 2070.76   61.46 2095.82   66.95
 2102.16   67.04 2137.05   76.61 2165.16   81.33 2325.44   97.44 2426.05  104.77
#Mann= 3 ,0,0
       0     .15       01675.083     .05       0 1711.04     .15       0
Bank Sta=1675.083,1711.04
XS Rating Curve= 0 ,0
Exp/Cntr=0.3,0.1

Type RM Length L Ch R = 1 ,22220   ,439.1,596.9,680.3
BEGIN DESCRIPTION:
Back Swamp 24.0
END DESCRIPTION:
XS GIS Cut Line= 4
2391150.65261868 897433.787953082391192.94552217897197.131212628
2391321.18777202       896266.672391271.01950129895602.274624352
#Sta/Elev= 30
       0   70.46   86.66   69.03  176.65   65.77  253.23   66.47  336.03   65.19
  422.15   65.47  511.58   63.59  575.29   64.94  697.06   61.14  793.11   61.88
  856.04   60.13  902.41   60.18  915.66   61.59  928.91   60.38  1144.2   60.43
 1155.61   54.43 1177.92   54.43 1187.21  60.625 1213.53    60.7  1223.4   59.89
 1243.14   61.14 1351.73   60.09 1401.09   61.71 1427.41   60.99 1463.61   61.48
 1509.67   59.83 1614.97   59.98 1690.65   68.51 1739.81    72.6 1845.95   88.12
#Mann= 3 ,0,0
       0     .15       0  1144.2     .05       0 1187.21     .15       0
Bank Sta=1144.2,1187.21
XS Rating Curve= 0 ,0
Exp/Cntr=0.5,0.3

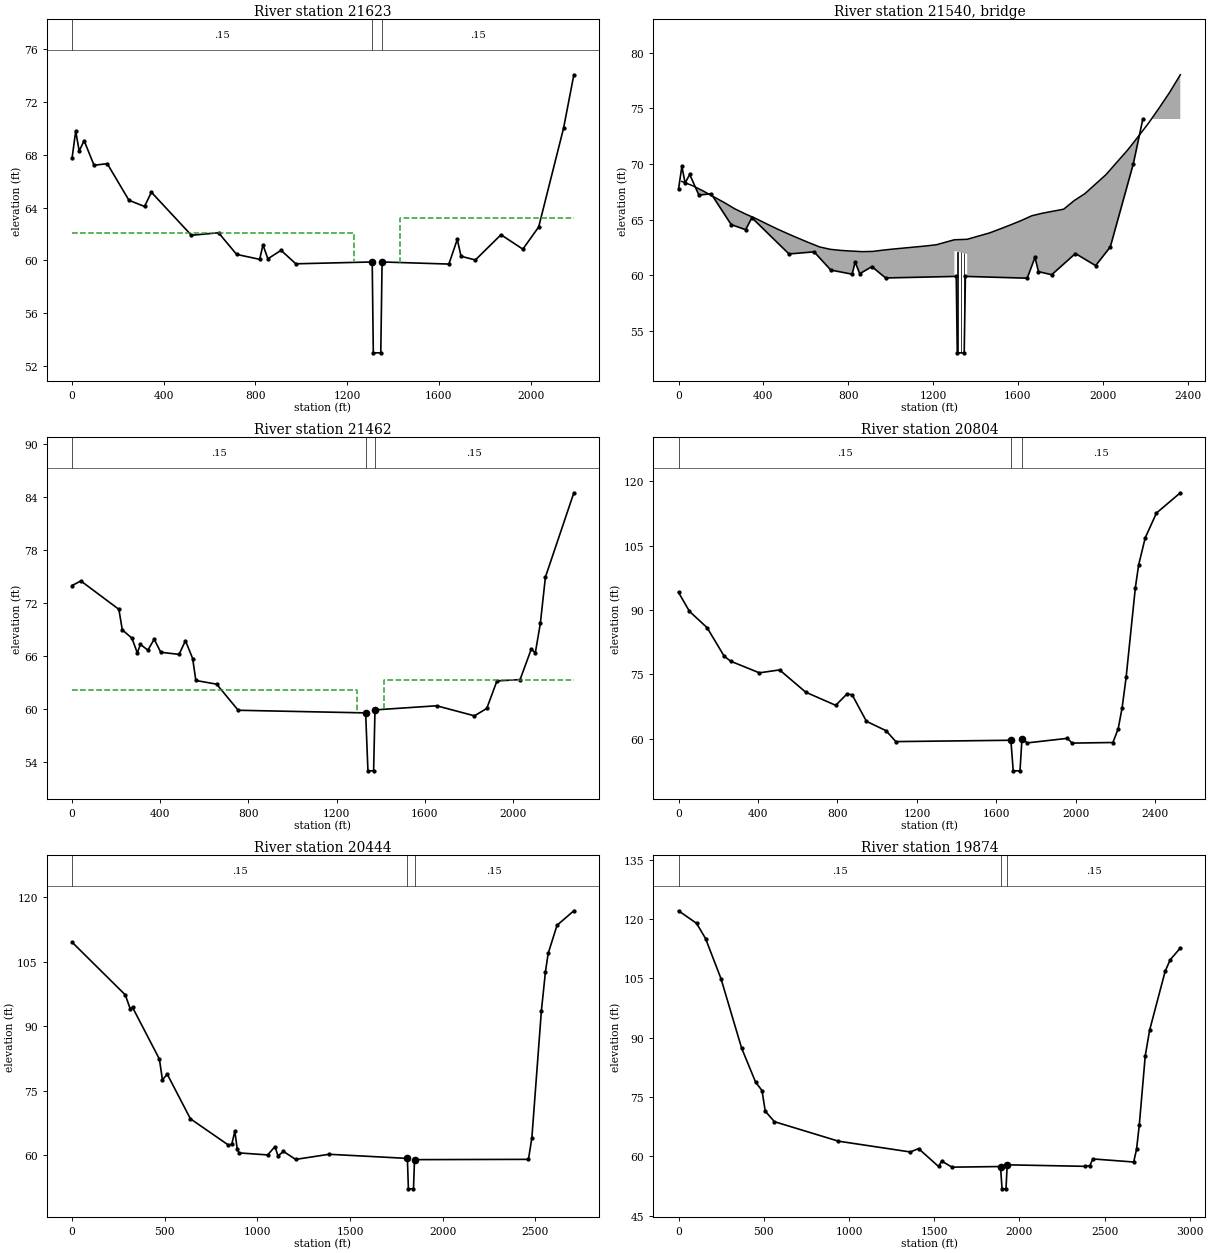
Type RM Length L Ch R = 1 ,21623   ,149.4,160.4,147.4
BEGIN DESCRIPTION:
Back Swamp 23.0
END DESCRIPTION:
XS GIS Cut Line= 6
2391240.37120011897201.4469594312391341.05151061897026.749313328
2391854.40541507895840.6757685532391902.05240594895687.819938989
2391913.31070653895505.8456908272391888.87865009 895154.57618795
#Sta/Elev= 30
       0   67.74   15.86   69.79      31   68.28   52.62   69.06   95.86    67.2
  153.52   67.32  248.06   64.55   316.2   64.08  345.89   65.16  520.63    61.9
  638.98   62.09  717.88   60.45  818.31   60.08  832.65   61.17  854.17   60.12
  911.55   60.76  976.11   59.74 1309.21   59.88 1314.03      53 1346.65      53
  1352.3   59.88 1643.71   59.72 1680.27   61.59 1696.71   60.31 1759.17   60.03
 1870.95   61.94  1966.3   60.85 2035.35   62.53 2143.92   70.01 2188.83   74.05
#Mann= 3 ,0,0
       0     .15       0 1309.21     .05       0  1352.3     .15       0
#XS Ineff= 2 , 0
         1229.51   62.11 1431.49           63.22
Permanent Ineff=
       F       F
Bank Sta=1309.21,1352.3
XS Rating Curve= 0 ,0
Exp/Cntr=0.5,0.3

Type RM Length L Ch R = 3 ,21540   ,,,
Node Name=Georgetown Rd Br
Bridge Culvert-0,0,0,0, 0
Deck Dist Width WeirC Skew NumUp NumDn MinLoCord MaxHiCord MaxSubmerge Is_Ogee
70.99572,28.6,2.6,0, 49, 49, , , 0.98, 0, 2,2,,
   15.47   65.47  115.47  165.47  215.47  265.47  315.47  365.47  415.47  465.47
  515.47  565.47  615.47  665.47  715.47  765.47  815.47  865.47  915.47  965.47
 1015.47 1065.47 1115.47 1165.47 1215.47  1300.5  1300.5  1360.5  1360.5 1415.47
 1465.47 1515.47 1565.47 1615.47 1665.47 1715.47 1765.47 1815.47 1865.47 1915.47
 1965.47 2015.47 2065.47 2115.47 2165.47 2215.47 2265.47 2315.47 2365.47
   68.43   68.05   67.58   67.05   66.53   65.96    65.5   65.08   64.61   64.15
   63.72   63.31   62.91   62.53   62.32   62.22   62.16   62.11   62.13   62.25
   62.35   62.44   62.53   62.62   62.73   63.18   63.18   63.22   63.22   63.52
   63.79   64.15   64.52   64.91   65.34   65.57   65.75   65.93   66.71   67.33
   68.19   69.05   70.14   71.22   72.43   73.67   75.04   76.46   78.03
                                                                                
                                                                                
                                                   62.17    61.9
                                                                                
                                                                        
   38.47   88.47  138.47  188.47  238.47  288.47  338.47  388.47  438.47  488.47
  538.47  588.47  638.47  688.47  738.47  788.47  838.47  888.47  938.47  988.47
 1038.47 1088.47 1138.47 1188.47 1238.47  1323.5  1323.5  1383.5  1383.5 1438.47
 1488.47 1538.47 1588.47 1638.47 1688.47 1738.47 1788.47 1838.47 1888.47 1938.47
 1988.47 2038.47 2088.47 2138.47 2188.47 2238.47 2288.47 2338.47 2388.47
   68.43   68.05   67.58   67.05   66.53   65.96    65.5   65.08   64.61   64.15
   63.72   63.31   62.91   62.53   62.32   62.22   62.16   62.11   62.13   62.25
   62.35   62.44   62.53   62.62   62.73   63.18   63.18   63.22   63.22   63.52
   63.79   64.15   64.52   64.91   65.34   65.57   65.75   65.93   66.71   67.33
   68.19   69.05   70.14   71.22   72.43   73.67   75.04   76.46   78.03
                                                                                
                                                                                
                                                   62.17    61.9
                                                                                
                                                                        
Pier Skew, UpSta & Num, DnSta & Num=  ,1315.5, 2 ,1338.5, 2 , 0 , 0 , 0 ,,
       1       1
       0    62.5
       1       1
       0    62.5
Pier Skew, UpSta & Num, DnSta & Num=  ,1330.5, 2 ,1353.5, 2 , 0 , 0 , 0 ,,
       1       1
       0    62.5
       1       1
       0    62.5
Pier Skew, UpSta & Num, DnSta & Num=  ,1345.5, 2 ,1368.5, 2 , 0 , 0 , 0 ,,
       1       1
       0    62.5
       1       1
       0    62.5
Abutment Skew #Up #Dn= , 2 , 2
  1300.5  1310.5
   62.17   57.17
  1323.5  1333.5
   62.17   57.17
Abutment Skew #Up #Dn= , 2 , 2
  1350.5  1360.5
    56.9    61.9
  1373.5  1383.5
    56.9    61.9
BR Coef=-1 ,-1 ,-1 ,0.9, 0 ,,,0.8,0,1.2,0,
WSPro=,,,, 1 ,,,, 0 ,,,, 0 ,,,,-1 ,-1 ,-1 , 0 , 0 , 0 , 0 , 0
BC Design=,, 0 ,, 0 ,,,,,,
BC HTab FreeFlow Pts= 100
BC HTab Sub Flow Curves= 60
BC HTab Sub Flow Pts= 50
BC HTab HWMax=70
BC HTab TWMax=70
BC Use User HTab Curves=0
BC User HTab FreeFlow(D)= 0

Type RM Length L Ch R = 1 ,21462   ,825.7,658.2,471.5
XS GIS Cut Line= 6
2391355.56908569897259.9680733282391464.40929705897075.329941747
2392012.51961844895908.8818954972392056.79132566895631.699397543
2392038.74965832895267.1051859812392027.01499591895139.761903067
#Sta/Elev= 30
       0   73.97   39.85   74.49  212.38   71.27  227.93   68.94  271.46      68
  296.14   66.32  310.04   67.29     344   66.64  372.57   67.88   402.4    66.4
  485.47   66.16  514.49   67.71  547.13   65.69  561.64    63.2  655.95   62.78
  753.88   59.82 1331.97  59.523 1342.47   52.95 1368.15   52.95 1374.45  59.863
 1653.94   60.33 1825.79   59.19 1881.64   60.03 1927.83   63.15 2032.76    63.3
 2083.96   66.79 2101.74   66.31 2124.74   69.68 2147.74   74.93 2276.76   84.49
#Mann= 3 ,0,0
       0     .15       0 1331.97     .05       0 1374.45     .15       0
#XS Ineff= 2 , 0
          1293.1   62.11  1413.9           63.22
Permanent Ineff=
       F       F
Bank Sta=1331.97,1374.45
XS Rating Curve= 0 ,0
Exp/Cntr(USF)=0,0
Exp/Cntr=0.5,0.3

Type RM Length L Ch R = 1 ,20804   ,315.8,360.5,240.8
BEGIN DESCRIPTION:
Back Swamp 22.0
END DESCRIPTION:
XS GIS Cut Line= 3
      2392644.63       897603.542392539.93636466895916.546557564
2392414.17849669895090.332955997
#Sta/Elev= 30
       0   94.09   55.01   89.67  143.77   85.87  229.25   79.25  262.12   78.05
  406.77   75.33  508.68   76.01  640.18   70.82   791.4   67.75  847.29   70.38
  873.59   70.23  945.91   64.02 1044.53   61.84 1093.85   59.29 1672.99  59.603
 1684.73   52.47 1718.91   52.47 1728.86  60.001 1755.24   58.99 1957.69   60.05
 1980.92   58.94  2186.7   59.08 2213.25   62.29 2233.16   67.23 2253.08   74.25
 2299.54   95.18 2316.14   100.5 2349.33  106.84 2405.75   112.6 2525.97  117.33
#Mann= 3 ,0,0
       0     .15       0 1672.99     .05       0 1728.86     .15       0
Bank Sta=1672.99,1728.86
XS Rating Curve= 0 ,0
Exp/Cntr=0.3,0.1

Type RM Length L Ch R = 1 ,20444   ,865.2,569.4,472.2
BEGIN DESCRIPTION:
Back Swamp 21.0
END DESCRIPTION:
XS GIS Cut Line= 3
      2392921.28       897737.41      2392871.76       895909.48
        2392475.       895125.01
#Sta/Elev= 30
       0  109.53  287.32   97.28  313.58   94.06  326.33   94.38  471.13   82.38
  487.54   77.57   513.8   78.84  638.53    68.5  842.03   62.44  861.73   62.54
  878.14   65.61  891.27   61.49  901.11   60.57 1055.38    60.1 1094.77   62.03
 1111.18   59.88 1140.72   60.91 1206.37   59.06  1386.9   60.25  1809.3  59.293
 1814.92   52.22 1842.31   52.22  1847.9  59.004 2462.61   59.07    2481   64.02
 2532.48   93.59 2554.54  102.72 2569.25  106.95 2617.05  113.47  2707.7  116.83
#Mann= 3 ,-1,0
       0     .15       0  1809.3     .05       0  1847.9     .15       0
Bank Sta=1809.3,1847.9
XS Rating Curve= 0 ,0
Exp/Cntr=0.3,0.1

Type RM Length L Ch R = 1 ,19874   ,309.4,472.5,398.1
BEGIN DESCRIPTION:
Back Swamp 20.0
END DESCRIPTION:
XS GIS Cut Line= 3
      2394358.01       897496.45      2393421.79       895833.47
      2392774.98       895024.97
#Sta/Elev= 30
       0  122.09  105.71  118.92  158.42  115.08  248.79  104.97  370.07   87.38
  452.11   78.78  489.76   76.65  508.59   71.45   562.8   68.78  937.83   63.86
 1359.66   61.13 1408.24   61.98 1525.34   57.46 1544.16   58.81 1604.41   57.29
  1888.9  57.448 1897.92   51.81  1921.2   51.81    1928  57.879 2384.34    57.5
 2413.27   57.69 2430.56   59.37 2670.07   58.59 2686.87   61.78    2703   67.92
 2738.01   85.43 2763.69   91.92 2854.95  106.82 2884.36  109.71  2943.8  112.68
#Mann= 3 ,-1,0
       0     .15       0  1888.9     .05       0    1928     .15       0
Bank Sta=1888.9,1928
XS Rating Curve= 0 ,0
Exp/Cntr=0.3,0.1

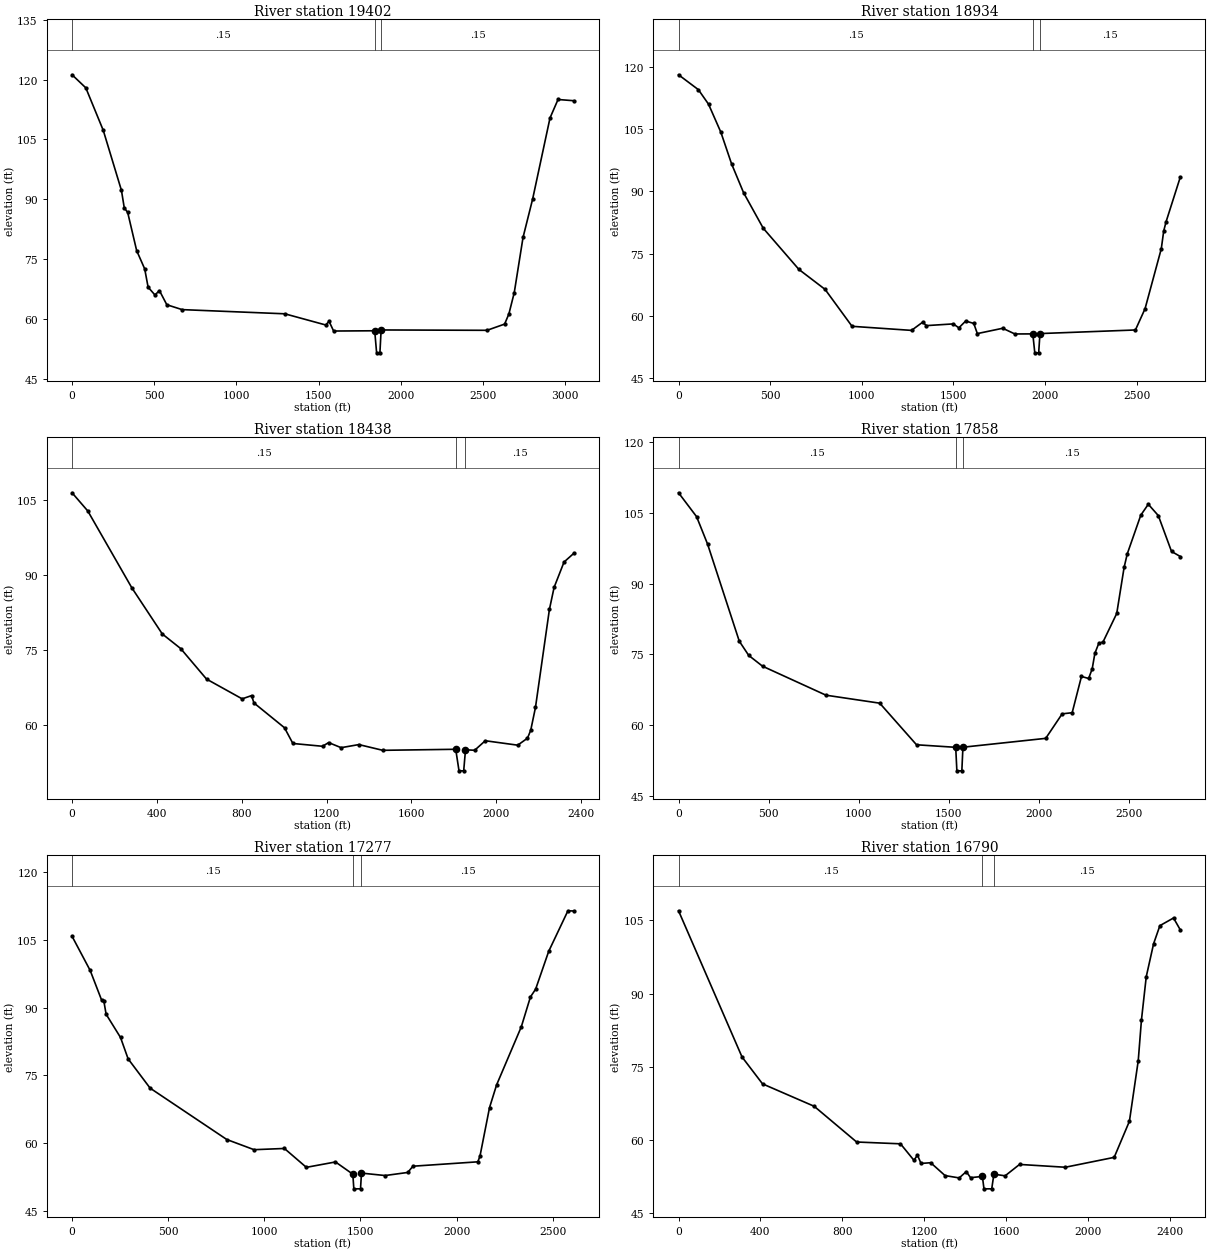
Type RM Length L Ch R = 1 ,19402   ,819.1,467.4,705.1
BEGIN DESCRIPTION:
Back Swamp 19.0
END DESCRIPTION:
XS GIS Cut Line= 3
      2394402.64       897433.98      2393822.74       895665.22
      2393019.44        894783.6
#Sta/Elev= 30
       0  121.21   83.68  117.93  190.03  107.25  300.52   92.21  317.79   87.81
   338.5   86.69  393.12   77.11  442.09   72.52  462.81   67.94  504.24   65.99
  531.86   67.07  576.75   63.53  669.98   62.31 1294.95   61.26 1543.56   58.46
 1564.27   59.37 1591.83   56.94  1841.9  57.006 1853.63   51.47 1873.67   51.47
    1881  57.209  2525.5   57.12 2632.68   58.68 2658.77   61.24 2691.41   66.59
 2744.73   80.41 2803.19   90.04 2908.92  110.38 2957.75  115.01  3054.1   114.7
#Mann= 3 ,-1,0
       0     .15       0  1841.9     .05       0    1881     .15       0
Bank Sta=1841.9,1881
XS Rating Curve= 0 ,0
Exp/Cntr=0.3,0.1

Type RM Length L Ch R = 1 ,18934   ,383.8,496.2,315.4
BEGIN DESCRIPTION:
Back Swamp 18.0
END DESCRIPTION:
XS GIS Cut Line= 3
      2395687.74       896782.61      2394207.09       895510.15
        2394225.       894724.96
#Sta/Elev= 30
       0  118.01  108.28  114.43  163.63  110.94  231.11  104.17  289.09   96.62
  354.94   89.64  462.13    81.1  656.81   71.19  799.58   66.39  946.67   57.51
 1271.13   56.53  1331.7    58.5 1352.56   57.68 1499.14   58.09 1529.39   57.14
 1566.62   58.78 1610.82    58.2  1630.2   55.76 1768.64   57.04 1834.94   55.67
  1932.8  55.688 1943.72   51.13 1964.86   51.13  1971.9  55.764 2492.78   56.63
 2545.29   61.75  2633.9   76.18 2647.03   80.44 2660.16   82.69  2737.7   93.42
#Mann= 3 ,-1,0
       0     .15       0  1932.8     .05       0  1971.9     .15       0
Bank Sta=1932.8,1971.9
XS Rating Curve= 0 ,0
Exp/Cntr=0.3,0.1

Type RM Length L Ch R = 1 ,18438   ,502.8,580.5,580.1
BEGIN DESCRIPTION:
Back Swamp 17.0
END DESCRIPTION:
XS GIS Cut Line= 3
      2395768.02       896550.55      2394545.01       895188.31
      2394268.77       894730.02
#Sta/Elev= 30
       0  106.47      74  102.83  281.23   87.47  425.35   78.19   512.2   75.26
  633.98   69.15  801.97   65.19  846.17   65.84   857.5   64.37 1001.55    59.4
 1041.05   56.25 1180.74   55.69 1209.61   56.43 1268.54   55.41 1352.04   56.03
    1465   54.88  1808.8  55.089 1824.34   50.77 1846.42   50.77  1854.9  54.989
 1898.11   54.89 1948.14    56.8 2101.06   55.91 2147.12   57.31 2162.44    58.9
 2184.77   63.46 2250.56   83.11 2272.67   87.52 2319.51    92.6  2365.8   94.35
#Mann= 3 ,0,0
       0     .15       0  1808.8     .05       0  1854.9     .15       0
Bank Sta=1808.8,1854.9
XS Rating Curve= 0 ,0
Exp/Cntr=0.3,0.1

Type RM Length L Ch R = 1 ,17858   ,549.1,581.2,519.6
BEGIN DESCRIPTION:
Back Swamp 16.0
END DESCRIPTION:
XS GIS Cut Line= 3
      2395975.03       896175.03      2395047.27       894923.38
      2394358.06       893909.09
#Sta/Elev= 30
       0  109.24  100.18  104.18  161.17   98.37  337.08   77.81  389.34    74.8
  466.09   72.51  818.17   66.37  1116.3   64.68 1320.51   55.87    1538  55.331
 1544.39   50.35 1571.99   50.35    1578  55.353 2037.39   57.23 2128.63   62.42
 2184.16   62.66 2235.73   70.34  2275.4   69.91 2295.23   71.94 2310.19   75.24
 2331.45   77.32 2355.56   77.66 2431.45   83.68 2472.32   93.43 2489.83    96.3
 2564.98   104.5 2606.59  106.81 2662.12  104.41 2735.34   96.82 2784.29   95.74
#Mann= 3 ,0,0
       0     .15       0    1538     .05       0    1578     .15       0
Bank Sta=1538,1578
XS Rating Curve= 0 ,0
Exp/Cntr=0.3,0.1

Type RM Length L Ch R = 1 ,17277   ,345.7,486.1,557.7
BEGIN DESCRIPTION:
Back Swamp 15.0
END DESCRIPTION:
XS GIS Cut Line= 3
      2396374.98       895874.97      2395551.91       894642.78
      2394774.99       893824.99
#Sta/Elev= 30
       0  105.74   94.21   98.19   153.4   91.67  165.23   91.45  177.07   88.52
  252.04   83.38   291.5   78.66  405.92   72.19  804.66   60.84  946.48   58.59
 1104.31   58.86 1218.49   54.69 1370.03   55.88 1460.17  53.181 1465.48   49.94
 1500.23   49.94  1505.2  53.416 1628.11   52.88 1745.77   53.56 1772.93   54.94
 2110.16   55.91  2121.4   57.14 2171.18   67.89  2207.9    72.9 2336.52   85.75
 2383.88   92.33 2411.04   94.07 2478.92  102.42 2578.97  111.38  2609.8  111.33
#Mann= 3 ,0,0
       0     .15       0 1460.17     .05       0  1505.2     .15       0
Bank Sta=1460.17,1505.2
XS Rating Curve= 0 ,0
Exp/Cntr=0.3,0.1

Type RM Length L Ch R = 1 ,16790   ,347.4,597.1,714.5
BEGIN DESCRIPTION:
Back Swamp 14.0
END DESCRIPTION:
XS GIS Cut Line= 3
      2396437.32       895818.78      2395961.46       894384.77
      2395446.78       893596.76
#Sta/Elev= 30
       0  106.98  310.27   76.98  410.52   71.46  662.88   66.86   870.3   59.53
 1084.63   59.16 1150.31   55.78  1167.6   56.84 1184.88   55.13  1232.2   55.28
 1302.42   52.64 1371.56   52.16 1406.13   53.46 1426.87   52.21  1484.8   52.47
 1492.63   49.92 1530.53   49.92    1541  52.931 1595.91   52.59 1666.45   54.93
 1889.82   54.35 2128.87   56.38 2203.33   63.79 2246.44   76.22 2262.11   84.57
 2285.63   93.46 2321.49  100.22 2352.25  103.93 2418.87   105.5  2452.1  103.05
#Mann= 3 ,0,0
       0     .15       0  1484.8     .05       0    1541     .15       0
Bank Sta=1484.8,1541
XS Rating Curve= 0 ,0
Exp/Cntr=0.3,0.1