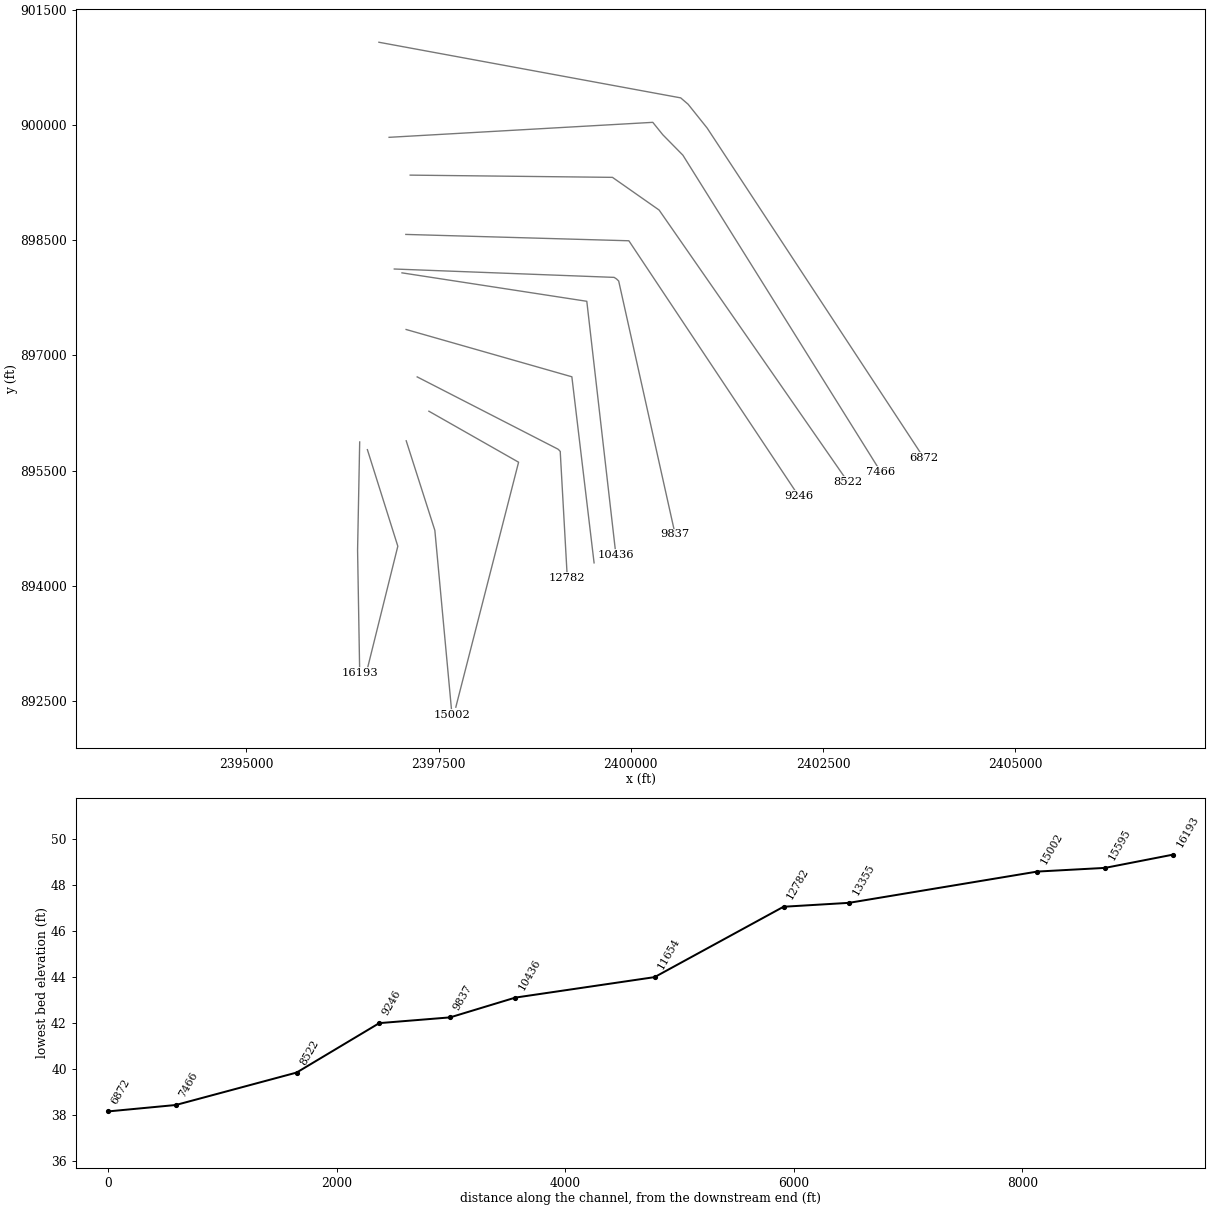
HEC-RAS study BackSwamp.prj: S-16-495 over Back Swamp

--- BackSwamp.g01 (geometry) --- (continued)

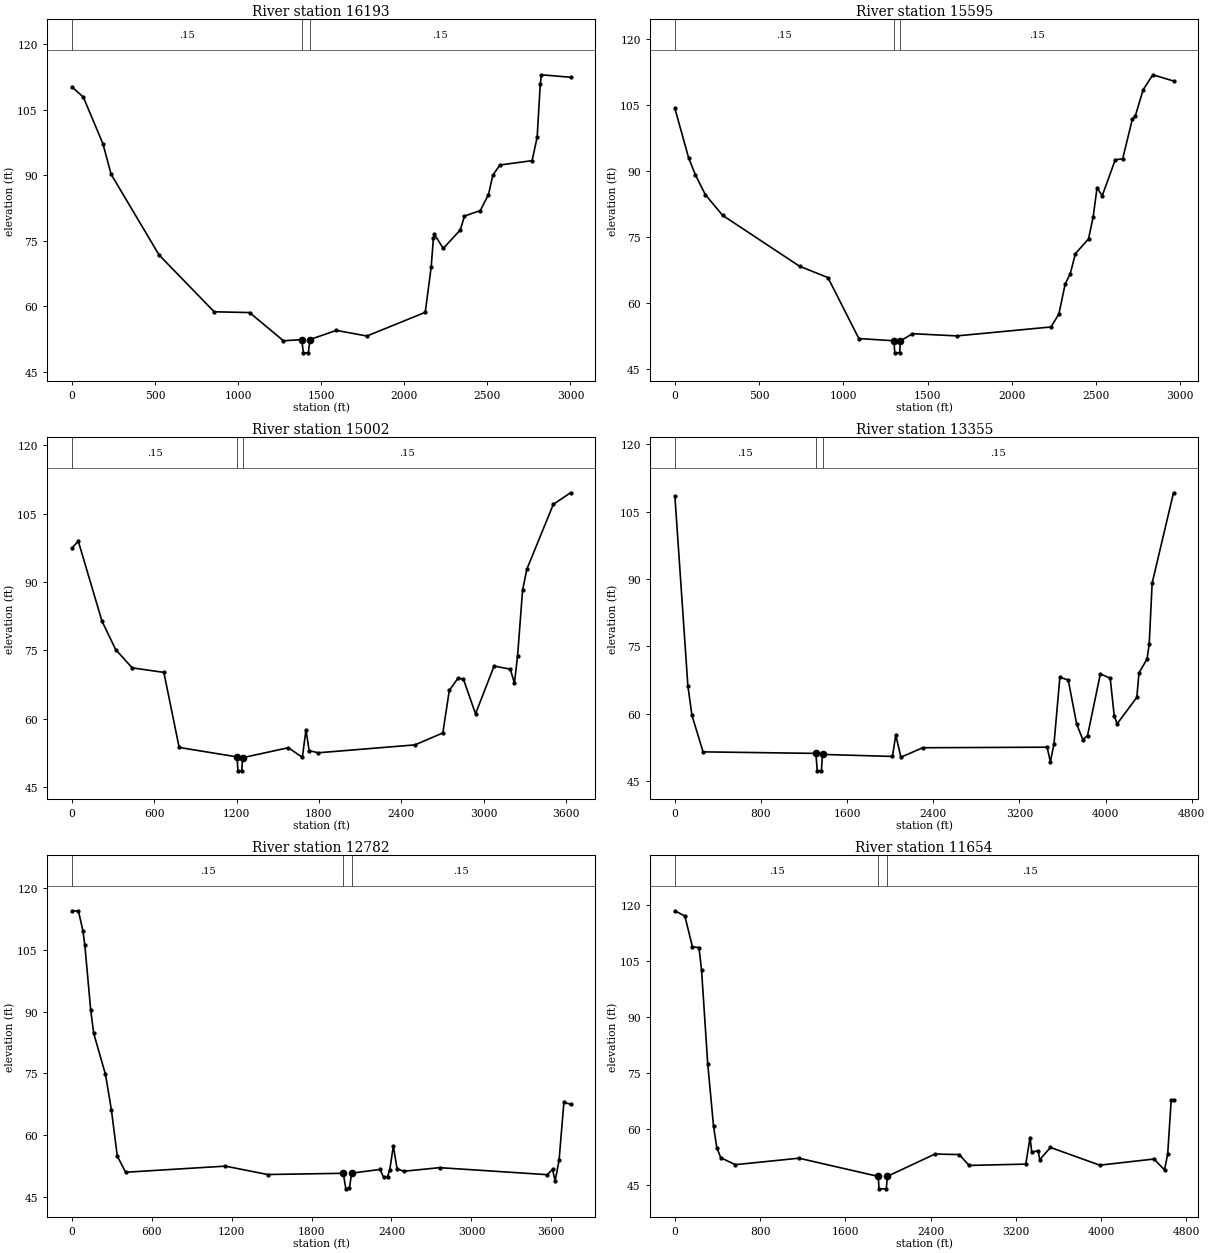
Type RM Length L Ch R = 1 ,16193   ,378.4,598.4,371.9
BEGIN DESCRIPTION:
Back Swamp 13.0
END DESCRIPTION:
XS GIS Cut Line= 3
        2396475.       895874.95      2396447.59       894466.72
        2396475.       892874.95
#Sta/Elev= 30
       0  110.21   68.49   107.9  186.63    97.2  235.86   90.22  524.64   71.73
  856.09   58.73  1069.4   58.55 1272.86   52.09  1382.4  52.356 1393.31   49.33
  1422.8   49.33 1432.52   52.38 1591.17   54.47 1774.94   53.18 2126.06    58.6
 2162.16   69.03 2175.28   75.62 2181.85   76.44 2234.35   73.24 2337.01   77.45
 2362.33   80.64 2457.21    81.9 2506.72   85.55 2532.97      90 2575.63   92.34
 2769.24   93.33 2799.72   98.72 2818.46  110.91 2825.53  112.99  3000.5  112.42
#Mann= 3 ,0,0
       0     .15       0  1382.4     .05       0 1432.52     .15       0
Bank Sta=1382.4,1432.52
XS Rating Curve= 0 ,0
Exp/Cntr=0.3,0.1

Type RM Length L Ch R = 1 ,15595   ,521.1,592.9,728.2
BEGIN DESCRIPTION:
Back Swamp 12.0
END DESCRIPTION:
XS GIS Cut Line= 3
      2396575.01       895774.98      2396970.79       894518.54
      2396574.99       892924.96
#Sta/Elev= 30
       0  104.32    81.5   93.06  121.78   89.21  180.26   84.72  283.46      80
  739.91   68.43  908.14   65.86 1091.85      52 1299.85   51.49 1305.01   48.75
 1334.16   48.78  1338.5  51.467 1410.14    53.1 1673.84    52.6 2231.66   54.63
 2278.99   57.57 2316.18   64.38  2346.6   66.73 2377.03    71.3 2454.78   74.63
 2482.69    79.7  2505.5    86.3 2535.92   84.44 2613.68   92.63 2657.63   92.86
  2715.1  101.88 2731.84   102.5 2779.33  108.57 2836.81  111.95  2959.3  110.53
#Mann= 3 ,0,0
       0     .15       0 1299.85     .05       0  1338.5     .15       0
Bank Sta=1299.85,1338.5
XS Rating Curve= 0 ,0
Exp/Cntr=0.3,0.1

Type RM Length L Ch R = 1 ,15002   ,1079.1,1647.3,962.4
BEGIN DESCRIPTION:
Back Swamp 11.0
END DESCRIPTION:
XS GIS Cut Line= 3
      2397079.84       895890.19      2397452.37       894724.57
        2397675.       892324.98
#Sta/Elev= 30
       0   97.45   46.56   98.95  218.78   81.45  318.67    75.2  439.23   71.17
  670.02   70.18  781.54   53.72  1203.6  51.645 1209.88   48.59 1237.56   48.59
  1243.9   51.47 1577.12   53.66 1679.27   51.55 1705.63   57.59  1728.7   53.03
  1794.6   52.55 2499.76   54.28 2703.06    56.9 2750.19   66.25  2812.8   68.86
 2852.34   68.75 2941.31   61.09 3076.41   71.56 3194.56    70.9 3224.72   67.82
 3247.75   73.79    3284   88.18 3315.18   92.81 3508.07  107.03  3633.6  109.57
#Mann= 3 ,0,0
       0     .15       0  1203.6     .05       0  1243.9     .15       0
Bank Sta=1203.6,1243.9
XS Rating Curve= 0 ,0
Exp/Cntr=0.3,0.1

Type RM Length L Ch R = 1 ,13355   ,405.6,572.7,1115.5
BEGIN DESCRIPTION:
Back Swamp 10.0
END DESCRIPTION:
XS GIS Cut Line= 3
      2397375.01       896274.99      2398540.98       895611.58
        2397725.       892424.99
#Sta/Elev= 30
       0  108.45  120.53    66.2  158.28    59.6  261.59   51.46 1309.22  51.117
 1322.19   47.23 1360.87   47.26 1371.04  50.887  2020.9   50.44 2051.39   55.25
  2098.8   50.26 2302.02   52.38 3456.95    52.5 3487.43   49.25  3521.3   53.31
 3575.49   68.09 3653.39   67.46 3731.29   57.66 3788.86   54.17 3832.55   55.09
 3951.44   68.84 4042.88   67.88 4080.14   59.55 4107.23   57.71 4290.12   63.61
 4310.36   69.09 4384.96   72.14 4405.28   75.49 4432.37   89.07  4630.9  109.21
#Mann= 3 ,0,0
       0     .15       0 1309.22     .05       0 1371.04     .15       0
Bank Sta=1309.22,1371.04
XS Rating Curve= 0 ,0
Exp/Cntr=0.3,0.1

Type RM Length L Ch R = 1 ,12782   ,902,1127.9,903.5
BEGIN DESCRIPTION:
Back Swamp 9.0
END DESCRIPTION:
XS GIS Cut Line= 6
2397222.75961195 896721.455715442399053.90870103 895781.15946392
2399071.49423343895764.3645352922399083.92683335895749.187825058
2399083.30130758895734.8007322712399174.23561289894109.631633875
#Sta/Elev= 30
       0   114.4   49.17  114.31   82.37  109.61   97.12  106.07  141.38   90.27
  163.51   84.73  252.03   74.78  296.29   66.24  340.55   55.01  403.25   51.08
 1151.98   52.56 1469.18   50.53  2037.8  50.821 2057.02   47.06 2084.21   47.24
  2100.5  50.858 2314.81   51.76 2340.77   49.82 2370.35   50.04 2386.78   51.63
 2413.77   57.41 2441.78   51.93 2491.93   51.32  2761.4   52.19  3569.8   50.49
 3609.23   51.77 3628.95   48.99 3658.52   54.02 3694.67   68.01 3744.51   67.54
#Mann= 3 ,0,0
       0     .15       0  2037.8     .05       0  2100.5     .15       0
Bank Sta=2037.8,2100.5
XS Rating Curve= 0 ,0
Exp/Cntr=0.3,0.1

Type RM Length L Ch R = 1 ,11654   ,897,1217.9,547.7
XS GIS Cut Line= 3
2397078.66785285897338.1407810462399233.76111215896722.855222489
2399522.65403435894302.102999195
#Sta/Elev= 30
       0  118.33   93.52  116.93  164.63  108.69  226.05  108.49  249.93  102.59
  307.94   77.49  362.53   60.78  393.24   55.02  430.78    52.3  567.26   50.46
 1164.39   52.19  1908.2  47.319 1915.84      44  1983.9      44  1993.5  47.338
 2440.45    53.3 2668.44   53.16 2760.97   50.26 3292.96   50.61  3332.6   57.69
 3349.13   53.81 3408.61    54.2 3424.12   51.79 3524.26   55.06 3986.87   50.33
 4495.43   51.97 4594.86   49.07  4624.6   53.33 4657.64   67.84 4679.14    67.8
#Mann= 3 ,0,0
       0     .15       0  1908.2     .05       0  1993.5     .15       0
Bank Sta=1908.2,1993.5
XS Rating Curve= 0 ,0
Exp/Cntr(USF)=0,0
Exp/Cntr=0.3,0.1

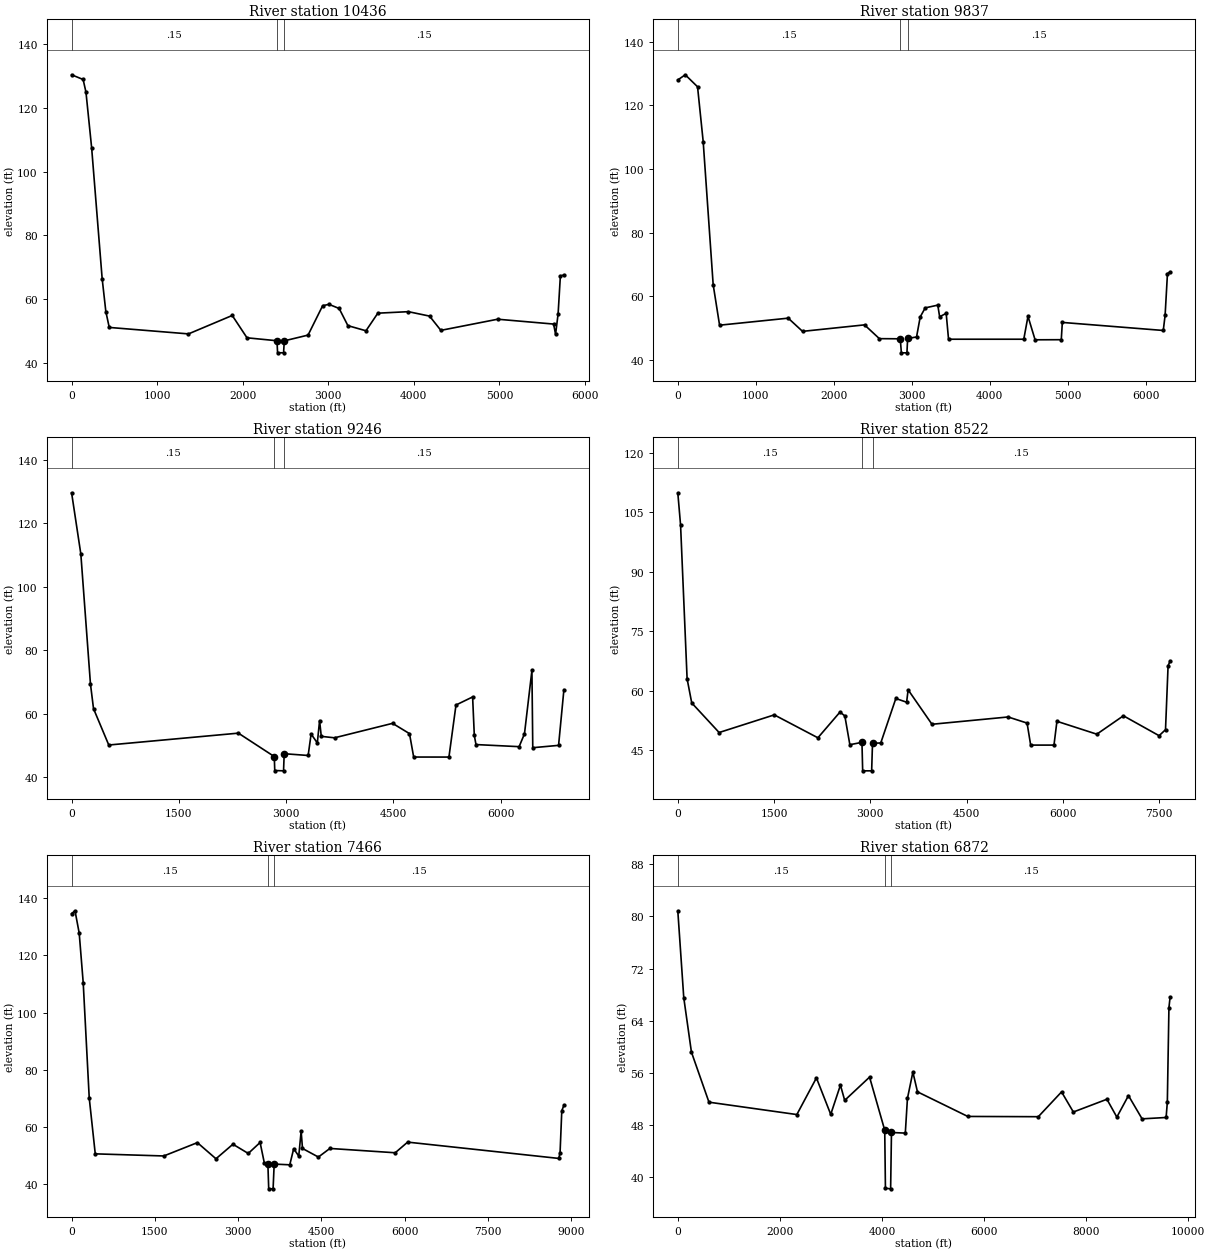
Type RM Length L Ch R = 1 ,10436   ,310.7,570.7,607.1
BEGIN DESCRIPTION:
Back Swamp 8.0
END DESCRIPTION:
XS GIS Cut Line= 3
      2397025.02         898075.2399428.00301407897705.062840913
2399806.72610839894403.930049013
#Sta/Elev= 30
       0  130.45  134.78  128.97  167.97     125  234.37   107.5  357.19   66.43
  400.35   56.06  440.19   51.09 1366.38   49.06 1877.61   54.85 2050.24   47.83
 2400.64   46.91 2407.48   43.15 2477.44   43.11  2486.3   46.88 2763.72   48.68
 2934.56   57.92  3008.1   58.34 3127.13   57.05 3229.38   51.65 3440.74   50.04
 3579.45   55.57 3936.12   56.04 4183.81   54.65 4315.92   50.17 4979.73   53.67
 5633.64   52.15 5656.75   48.95 5686.48   55.35  5712.9   67.25 5754.08   67.56
#Mann= 3 ,0,0
       0     .15       0 2400.64     .05       0  2486.3     .15       0
Bank Sta=2400.64,2486.3
XS Rating Curve= 0 ,0
Exp/Cntr=0.3,0.1

Type RM Length L Ch R = 1 ,9837    ,488.6,619.8,888.2
BEGIN DESCRIPTION:
Back Swamp 7.0
END DESCRIPTION:
XS GIS Cut Line= 5
      2396924.95         898125.2399783.30726833 898016.09633069
2399814.38168739897995.941687386 2399842.5883378897968.671475114
2400576.44252384894674.271710956
#Sta/Elev= 30
       0  128.03   95.54  129.65  253.15  125.88  325.38  108.67  453.43   63.69
  535.52   50.94 1415.48   53.15 1599.35      49 2393.93   51.04 2584.37   46.71
  2852.3   46.66 2866.43   42.25 2937.69   42.25  2946.8   46.76 3061.07   47.24
 3108.14   53.55    3172   56.38 3333.35   57.25 3356.91   53.59 3440.92   54.66
 3471.17   46.53 4435.91   46.53 4489.69   53.73 4580.77   46.35  4916.6   46.38
 4930.04   51.81  6224.2   49.28 6247.73   54.01 6277.99   67.14 6311.85   67.69
#Mann= 3 ,0,0
       0     .15       0  2852.3     .05       0  2946.8     .15       0
Bank Sta=2852.3,2946.8
XS Rating Curve= 0 ,0
Exp/Cntr=0.3,0.1

Type RM Length L Ch R = 1 ,9246    ,809.1,723.3,647.5
BEGIN DESCRIPTION:
Back Swamp 6.0
END DESCRIPTION:
XS GIS Cut Line= 3
      2397075.05         898575.      2399974.97       898492.42
2402179.62555089895176.937784994
#Sta/Elev= 30
       0  129.64  129.16  110.35  263.74   69.39  306.41    61.6  519.76   50.14
 2331.63   53.88 2833.83    46.5 2840.31    42.1 2963.13      42 2972.41    47.4
 3307.04   46.84  3348.7   53.59  3435.5   50.79 3467.03   57.84 3490.69   52.87
 3675.85   52.41 4487.53   56.97 4723.95   53.73 4782.49   46.35 5275.58   46.34
 5374.08   62.75 5606.55   65.29 5630.19   53.16 5653.71   50.28 6256.69   49.62
 6331.55   53.66  6435.7   73.67 6447.55   49.29 6808.32   50.03 6882.67   67.55
#Mann= 3 ,0,0
       0     .15       0 2833.83     .05       0 2972.41     .15       0
Bank Sta=2833.83,2972.41
XS Rating Curve= 0 ,0
Exp/Cntr=0.3,0.1

Type RM Length L Ch R = 1 ,8522    ,668.1,1056.7,641.8
XS GIS Cut Line= 4
2397131.42743578899346.4018339222399761.56712652899317.339800362
 2400368.2065648898892.0635730832402819.39563844895360.541608441
#Sta/Elev= 30
       0  109.95   43.21   101.8  144.93   63.05  217.11   56.97  643.67   49.51
 1502.85   53.96 2182.57   48.18  2527.1   54.67 2602.57   53.69 2680.58   46.44
  2869.2   47.03 2880.21   39.85 3020.22   39.85 3033.41  46.795 3162.15   46.88
 3396.85   58.09 3564.82   57.15 3588.56   60.27 3959.99   51.59 5146.19   53.43
 5441.74   51.89 5497.65   46.34 5860.75   46.34 5906.78   52.34 6528.08   49.09
 6942.54   53.73 7498.61   48.71 7598.46   50.22  7638.4   66.29 7669.99   67.57
#Mann= 3 ,0,0
       0     .15       0  2869.2     .05       0 3033.41     .15       0
Bank Sta=2869.2,3033.41
XS Rating Curve= 0 ,0
Exp/Cntr(USF)=0,0
Exp/Cntr=0.3,0.1

Type RM Length L Ch R = 1 ,7466    ,641.1,594.1,488.8
BEGIN DESCRIPTION:
Back Swamp 5.0
END DESCRIPTION:
XS GIS Cut Line= 5
2396857.27994416899838.2015939712400285.96041221900033.104377427
2400416.16298827899871.6524142672400677.21962604899606.022263291
2403250.39274279895485.560695322
#Sta/Elev= 30
       0  134.66   61.53  135.63  137.12  127.82  209.42  110.46  317.86   70.21
  426.31   50.67 1661.97   49.93 2266.66   54.59 2601.86   48.95 2907.49   54.03
 3183.96   50.81 3397.16   54.64 3474.58   47.38 3537.37  47.099 3552.44   38.47
 3631.32   38.44 3650.88  47.091 3932.03   46.84 4002.24   52.47 4093.86   49.89
 4136.72   58.59 4161.19   52.55 4447.44   49.55 4655.02   52.56 5832.28   51.05
 6055.98   54.77 8780.42   49.07  8803.1    51.1 8834.05   65.74 8871.99   67.62
#Mann= 3 ,-1,0
       0     .15       0 3537.37     .05       0 3650.88     .15       0
Bank Sta=3537.37,3650.88
XS Rating Curve= 0 ,0
Exp/Cntr=0.3,0.1

Type RM Length L Ch R = 1 ,6872    ,,,
BEGIN DESCRIPTION:
Back Swamp 4.0
END DESCRIPTION:
XS GIS Cut Line= 5
      2396725.02         901075.2400648.76024846900351.370575219
        2400745.       900268.922400992.93095547899958.642181278
2403809.16630044895669.206792049
#Sta/Elev= 30
       0   80.87  116.88   67.51  267.02   59.16  610.67   51.47 2332.23   49.57
 2715.91    55.2 2996.17    49.6 3186.34   54.09 3269.75   51.75 3756.86   55.32
 4054.11  47.165  4067.8   38.25 4169.69   38.16 4186.15  46.814 4457.31   46.72
 4499.13   52.05 4605.64   56.09 4695.67   53.06 5681.06   49.28 7063.12   49.24
 7518.42   53.05 7749.52   49.96 8407.12   51.92 8601.72   49.18 8829.37   52.48
 9096.27   48.91 9566.89   49.12 9590.81   51.46 9622.22   65.99 9645.12   67.61
#Mann= 3 ,0,0
       0     .15       0 4054.11     .05       0 4186.15     .15       0
Bank Sta=4054.11,4186.15
XS Rating Curve= 0 ,0
Exp/Cntr=0.3,0.1
LCMann Table=0

Chan Stop Cuts=-1
Use User Specified Reach Order=0
Composite Channel Slope=5

--- BackSwamp.g02 (geometry) ---

Geom Title=Natural Conditions
Program Version=6.60

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
River Reach=Back Swamp      ,Reach-1

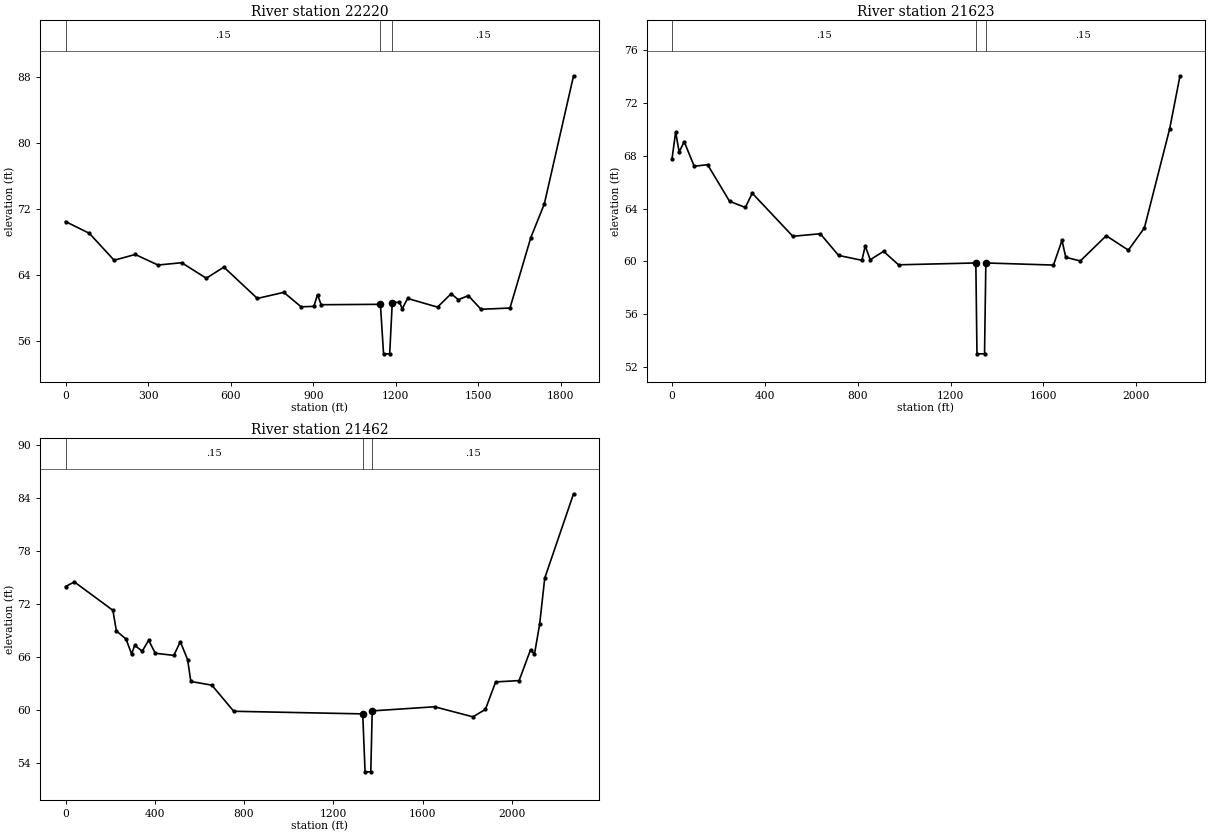
Type RM Length L Ch R = 1 ,22220   ,439.1,596.9,680.3
BEGIN DESCRIPTION:
Back Swamp 24.0
END DESCRIPTION:
XS GIS Cut Line= 4
2391150.65261868 897433.787953082391192.94552217897197.131212628
2391321.18777202       896266.672391271.01950129895602.274624352
#Sta/Elev= 30
       0   70.46   86.66   69.03  176.65   65.77  253.23   66.47  336.03   65.19
  422.15   65.47  511.58   63.59  575.29   64.94  697.06   61.14  793.11   61.88
  856.04   60.13  902.41   60.18  915.66   61.59  928.91   60.38  1144.2   60.43
 1155.61   54.43 1177.92   54.43 1187.21  60.625 1213.53    60.7  1223.4   59.89
 1243.14   61.14 1351.73   60.09 1401.09   61.71 1427.41   60.99 1463.61   61.48
 1509.67   59.83 1614.97   59.98 1690.65   68.51 1739.81    72.6 1845.95   88.12
#Mann= 3 ,0,0
       0     .15       0  1144.2     .05       0 1187.21     .15       0
Bank Sta=1144.2,1187.21
XS Rating Curve= 0 ,0
Exp/Cntr=0.3,0.1

Type RM Length L Ch R = 1 ,21623   ,149.4,160.4,147.4
BEGIN DESCRIPTION:
Back Swamp 23.0
END DESCRIPTION:
XS GIS Cut Line= 6
2391240.37120011897201.4469594312391341.05151061897026.749313328
2391854.40541507895840.6757685532391902.05240594895687.819938989
2391913.31070653895505.8456908272391888.87865009 895154.57618795
#Sta/Elev= 30
       0   67.74   15.86   69.79      31   68.28   52.62   69.06   95.86    67.2
  153.52   67.32  248.06   64.55   316.2   64.08  345.89   65.16  520.63    61.9
  638.98   62.09  717.88   60.45  818.31   60.08  832.65   61.17  854.17   60.12
  911.55   60.76  976.11   59.74 1309.21   59.88 1314.03      53 1346.65      53
  1352.3   59.88 1643.71   59.72 1680.27   61.59 1696.71   60.31 1759.17   60.03
 1870.95   61.94  1966.3   60.85 2035.35   62.53 2143.92   70.01 2188.83   74.05
#Mann= 3 ,0,0
       0     .15       0 1309.21     .05       0  1352.3     .15       0
#XS Ineff= 2 , 0
Permanent Ineff=
       F       F
Bank Sta=1309.21,1352.3
XS Rating Curve= 0 ,0
Exp/Cntr=0.3,0.1

Type RM Length L Ch R = 1 ,21462   ,825.7,658.2,471.5
XS GIS Cut Line= 6
2391355.56908569897259.9680733282391464.40929705897075.329941747
2392012.51961844895908.8818954972392056.79132566895631.699397543
2392038.74965832895267.1051859812392027.01499591895139.761903067
#Sta/Elev= 30
       0   73.97   39.85   74.49  212.38   71.27  227.93   68.94  271.46      68
  296.14   66.32  310.04   67.29     344   66.64  372.57   67.88   402.4    66.4
  485.47   66.16  514.49   67.71  547.13   65.69  561.64    63.2  655.95   62.78
  753.88   59.82 1331.97  59.523 1342.47   52.95 1368.15   52.95 1374.45  59.863
 1653.94   60.33 1825.79   59.19 1881.64   60.03 1927.83   63.15 2032.76    63.3
 2083.96   66.79 2101.74   66.31 2124.74   69.68 2147.74   74.93 2276.76   84.49
#Mann= 3 ,0,0
       0     .15       0 1331.97     .05       0 1374.45     .15       0
#XS Ineff= 2 , 0
Permanent Ineff=
       F       F
Bank Sta=1331.97,1374.45
XS Rating Curve= 0 ,0
Exp/Cntr(USF)=0,0
Exp/Cntr=0.3,0.1

--- BackSwamp.g03 (geometry) ---

Geom Title=Duplicate Effective
Program Version=6.60

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
River Reach=Back Swamp      ,Reach-1

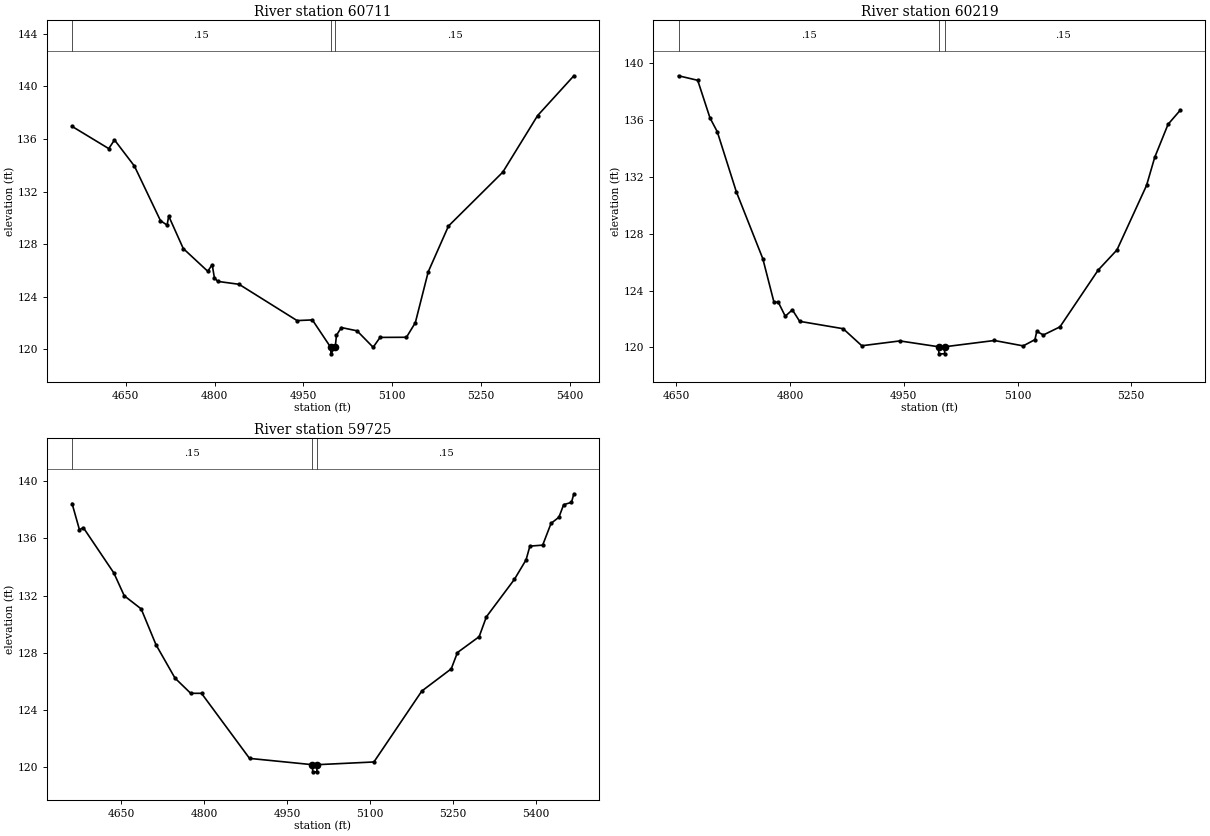
Type RM Length L Ch R = 1 ,60711   ,492,492,492
BEGIN DESCRIPTION:
Back Swamp 101.0
END DESCRIPTION:
XS GIS Cut Line= 3
      2361022.07       906111.87      2360923.81       905682.17
        2360925.       905274.97
#Sta/Elev= 30
  4559.2  136.96  4621.2  135.27  4630.9  135.93  4664.6  133.94  4708.6  129.79
  4719.8  129.45  4722.5  130.14  4747.1  127.67  4788.5  125.94    4796  126.44
  4799.7  125.45  4805.4  125.17  4841.4  124.95  4939.4  122.19  4965.3  122.24
  4996.2  120.16  4996.7  119.66  5003.9  120.16    5006  121.07  5014.3  121.66
  5040.8  121.41    5068  120.16  5079.7  120.91  5124.3  120.92  5139.3  122.03
  5161.1   125.9  5195.3  129.38  5287.1  133.48  5345.9  137.78  5407.2  140.81
#Mann= 3 ,-1,0
  4559.2     .15       0  4996.2     .05       0  5003.9     .15       0
Bank Sta=4996.2,5003.9
XS Rating Curve= 0 ,0
Exp/Cntr=0.3,0.1

Type RM Length L Ch R = 1 ,60219   ,494,494,494
BEGIN DESCRIPTION:
Back Swamp 100.0
END DESCRIPTION:
XS GIS Cut Line= 3
      2361525.01       905775.01      2361335.75       905483.92
      2361275.01       905175.04
#Sta/Elev= 30
  4652.8  139.13  4678.1  138.81  4694.3  136.16  4703.9  135.19  4729.1  130.95
    4764  126.24  4778.7  123.18  4784.4  123.18  4793.6  122.19    4803  122.64
  4812.6  121.83    4870  121.31  4894.6  120.11  4944.8  120.45  4995.8  120.04
  4996.3  119.54  5003.7  119.54  5004.2  120.04  5069.5  120.48  5107.5   120.1
    5123  120.54  5125.4  121.12  5134.2  120.87    5156  121.44  5206.4  125.44
  5231.2  126.86  5270.2   131.4    5281  133.38  5298.6  135.71  5314.8  136.71
#Mann= 3 ,-1,0
  4652.8     .15       0  4995.8     .05       0  5004.2     .15       0
Bank Sta=4995.8,5004.2
XS Rating Curve= 0 ,0
Exp/Cntr=0.3,0.1

Type RM Length L Ch R = 1 ,59725   ,471,471,471
BEGIN DESCRIPTION:
Back Swamp 99.0
END DESCRIPTION:
XS GIS Cut Line= 3
      2361903.03       905539.63      2361698.54       905152.07
      2361334.55       904858.21
#Sta/Elev= 30
  4561.8  138.44  4575.1  136.61  4582.2  136.75  4637.3  133.58    4656  131.99
  4686.6  131.07  4713.4  128.56  4747.7  126.23    4776  125.17  4795.5  125.17
  4882.2  120.62  4995.8  120.18  4996.3  119.68  5003.7  119.68  5004.2  120.18
  5106.8  120.37  5193.3  125.33  5246.4  126.88  5257.6  128.02  5296.8  129.13
  5309.9  130.52  5360.5  133.14  5381.5   134.5  5388.4  135.46  5411.5  135.53
  5426.6  137.05  5440.8  137.48  5449.4  138.36  5463.5  138.52  5467.8  139.12
#Mann= 3 ,-1,0
  4561.8     .15       0  4995.8     .05       0  5004.2     .15       0
Bank Sta=4995.8,5004.2
XS Rating Curve= 0 ,0
Exp/Cntr=0.3,0.1