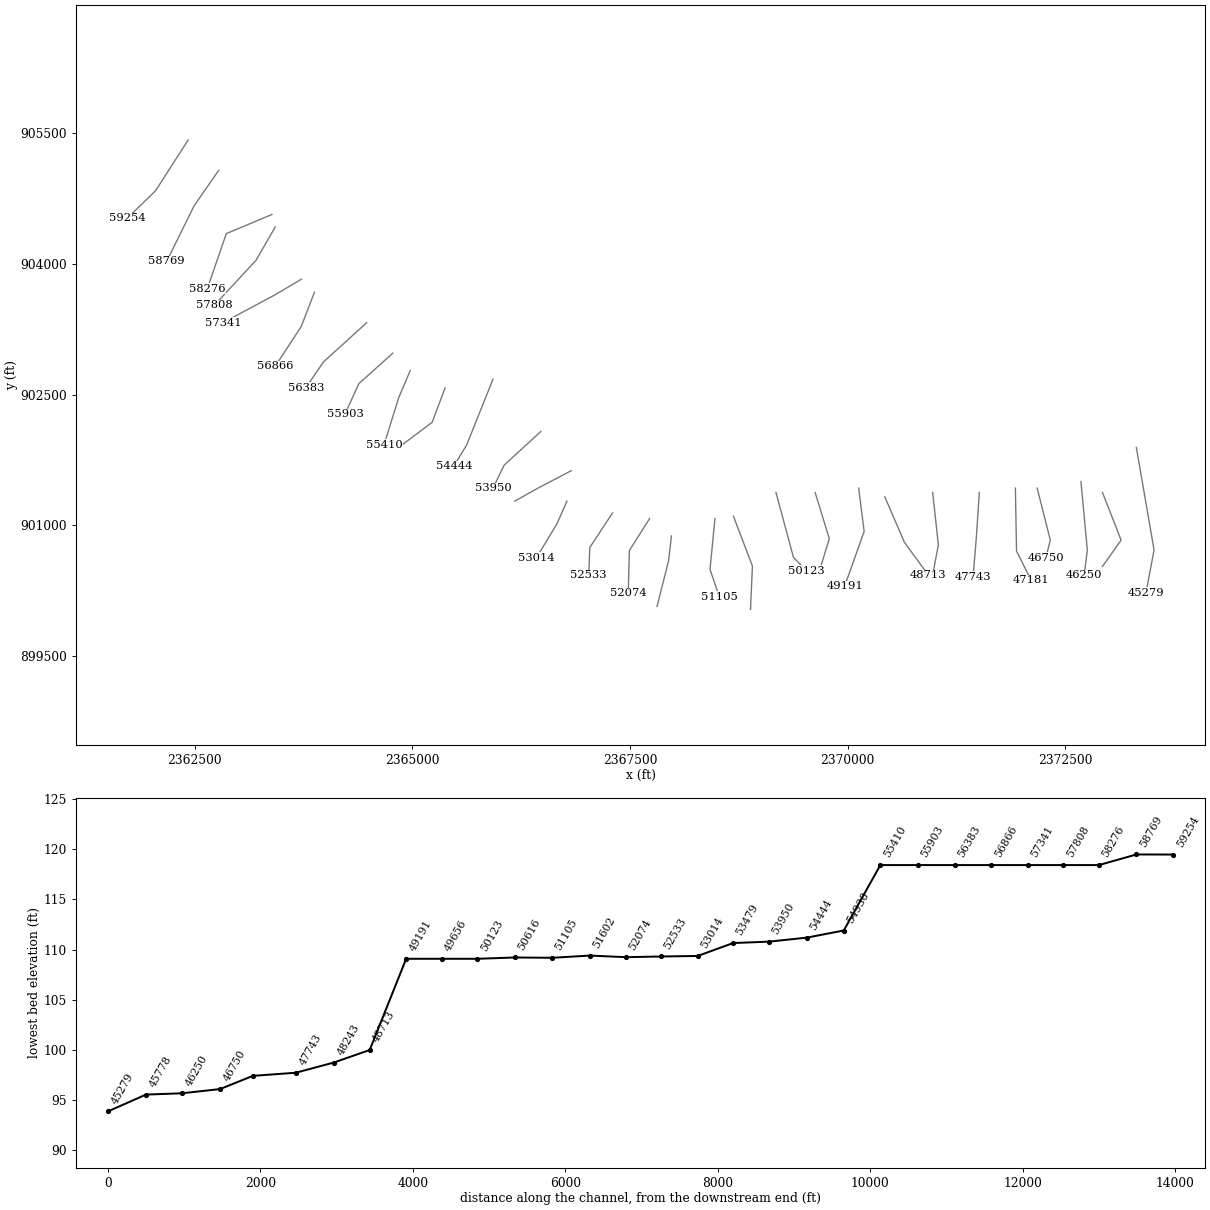
HEC-RAS study BackSwamp.prj: S-16-495 over Back Swamp

--- BackSwamp.g03 (geometry) --- (continued)

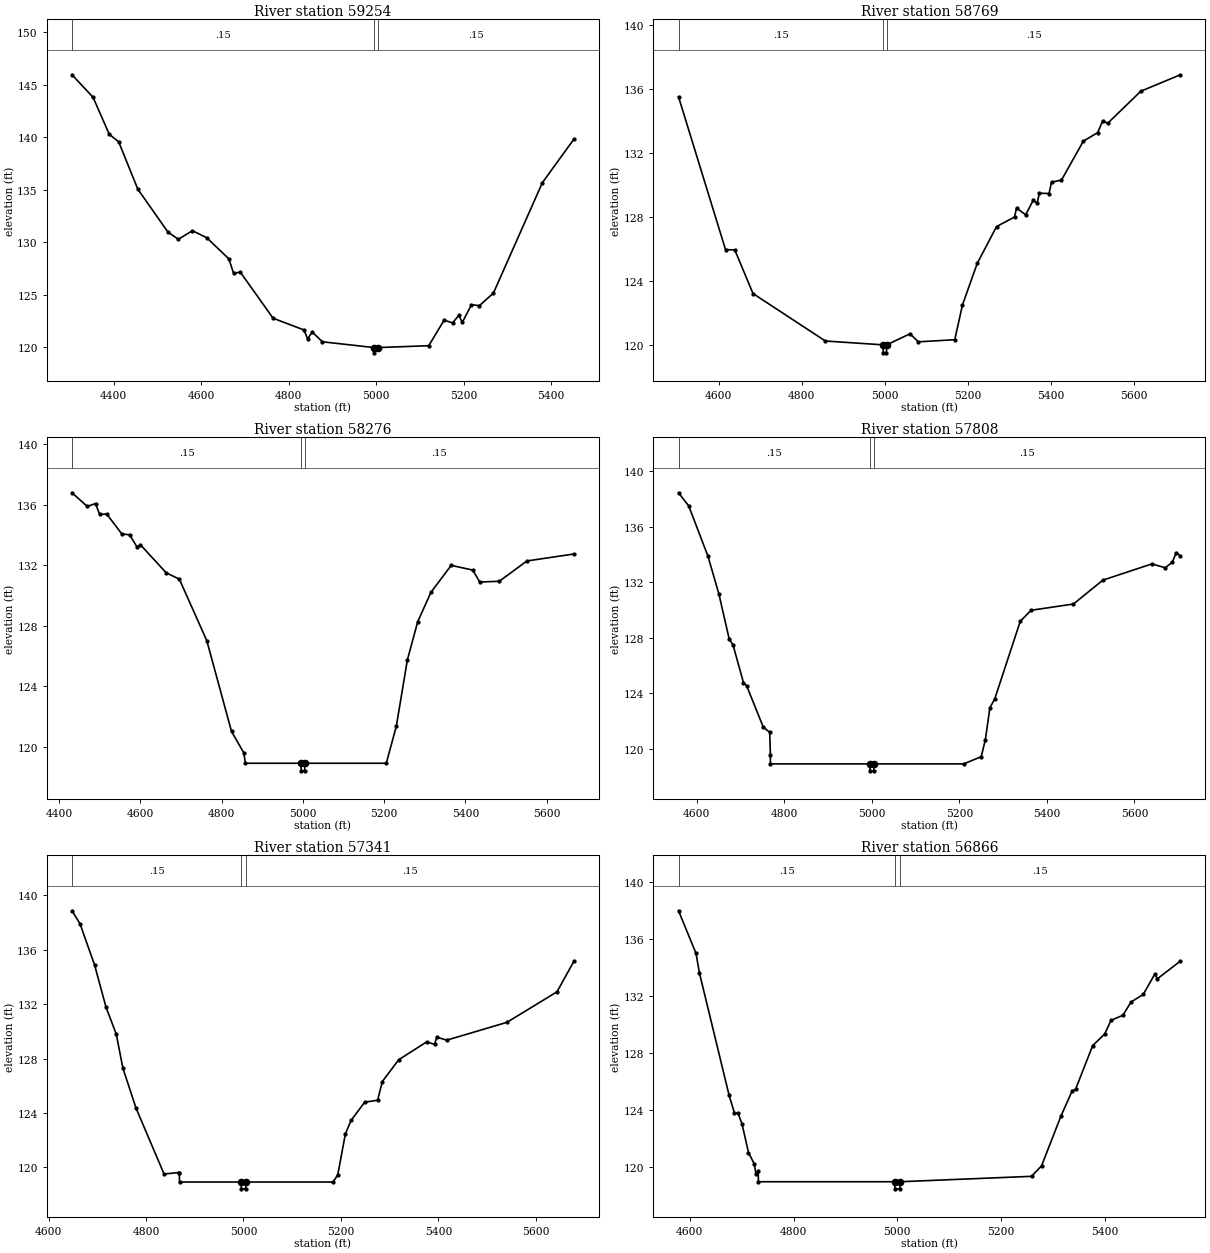
Type RM Length L Ch R = 1 ,59254   ,485,485,485
BEGIN DESCRIPTION:
Back Swamp 98.0
END DESCRIPTION:
XS GIS Cut Line= 3
      2362425.02       905425.04      2362049.43       904840.03
      2361725.01       904525.01
#Sta/Elev= 30
  4304.8  145.94  4352.9  143.79  4389.8  140.28  4411.4  139.56  4455.2  135.05
  4524.2  130.96  4547.9  130.29    4580   131.1  4612.5  130.44  4663.4  128.42
  4674.1  127.05  4689.5  127.16  4764.5  122.77    4835  121.66  4843.5  120.81
  4853.9  121.46  4877.3  120.53  4995.8  119.98  4996.3  119.48  5004.3  119.98
  5120.4  120.16  5155.5  122.59  5174.8  122.33    5189  123.04  5197.2  122.38
    5218  124.06  5236.3  123.97  5268.3  125.17  5380.3  135.68  5452.2  139.81
#Mann= 3 ,-1,0
  4304.8     .15       0  4995.8     .05       0  5004.3     .15       0
Bank Sta=4995.8,5004.3
XS Rating Curve= 0 ,0
Exp/Cntr=0.3,0.1

Type RM Length L Ch R = 1 ,58769   ,493,493,493
BEGIN DESCRIPTION:
Back Swamp 97.0
END DESCRIPTION:
XS GIS Cut Line= 3
      2362774.98       905074.97       2362492.3       904667.17
      2362177.85       904029.93
#Sta/Elev= 30
  4503.8  135.51  4616.8  125.95  4639.1  125.93  4682.9   123.2    4857  120.23
  4995.7  119.99  4996.2  119.49  5003.8  119.49  5004.3  119.99  5060.5  120.68
  5080.5  120.18  5168.1  120.31  5186.7  122.49  5222.2  125.09  5268.6  127.39
  5311.9  127.99  5316.6  128.55  5338.7  128.13  5356.7  129.03  5366.5  128.85
  5371.3  129.48  5394.8  129.46  5400.8  130.17  5424.8   130.3  5477.5  132.74
  5511.8  133.27  5524.1  134.02  5535.7  133.85  5615.5  135.86  5710.6  136.89
#Mann= 3 ,-1,0
  4503.8     .15       0  4995.7     .05       0  5004.3     .15       0
Bank Sta=4995.7,5004.3
XS Rating Curve= 0 ,0
Exp/Cntr=0.3,0.1

Type RM Length L Ch R = 1 ,58276   ,468,468,468
BEGIN DESCRIPTION:
Back Swamp 96.0
END DESCRIPTION:
XS GIS Cut Line= 3
      2363386.36       904568.32      2362862.62         904348.
       2362644.7       903717.49
#Sta/Elev= 30
  4431.8  136.78  4469.2  135.88  4489.5  136.07  4499.6  135.35  4517.1  135.38
  4554.3  134.06  4573.3  134.01  4592.4  133.17  4599.7  133.36  4663.5   131.5
  4695.9  131.08  4763.6  127.01  4824.3  121.03  4854.3  119.63  4858.6  118.93
  4995.3  118.93  4995.8  118.43  5004.3  118.43  5004.8  118.93  5205.3  118.93
    5230  121.37  5257.4  125.77  5282.8  128.28  5315.3  130.21  5365.1  131.99
  5418.1  131.68  5435.5  130.89  5483.6  130.94  5551.5  132.28  5667.1  132.74
#Mann= 3 ,-1,0
  4431.8     .15       0  4995.3     .05       0  5004.8     .15       0
Bank Sta=4995.3,5004.8
XS Rating Curve= 0 ,0
Exp/Cntr=0.3,0.1

Type RM Length L Ch R = 1 ,57808   ,467,467,467
BEGIN DESCRIPTION:
Back Swamp 95.0
END DESCRIPTION:
XS GIS Cut Line= 3
      2363424.99       904424.98      2363203.99       904042.31
      2362725.01       903525.01
#Sta/Elev= 30
  4558.1  138.45  4581.4   137.5  4625.2   133.9  4650.3  131.17  4673.9  127.92
  4682.6   127.5  4706.5  124.78  4713.5  124.57  4751.8  121.58  4766.5   121.2
    4768  119.58  4768.1  118.93  4995.3  118.93  4995.8  118.43  5004.3  118.43
  5004.8  118.93  5209.9  118.93    5250  119.45  5259.4  120.68  5269.7  122.96
    5281  123.63  5339.1  129.19  5363.7  129.99  5460.7  130.44  5527.9  132.16
  5640.1  133.33  5670.6  133.05  5686.7  133.46  5695.8  134.15    5705   133.9
#Mann= 3 ,-1,0
  4558.1     .15       0  4995.3     .05       0  5004.8     .15       0
Bank Sta=4995.3,5004.8
XS Rating Curve= 0 ,0
Exp/Cntr=0.3,0.1

Type RM Length L Ch R = 1 ,57341   ,475,475,475
BEGIN DESCRIPTION:
Back Swamp 94.0
END DESCRIPTION:
XS GIS Cut Line= 3
      2363724.98       903824.99      2363422.45       903645.42
      2362824.96       903324.98
#Sta/Elev= 30
  4648.2  138.87  4664.5  137.91  4694.3   134.9  4717.9  131.78  4738.9   129.8
  4752.5   127.3  4779.7  124.34    4837  119.52  4867.5  119.63  4868.3  119.57
  4868.7  118.93  4995.2  118.93  4995.7  118.43  5004.4  118.43  5004.9  118.93
  5183.9  118.93  5193.5  119.47  5209.1  122.47  5220.8  123.46  5248.7   124.8
  5275.2  124.94    5285  126.32  5318.5  127.92  5375.9  129.23  5392.2  129.05
  5396.5  129.58  5417.2  129.36  5540.7  130.67  5643.3  132.91    5678  135.15
#Mann= 3 ,-1,0
  4648.2     .15       0  4995.2     .05       0  5004.9     .15       0
Bank Sta=4995.2,5004.9
XS Rating Curve= 0 ,0
Exp/Cntr=0.3,0.1

Type RM Length L Ch R = 1 ,56866   ,483,483,483
BEGIN DESCRIPTION:
Back Swamp 93.0
END DESCRIPTION:
XS GIS Cut Line= 3
      2363874.98       903674.96      2363723.38       903281.45
      2363425.01       902825.02
#Sta/Elev= 30
  4578.3  137.99    4612  134.99  4618.5  133.63  4675.6  125.03  4685.9  123.78
  4693.1  123.75  4700.9  122.96  4713.1  120.98  4723.9  120.21  4727.7  119.47
  4731.9  119.71  4732.2  118.93  4994.7  118.93  4995.2  118.43  5004.8  118.43
  5005.3  118.93  5258.5  119.31  5277.9  120.05  5315.4  123.56  5336.4  125.28
  5343.5  125.44  5376.4  128.51  5399.3  129.31  5411.8  130.28  5434.6  130.64
  5450.3  131.57  5473.9  132.11  5496.2  133.54  5500.9   133.2  5545.3  134.45
#Mann= 3 ,-1,0
  4578.3     .15       0  4994.7     .05       0  5005.3     .15       0
Bank Sta=4994.7,5005.3
XS Rating Curve= 0 ,0
Exp/Cntr=0.3,0.1

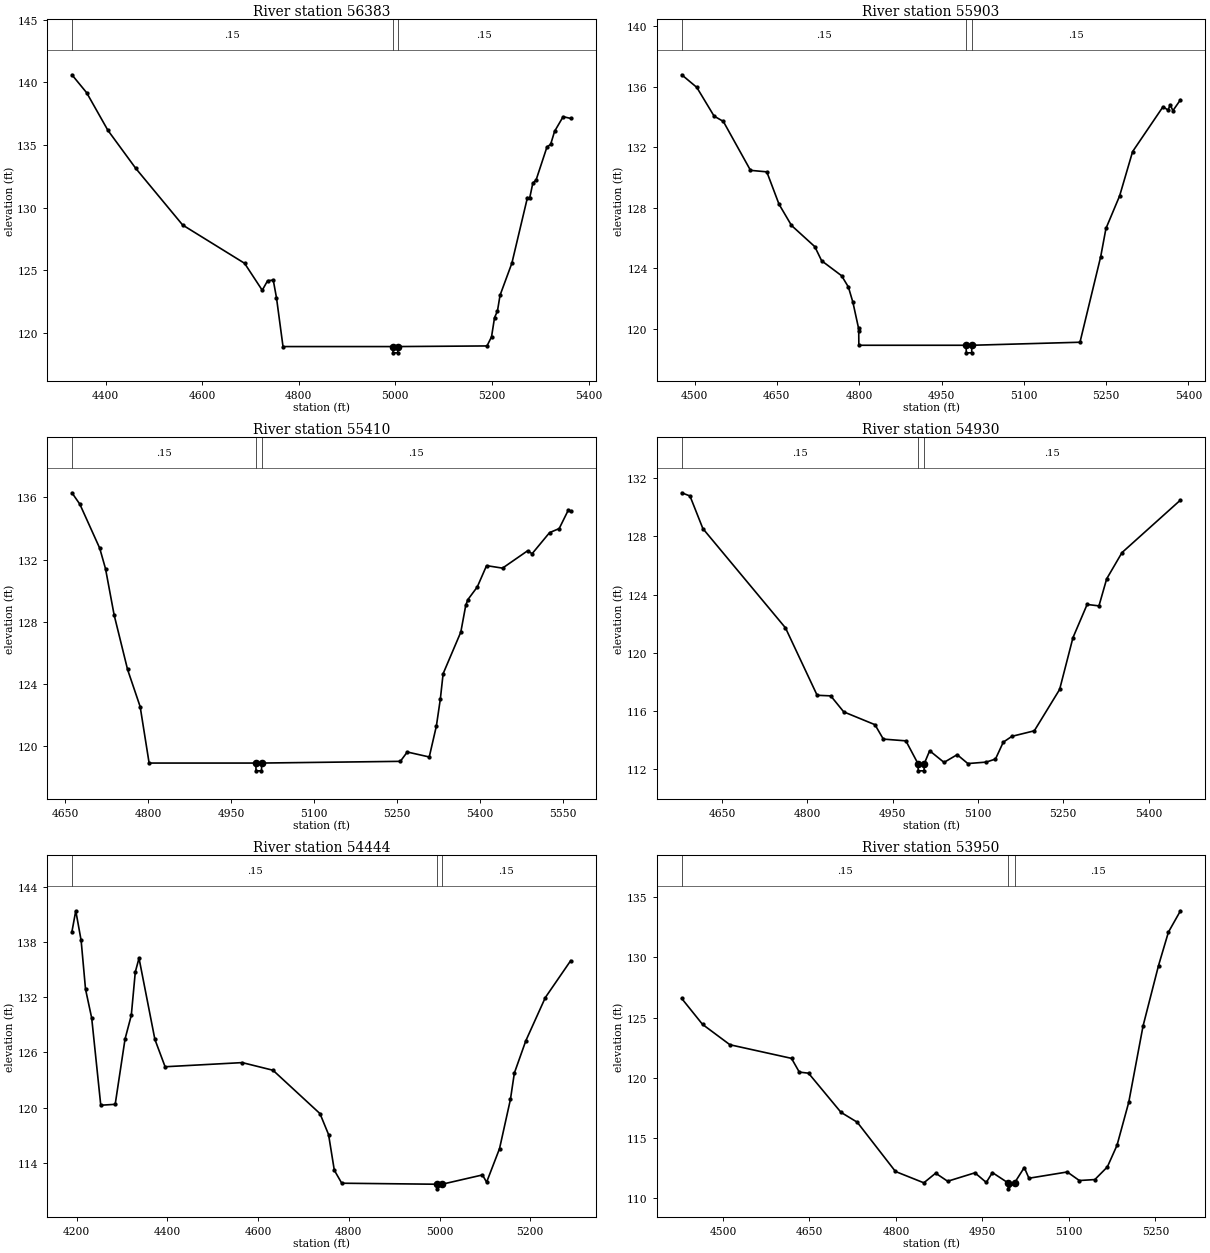
Type RM Length L Ch R = 1 ,56383   ,480,480,480
BEGIN DESCRIPTION:
Back Swamp 92.0
END DESCRIPTION:
XS GIS Cut Line= 3
      2364475.01       903325.01      2363979.12       902875.05
        2363775.         902575.
#Sta/Elev= 30
  4330.4   140.6  4360.9  139.17  4404.9  136.17  4462.5  133.14  4559.7  128.62
  4687.8  125.57  4724.4  123.42  4735.5  124.18  4747.2  124.23  4753.9  122.82
  4767.4  118.93  4994.7  118.93  4995.2  118.43  5004.8  118.43  5005.3  118.93
  5189.7  118.98  5199.1  119.71  5205.3  121.24  5211.3  121.76  5216.7  123.02
  5241.2  125.58  5273.4  130.81  5278.1  130.78  5284.5  131.95  5291.4  132.22
  5313.8  134.84  5321.5  135.06  5329.6  136.09  5347.3  137.26  5362.9  137.12
#Mann= 3 ,-1,0
  4330.4     .15       0  4994.7     .05       0  5005.3     .15       0
Bank Sta=4994.7,5005.3
XS Rating Curve= 0 ,0
Exp/Cntr=0.3,0.1

Type RM Length L Ch R = 1 ,55903   ,493,493,493
BEGIN DESCRIPTION:
Back Swamp 91.0
END DESCRIPTION:
XS GIS Cut Line= 3
      2364774.98       902974.98      2364385.51       902625.47
      2364225.03       902275.07
#Sta/Elev= 30
  4476.7  136.79  4504.1  135.96  4535.7  134.06  4552.5  133.71    4602  130.48
  4631.7  130.38    4654  128.24  4676.7  126.84  4719.2  125.44  4731.6  124.51
    4768  123.52  4780.3  122.78  4788.5  121.78  4798.9  120.05  4799.2  119.86
  4799.4  118.93  4994.7  118.93  4995.2  118.43  5004.9  118.43  5005.4  118.93
  5202.3  119.13  5240.1  124.79  5249.6  126.64  5274.5  128.79  5298.2  131.72
  5353.6  134.68  5362.7  134.46  5366.7   134.8  5371.6  134.42  5385.4  135.14
#Mann= 3 ,-1,0
  4476.7     .15       0  4994.7     .05       0  5005.4     .15       0
Bank Sta=4994.7,5005.4
XS Rating Curve= 0 ,0
Exp/Cntr=0.3,0.1

Type RM Length L Ch R = 1 ,55410   ,480,480,480
BEGIN DESCRIPTION:
Back Swamp 90.0
END DESCRIPTION:
XS GIS Cut Line= 3
      2364975.01       902775.02      2364842.66        902463.9
      2364674.99       901924.98
#Sta/Elev= 30
  4661.9  136.29  4676.2  135.56  4712.2  132.73  4722.7  131.41  4738.3  128.44
  4762.6  124.94  4785.4  122.55  4801.6  118.93  4994.6  118.93  4995.1  118.43
  5004.9  118.43  5005.4  118.93  5256.2  119.04  5268.7  119.64  5308.5  119.32
  5321.4  121.31  5328.6  123.05  5333.6  124.67  5365.6  127.34  5374.5  129.05
  5378.2  129.42  5395.4  130.24  5412.2  131.61  5441.1  131.45  5486.3  132.56
  5494.7  132.38  5526.2  133.73  5543.6  133.99    5560  135.17  5564.4  135.11
#Mann= 3 ,-1,0
  4661.9     .15       0  4994.6     .05       0  5005.4     .15       0
Bank Sta=4994.6,5005.4
XS Rating Curve= 0 ,0
Exp/Cntr=0.3,0.1

Type RM Length L Ch R = 1 ,54930   ,486,486,486
BEGIN DESCRIPTION:
Back Swamp 89.0
END DESCRIPTION:
XS GIS Cut Line= 3
        2365375.       902574.99      2365226.73       902180.86
      2364862.17       901906.61
#Sta/Elev= 30
  4578.9     131  4593.4  130.78  4616.1  128.54  4761.4  121.72  4817.1  117.09
    4841  117.05  4863.9  115.95  4918.8  115.07  4933.5  114.08  4973.2  113.96
  4994.4   112.4  4994.9   111.9  5005.1   111.9  5005.6   112.4    5015  113.28
  5040.3  112.48  5063.4  113.01  5082.2   112.4  5114.5   112.5  5130.8  112.71
  5144.5  113.87  5159.7  114.27  5199.1  114.65  5243.6  117.49  5267.1  121.05
    5292  123.33  5312.8  123.23  5326.4  125.09  5353.3  126.89  5456.2   130.5
#Mann= 3 ,-1,0
  4578.9     .15       0  4994.4     .05       0  5005.6     .15       0
Bank Sta=4994.4,5005.6
XS Rating Curve= 0 ,0
Exp/Cntr=0.3,0.1

Type RM Length L Ch R = 1 ,54444   ,494,494,494
BEGIN DESCRIPTION:
Back Swamp 88.0
END DESCRIPTION:
XS GIS Cut Line= 3
        2365925.       902675.01      2365624.09       901922.65
      2365474.98       901674.97
#Sta/Elev= 30
  4189.7  139.11  4198.2  141.39    4210  138.17  4219.7  132.87  4233.3  129.74
  4253.3  120.27  4285.1  120.37  4306.8  127.46  4320.6  130.04  4329.4  134.74
  4337.6  136.24  4372.6  127.42  4395.1  124.45  4565.1   124.9  4632.9  124.07
  4736.5  119.36  4755.4  117.09  4768.1  113.21  4784.5   111.8  4994.4  111.69
  4994.9  111.19  5005.6  111.69  5094.7   112.7  5103.8  111.91  5132.3  115.56
  5156.3   120.9    5165  123.77  5190.3  127.28  5233.3  131.97  5289.1  135.97
#Mann= 3 ,-1,0
  4189.7     .15       0  4994.4     .05       0  5005.6     .15       0
Bank Sta=4994.4,5005.6
XS Rating Curve= 0 ,0
Exp/Cntr=0.3,0.1

Type RM Length L Ch R = 1 ,53950   ,471,471,471
BEGIN DESCRIPTION:
Back Swamp 87.0
END DESCRIPTION:
XS GIS Cut Line= 3
        2366475.         902075.      2366053.79       901688.75
        2365925.       901425.01
#Sta/Elev= 30
  4428.5  126.59  4464.6  124.44  4512.1  122.75  4618.9  121.62  4632.4  120.48
  4648.4  120.39  4704.7  117.14  4732.9  116.32  4799.2  112.23  4848.4  111.29
  4868.9  112.09  4889.7  111.42    4937  112.12  4956.7  111.32  4967.3  112.14
  4994.3  111.29  4994.8  110.79  5005.8  111.29  5022.6  112.56  5030.7  111.67
  5097.1  112.19  5118.1  111.48    5145  111.56  5166.7  112.61  5183.4   114.4
  5203.8  117.98  5228.6  124.31  5255.4  129.32  5272.6   132.1  5293.5  133.87
#Mann= 3 ,-1,0
  4428.5     .15       0  4994.3     .05       0  5005.8     .15       0
Bank Sta=4994.3,5005.8
XS Rating Curve= 0 ,0
Exp/Cntr=0.3,0.1

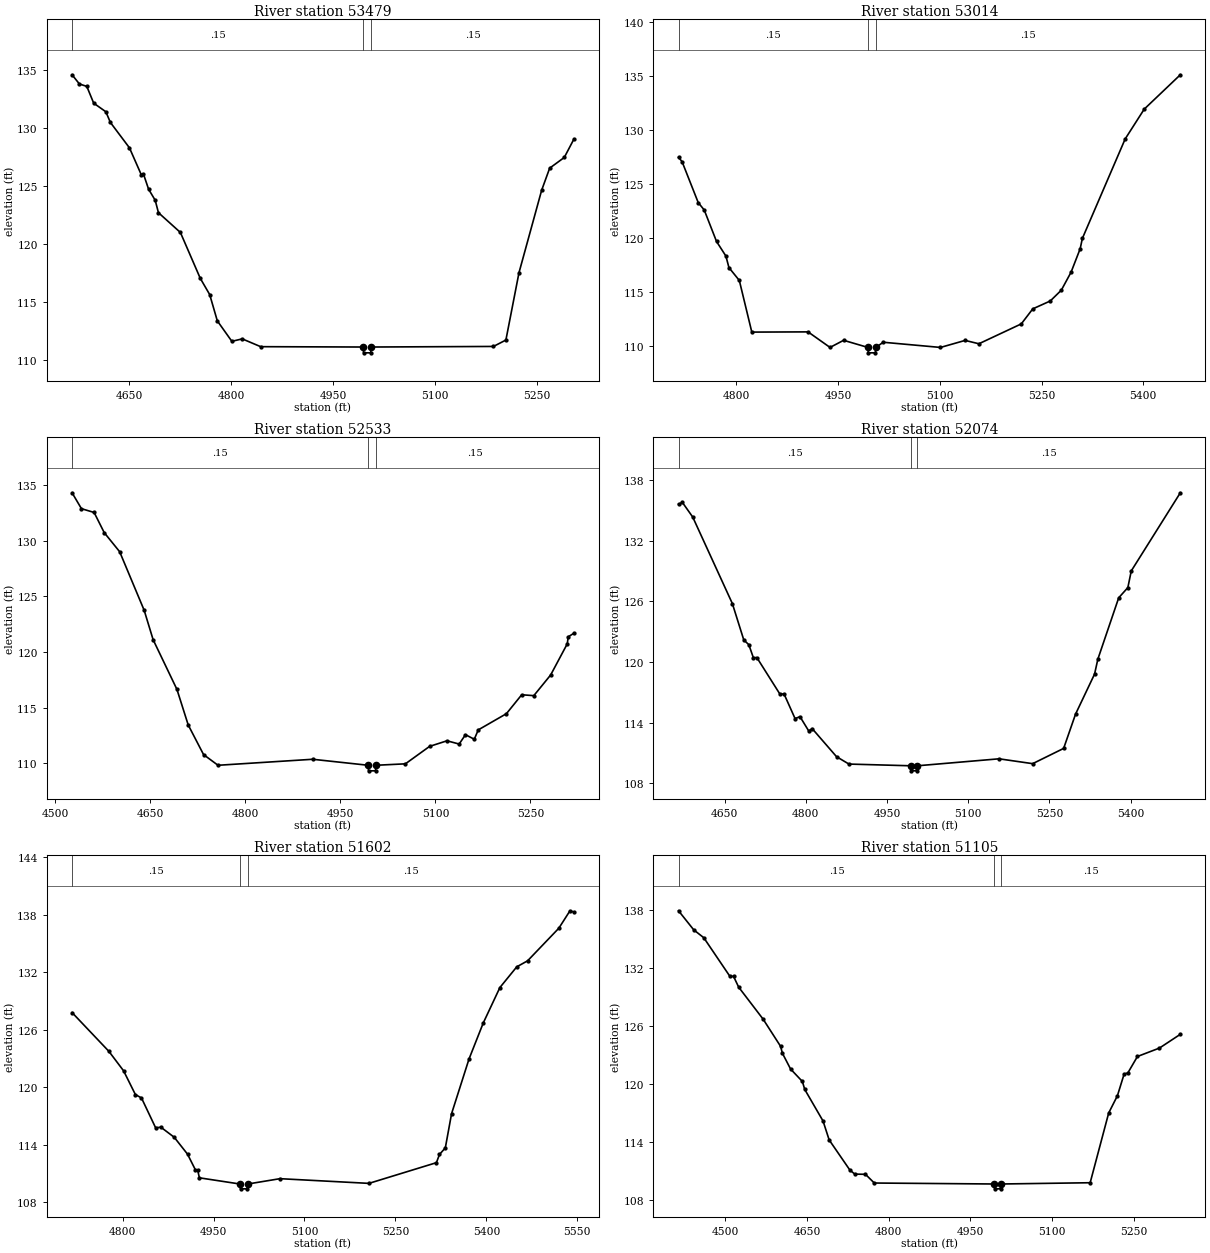
Type RM Length L Ch R = 1 ,53479   ,465,465,465
BEGIN DESCRIPTION:
Back Swamp 86.0
END DESCRIPTION:
XS GIS Cut Line= 3
      2366824.99         901625.       2366440.4       901423.68
        2366175.         901275.
#Sta/Elev= 30
  4565.9  134.56  4576.7  133.77  4587.6  133.56  4597.7  132.12  4615.6  131.38
  4622.3  130.46  4650.3  128.28  4667.7  125.97  4670.8  126.05  4678.5  124.72
  4688.2  123.77    4693   122.7  4725.3     121  4754.5  117.06  4768.4  115.66
  4779.6   113.4    4801  111.64  4816.3  111.85  4843.4  111.18  4994.3  111.15
  4994.8  110.65  5005.3  110.65  5005.8  111.15  5185.9   111.2  5204.2  111.75
  5223.5  117.55  5256.8  124.63  5268.6  126.53  5290.1  127.45  5304.2  129.02
#Mann= 3 ,-1,0
  4565.9     .15       0  4994.3     .05       0  5005.8     .15       0
Bank Sta=4994.3,5005.8
XS Rating Curve= 0 ,0
Exp/Cntr=0.3,0.1

Type RM Length L Ch R = 1 ,53014   ,481,481,481
BEGIN DESCRIPTION:
Back Swamp 85.0
END DESCRIPTION:
XS GIS Cut Line= 3
        2366775.       901275.01      2366659.79       901014.33
      2366425.03       900625.04
#Sta/Elev= 30
    4715  127.46  4720.2  127.06    4744  123.27  4752.9  122.58    4771  119.67
  4784.8  118.32  4789.3  117.25  4804.6  116.06    4823  111.28  4905.9   111.3
  4938.3  109.86  4958.3  110.52  4994.2  109.86  4994.7  109.36  5005.3  109.36
  5005.8  109.86  5016.7  110.34  5101.1  109.86  5137.4  110.51  5157.7   110.2
  5220.2  112.04  5237.1  113.43  5262.9  114.16  5279.2  115.16  5293.6  116.83
    5307     119  5310.2  119.95  5373.3  129.16  5401.4  131.92  5454.6   135.1
#Mann= 3 ,-1,0
    4715     .15       0  4994.2     .05       0  5005.8     .15       0
Bank Sta=4994.2,5005.8
XS Rating Curve= 0 ,0
Exp/Cntr=0.3,0.1

Type RM Length L Ch R = 1 ,52533   ,459,459,459
BEGIN DESCRIPTION:
Back Swamp 84.0
END DESCRIPTION:
XS GIS Cut Line= 3
      2367297.98       901138.57      2367037.69       900743.28
        2367025.       900425.03
#Sta/Elev= 30
  4526.7  134.31  4541.5  132.88  4561.5  132.54  4577.4  130.73  4601.8  129.01
  4640.5  123.74  4654.6   121.1  4692.2  116.63    4710  113.43  4734.2  110.77
    4757  109.81  4906.4  110.35    4994  109.81  4994.5  109.31  5005.5  109.31
    5006  109.81  5052.7  109.94  5090.9  111.51  5118.3  112.01  5137.5  111.72
  5147.5  112.56  5161.4  112.15  5167.6  112.99  5212.1  114.45  5236.2  116.15
  5255.3  116.07  5281.9  117.93  5308.1  120.73  5309.6  121.36  5318.5  121.68
#Mann= 3 ,-1,0
  4526.7     .15       0    4994     .05       0    5006     .15       0
Bank Sta=4994,5006
XS Rating Curve= 0 ,0
Exp/Cntr=0.3,0.1

Type RM Length L Ch R = 1 ,52074   ,472,472,472
BEGIN DESCRIPTION:
Back Swamp 83.0
END DESCRIPTION:
XS GIS Cut Line= 3
      2367724.97       901074.96      2367491.83       900707.83
       2367478.7       900216.21
#Sta/Elev= 30
  4565.1  135.62  4572.3  135.79  4591.3  134.35  4664.5  125.79  4685.6  122.19
  4694.9  121.72  4703.2  120.45  4709.8  120.44    4752  116.86  4760.1  116.83
  4780.3  114.41  4789.4   114.6  4805.6  113.18  4811.9  113.42  4856.9  110.64
  4879.8  109.91    4994  109.74  4994.5  109.24  5005.6  109.24  5006.1  109.74
    5157  110.43  5219.1  109.95  5276.3  111.46  5298.3  114.85  5333.4  118.81
  5339.5  120.29    5378  126.36  5394.9  127.37  5401.2  129.02  5491.8  136.75
#Mann= 3 ,-1,0
  4565.1     .15       0    4994     .05       0  5006.1     .15       0
Bank Sta=4994,5006.1
XS Rating Curve= 0 ,0
Exp/Cntr=0.3,0.1

Type RM Length L Ch R = 1 ,51602   ,497,497,497
BEGIN DESCRIPTION:
Back Swamp 82.0
END DESCRIPTION:
XS GIS Cut Line= 3
        2367975.       900874.99      2367942.63       900593.54
      2367810.01       900065.65
#Sta/Elev= 30
  4716.7  127.79  4777.5  123.74  4801.7  121.71  4821.1  119.24  4831.2  118.88
  4854.5  115.77  4863.2  115.83  4885.2  114.78  4907.1  113.02  4920.2  111.37
  4923.9  111.33  4926.7  110.55    4994   109.9  4994.5   109.4  5005.6   109.4
  5006.1   109.9  5059.6  110.46  5206.3  109.97  5317.6  112.13  5322.7  112.99
  5332.3  113.67  5342.6  117.24  5371.4  122.95  5394.9  126.71  5422.3   130.4
  5450.1  132.56    5468  133.19  5519.5  136.59  5537.9  138.41  5544.3  138.28
#Mann= 3 ,-1,0
  4716.7     .15       0    4994     .05       0  5006.1     .15       0
Bank Sta=4994,5006.1
XS Rating Curve= 0 ,0
Exp/Cntr=0.3,0.1

Type RM Length L Ch R = 1 ,51105   ,489,489,489
BEGIN DESCRIPTION:
Back Swamp 81.0
END DESCRIPTION:
XS GIS Cut Line= 3
        2368475.       901074.98      2368417.68        900492.3
      2368525.02       900174.96
#Sta/Elev= 30
  4414.5  137.88  4442.4  135.91  4460.8   135.1  4508.4  131.14  4515.5   131.1
  4524.9  129.99  4569.7  126.69  4601.7  123.89    4605  123.18    4620  121.55
  4641.7  120.26    4646  119.44  4679.6  116.18  4690.8  114.23  4728.9  111.11
  4737.9   110.7  4757.4  110.68  4773.6  109.78  4993.9  109.68  4994.4  109.18
  5005.7  109.18  5006.2  109.68  5169.6  109.81  5203.6  117.01  5219.6  118.79
  5231.9  121.03  5238.7  121.14  5256.3  122.84  5296.7  123.71    5335  125.13
#Mann= 3 ,-1,0
  4414.5     .15       0  4993.9     .05       0  5006.2     .15       0
Bank Sta=4993.9,5006.2
XS Rating Curve= 0 ,0
Exp/Cntr=0.3,0.1

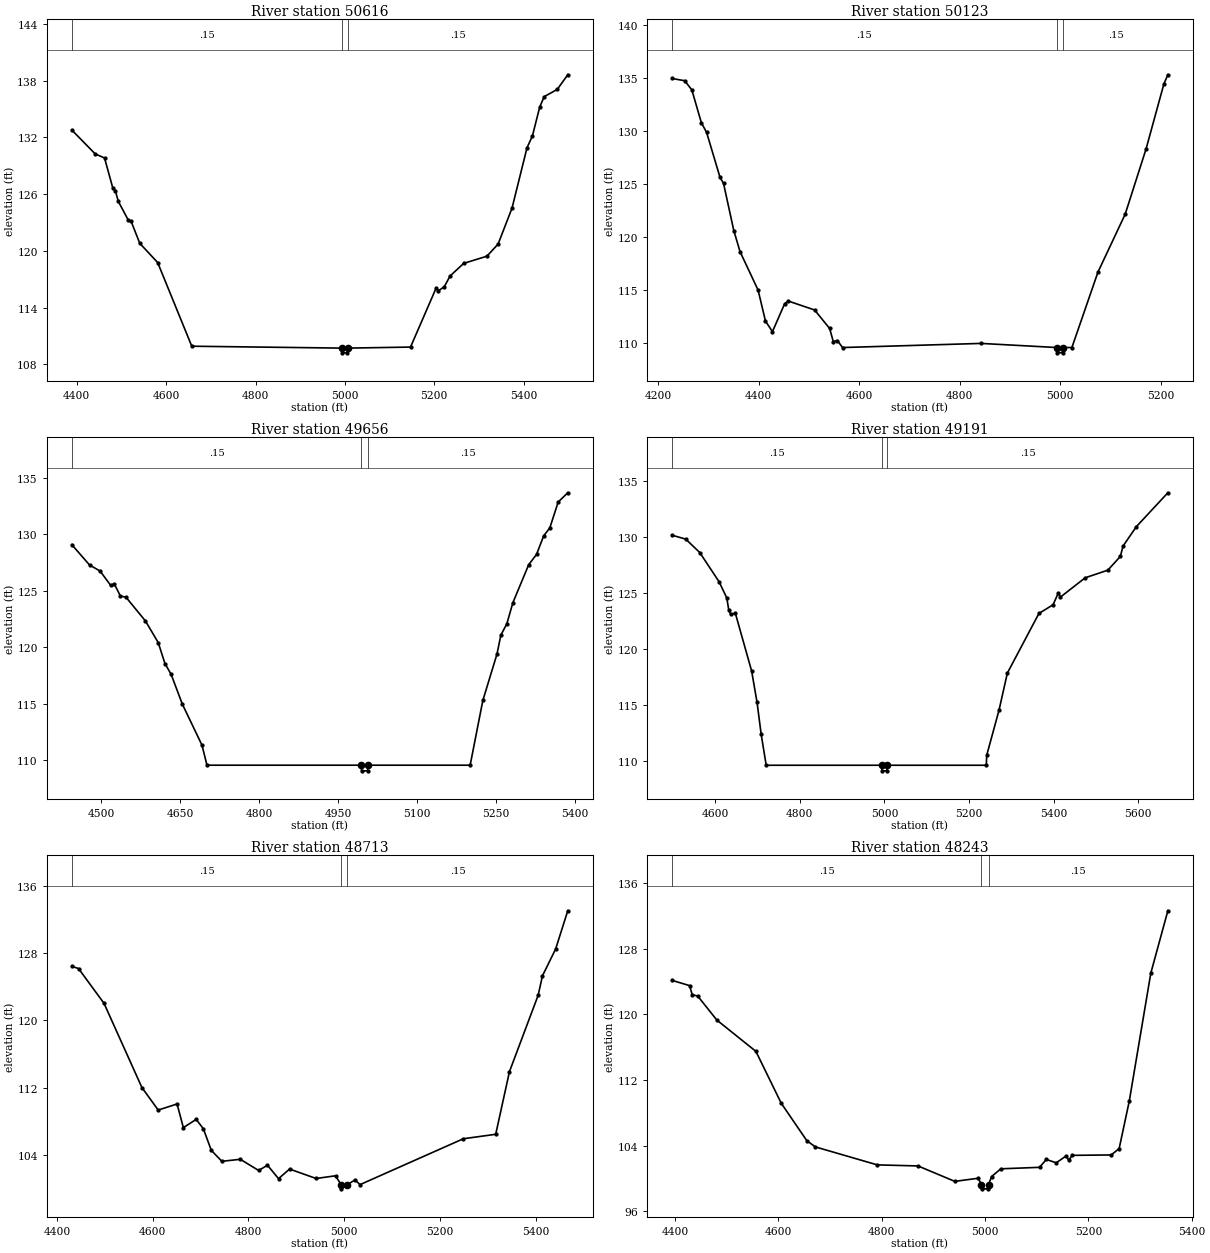
Type RM Length L Ch R = 1 ,50616   ,493,493,493
BEGIN DESCRIPTION:
Back Swamp 80.0
END DESCRIPTION:
XS GIS Cut Line= 3
      2368687.19       901100.97      2368904.94       900529.98
      2368882.97       900031.76
#Sta/Elev= 30
  4388.9  132.78  4441.3  130.25  4462.2  129.82  4480.5  126.68  4486.3  126.38
  4492.9  125.24  4515.4  123.24  4521.4  123.15  4541.1  120.79  4581.1  118.76
  4657.4  109.91  4993.8  109.71  4994.3  109.21  5005.7  109.21  5006.2  109.71
  5146.9  109.82  5204.5   116.1    5209  115.76  5222.6  116.21  5235.2  117.33
  5265.7  118.67  5317.7  119.43  5342.8  120.71    5374  124.52  5407.5   130.9
  5419.6  132.15  5435.9   135.2    5446  136.31  5475.1  137.07  5498.7  138.62
#Mann= 3 ,-1,0
  4388.9     .15       0  4993.8     .05       0  5006.2     .15       0
Bank Sta=4993.8,5006.2
XS Rating Curve= 0 ,0
Exp/Cntr=0.3,0.1

Type RM Length L Ch R = 1 ,50123   ,467,467,467
BEGIN DESCRIPTION:
Back Swamp 79.0
END DESCRIPTION:
XS GIS Cut Line= 3
        2369175.       901374.99      2369376.21       900629.25
      2369524.99       900475.01
#Sta/Elev= 30
  4227.6  134.99    4253  134.78  4267.3  133.92  4286.3  130.81  4296.7   129.9
  4323.4  125.65  4330.4  125.08  4350.8  120.63  4363.2  118.64  4399.2     115
  4413.8  112.08  4427.7  111.08  4451.9  113.71  4459.2  113.97  4511.5  113.13
  4541.5  111.38  4548.7  110.15    4557  110.24  4567.1  109.58  4842.7  109.97
  4993.8  109.58  4994.3  109.08  5005.8  109.08  5006.3  109.58  5023.4  109.58
  5075.3  116.71  5129.4  122.17  5170.8  128.31  5206.4  134.47  5214.3  135.34
#Mann= 3 ,-1,0
  4227.6     .15       0  4993.8     .05       0  5006.3     .15       0
Bank Sta=4993.8,5006.3
XS Rating Curve= 0 ,0
Exp/Cntr=0.3,0.1

Type RM Length L Ch R = 1 ,49656   ,465,465,465
BEGIN DESCRIPTION:
Back Swamp 78.0
END DESCRIPTION:
XS GIS Cut Line= 3
        2369625.       901375.01      2369788.19       900843.71
        2369675.         900475.
#Sta/Elev= 30
  4444.2   129.1  4477.9   127.3    4498  126.76  4517.9   125.5  4524.9  125.62
  4536.4  124.56  4547.2  124.44  4584.1  122.34  4608.3  120.43  4621.1  118.57
  4632.7  117.63  4654.1  114.98  4691.4  111.35  4700.8  109.58  4993.8  109.58
  4994.3  109.08  5005.8  109.08  5006.3  109.58  5200.4  109.58  5224.5  115.31
  5251.3  119.41  5258.7  121.09  5270.1   122.1  5281.5  123.96  5311.6  127.33
  5326.5  128.24    5340  129.88  5351.6  130.58  5367.5  132.87  5385.7  133.69
#Mann= 3 ,-1,0
  4444.2     .15       0  4993.8     .05       0  5006.3     .15       0
Bank Sta=4993.8,5006.3
XS Rating Curve= 0 ,0
Exp/Cntr=0.3,0.1

Type RM Length L Ch R = 1 ,49191   ,478,478,478
BEGIN DESCRIPTION:
Back Swamp 77.0
END DESCRIPTION:
XS GIS Cut Line= 3
        2370125.       901425.02      2370188.02       900926.59
      2369963.46       900295.24
#Sta/Elev= 30
  4497.6  130.15  4530.3   129.8  4563.5   128.6  4609.3  125.98  4627.4  124.54
    4632  123.49  4636.5  123.08  4647.7  123.17  4686.2     118    4699   115.2
  4708.8  112.33  4720.6  109.58  4993.6  109.58  4994.1  109.08    5006  109.08
  5006.5  109.58  5240.8  109.58  5242.1   110.5  5271.1  114.52  5290.7  117.82
  5365.3  123.15  5398.8  123.93  5411.5  125.01    5416  124.61  5474.7  126.34
  5528.2  127.02  5557.8  128.25  5564.3  129.18  5595.6  130.91  5670.1  133.94
#Mann= 3 ,-1,0
  4497.6     .15       0  4993.6     .05       0  5006.5     .15       0
Bank Sta=4993.6,5006.5
XS Rating Curve= 0 ,0
Exp/Cntr=0.3,0.1

Type RM Length L Ch R = 1 ,48713   ,470,470,470
BEGIN DESCRIPTION:
Back Swamp 76.0
END DESCRIPTION:
XS GIS Cut Line= 3
      2370425.01       901324.99      2370650.27       900802.47
      2370925.02       900424.97
#Sta/Elev= 30
    4431  126.41  4445.1  126.15  4498.4  122.01  4577.5  112.01  4611.5  109.34
  4650.9  110.06    4664  107.25  4690.8  108.23  4705.8  107.12  4722.4  104.55
  4744.5  103.25    4783  103.49  4821.3  102.16  4839.7  102.79  4862.8  101.19
  4885.9  102.33  4941.3  101.21  4981.8  101.53  4993.5  100.48    4994   99.98
  5006.5  100.48  5022.6  101.04    5033  100.48  5248.8  105.93  5316.4  106.46
  5345.1   113.9  5405.1  122.98    5414  125.28  5441.5  128.46  5466.9  133.01
#Mann= 3 ,-1,0
    4431     .15       0  4993.5     .05       0  5006.5     .15       0
Bank Sta=4993.5,5006.5
XS Rating Curve= 0 ,0
Exp/Cntr=0.3,0.1

Type RM Length L Ch R = 1 ,48243   ,500,500,500
BEGIN DESCRIPTION:
Back Swamp 75.0
END DESCRIPTION:
XS GIS Cut Line= 3
        2370975.         901375.      2371040.26       900772.72
        2370975.       900424.99
#Sta/Elev= 30
  4394.2  124.14  4428.5  123.49  4433.6  122.38  4444.1  122.23  4481.3  119.29
  4556.8  115.48  4605.8  109.16  4655.3   104.6  4671.8  103.84  4791.6  101.65
  4870.4  101.52  4941.6   99.64  4986.9  100.02  4993.2   99.23  4993.7   98.73
  5006.4   98.73  5006.9   99.23  5012.8  100.23  5030.7  101.17  5105.5  101.35
  5118.7  102.31  5137.9   101.9  5156.8  102.73    5162  102.21  5168.7  102.81
  5244.3  102.86  5259.6  103.64  5279.2  109.43  5320.8     125  5353.8  132.61
#Mann= 3 ,-1,0
  4394.2     .15       0  4993.2     .05       0  5006.9     .15       0
Bank Sta=4993.2,5006.9
XS Rating Curve= 0 ,0
Exp/Cntr=0.3,0.1

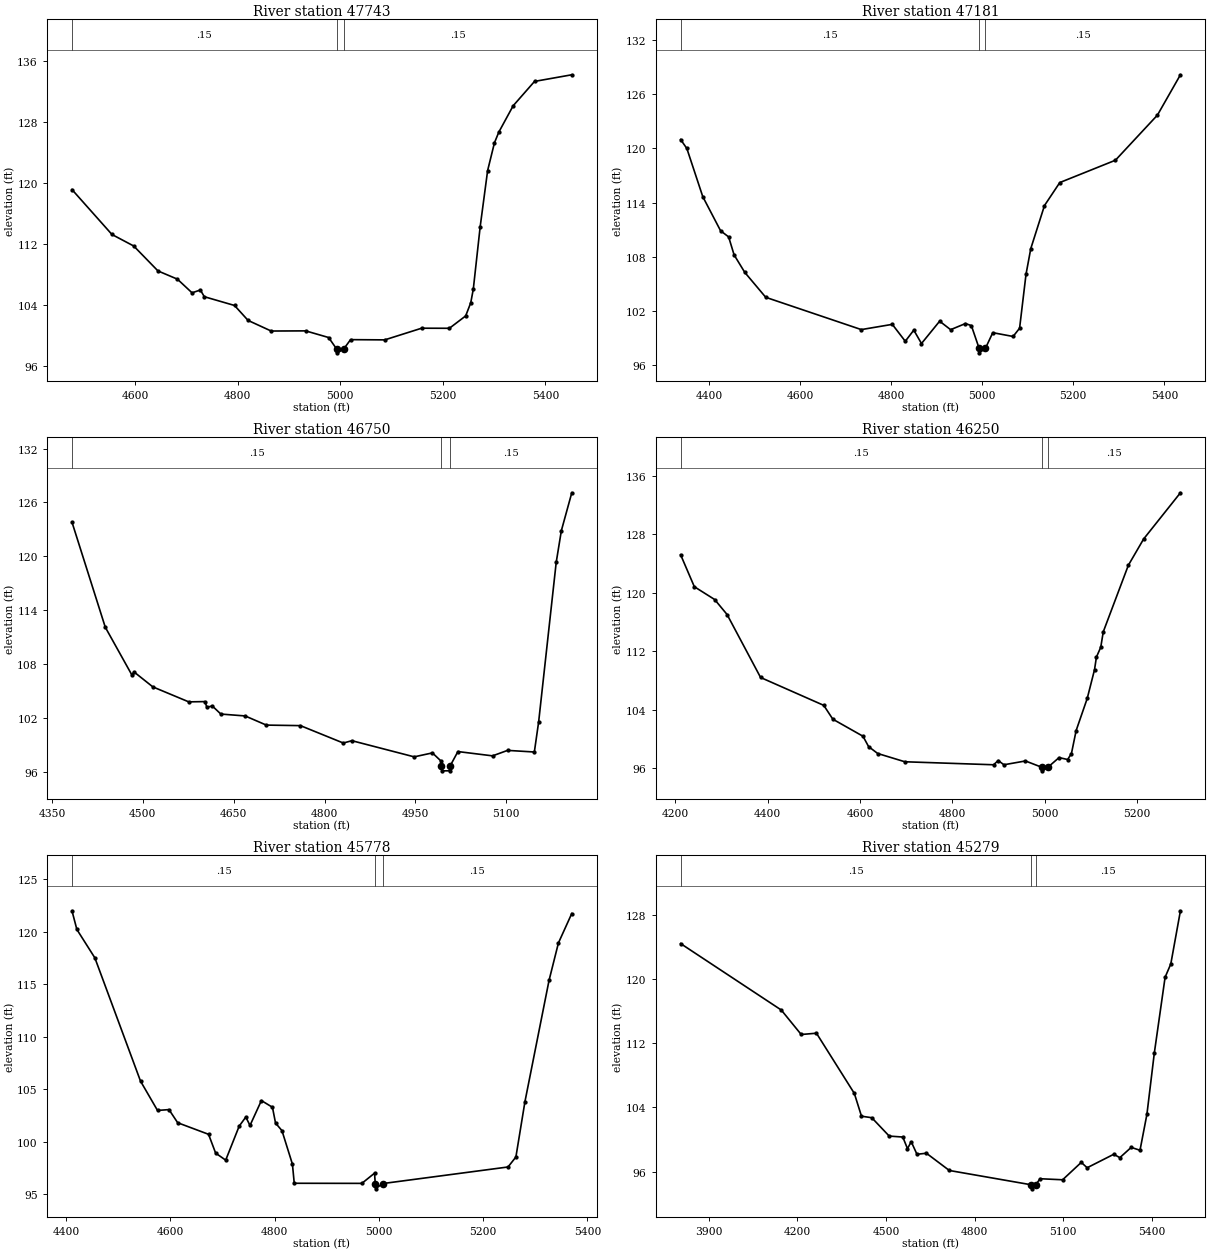
Type RM Length L Ch R = 1 ,47743   ,562,562,562
BEGIN DESCRIPTION:
Back Swamp 74.0
END DESCRIPTION:
XS GIS Cut Line= 3
       2371510.8       901375.76      2371476.39       900854.29
      2371439.27       900404.42
#Sta/Elev= 30
  4477.4  119.12  4555.3  113.23  4597.7  111.72    4645  108.45  4682.9  107.37
  4711.4  105.58  4727.6  105.95  4735.3  105.07  4794.2  103.92  4820.6  101.96
  4865.6  100.57  4932.8  100.59  4977.5   99.72  4993.2   98.21  4993.7   97.71
  5006.9   98.21  5020.3   99.44  5086.9   99.41  5158.8  100.94  5212.9  100.93
  5244.6  102.55  5254.5  104.27  5259.5  106.07  5272.9  114.26  5287.4  121.61
  5300.7  125.25  5309.2  126.65  5337.2  130.11  5378.8   133.3  5451.4  134.17
#Mann= 3 ,-1,0
  4477.4     .15       0  4993.2     .05       0  5006.9     .15       0
Bank Sta=4993.2,5006.9
XS Rating Curve= 0 ,0
Exp/Cntr=0.3,0.1

Type RM Length L Ch R = 1 ,47181   ,431,431,431
BEGIN DESCRIPTION:
Back Swamp 73.0
END DESCRIPTION:
XS GIS Cut Line= 3
        2371925.       901425.03      2371938.18       900701.26
      2372105.62       900366.83
#Sta/Elev= 30
  4337.4  120.99  4351.1     120  4386.1  114.67  4425.2   110.9  4442.9  110.22
  4454.9  108.23  4478.3   106.3  4524.4  103.54  4734.3   99.97  4802.4  100.55
  4830.9   98.68  4849.6   99.91  4866.5   98.43  4906.4   100.9  4930.5   99.96
  4963.1  100.64  4976.1  100.41  4993.1    97.9  4993.6    97.4    5007    97.9
  5023.1   99.63  5067.7   99.21    5082  100.12  5096.1  106.08  5106.6  108.93
  5136.7  113.69  5170.3  116.23  5292.5   118.7  5384.8  123.69  5435.3  128.15
#Mann= 3 ,-1,0
  4337.4     .15       0  4993.1     .05       0    5007     .15       0
Bank Sta=4993.1,5007
XS Rating Curve= 0 ,0
Exp/Cntr=0.3,0.1

Type RM Length L Ch R = 1 ,46750   ,500,500,500
BEGIN DESCRIPTION:
Back Swamp 72.0
END DESCRIPTION:
XS GIS Cut Line= 3
        2372175.       901425.01      2372326.24       900826.84
      2372275.01       900625.04
#Sta/Elev= 30
    4383  123.81    4438  112.09  4481.9  106.77  4485.4  107.11  4516.5  105.44
  4575.8  103.77  4602.7   103.8  4605.6  103.17  4614.7  103.31  4628.8  102.41
  4668.9   102.2  4703.9  101.18  4760.2  101.12    4831   99.18  4845.2   99.44
    4948   97.64  4978.1   98.08    4992   97.19  4993.1   96.58  4993.6   96.08
  5006.5   96.08    5007   96.58  5020.2   98.23  5077.4   97.75  5102.2   98.36
  5146.4   98.18  5153.5  101.54  5182.5  119.33    5191  122.86  5208.2  127.08
#Mann= 3 ,-1,0
    4383     .15       0  4993.1     .05       0    5007     .15       0
Bank Sta=4993.1,5007
XS Rating Curve= 0 ,0
Exp/Cntr=0.3,0.1

Type RM Length L Ch R = 1 ,46250   ,472,472,472
BEGIN DESCRIPTION:
Back Swamp 71.0
END DESCRIPTION:
XS GIS Cut Line= 3
      2372677.89       901499.96      2372751.17       900714.87
      2372715.53       900423.24
#Sta/Elev= 30
  4211.5   125.2  4241.2  120.83  4285.2  119.08  4312.1  117.03  4384.7  108.42
  4521.5  104.61  4541.1  102.72  4606.4  100.39  4618.6   98.97  4638.3   98.03
  4697.1    96.9  4889.2   96.49  4899.3   97.07  4911.6   96.49  4958.2   97.01
  4993.1   96.16  4993.6   95.66    5007   96.16    5031   97.47  5049.5   97.21
  5057.8   98.02    5068  101.17    5092  105.56  5107.8  109.49  5111.9  111.21
  5121.3  112.56  5126.7  114.66  5181.1  123.77  5214.1  127.35  5293.8  133.67
#Mann= 3 ,-1,0
  4211.5     .15       0  4993.1     .05       0    5007     .15       0
Bank Sta=4993.1,5007
XS Rating Curve= 0 ,0
Exp/Cntr=0.3,0.1

Type RM Length L Ch R = 1 ,45778   ,499,499,499
BEGIN DESCRIPTION:
Back Swamp 70.0
END DESCRIPTION:
XS GIS Cut Line= 3
      2372925.01       901374.99      2373139.31       900826.57
      2372924.98       900524.97
#Sta/Elev= 30
  4411.2  121.99  4420.6  120.21  4455.1  117.51  4542.7  105.78  4575.3  102.99
  4597.3  103.07    4614  101.82  4673.2  100.72  4686.8   98.93  4706.1   98.26
    4732   101.5  4744.7  102.36  4752.7  101.56  4774.6  103.93  4795.8  103.29
  4801.7  101.79    4814  101.07  4834.1   97.88  4837.6   96.06  4967.3   96.05
  4991.6   97.02    4993   96.03  4993.5   95.53    5007   96.03  5247.7   97.61
  5262.8   98.56  5280.2  103.84  5326.4  115.37  5344.4  118.93    5370  121.73
#Mann= 3 ,-1,0
  4411.2     .15       0    4993     .05       0    5007     .15       0
Bank Sta=4993,5007
XS Rating Curve= 0 ,0
Exp/Cntr=0.3,0.1

Type RM Length L Ch R = 1 ,45279   ,490,490,490
BEGIN DESCRIPTION:
Back Swamp 69.0
END DESCRIPTION:
XS GIS Cut Line= 3
      2373314.14       901891.56      2373517.85       900713.54
        2373425.       900224.99
#Sta/Elev= 30
  3804.5  124.44  4145.5  116.15  4212.9   113.1  4264.6  113.26  4392.9  105.75
  4417.1  102.91    4452  102.72    4511  100.43    4557  100.31  4572.9   98.86
  4585.5   99.73    4605   98.16    4637   98.29  4714.6   96.14  4992.9   94.35
  4993.4   93.85  5007.1   94.35  5021.9   95.11  5098.3   94.98  5161.5   97.15
  5181.4   96.48  5271.5   98.16  5292.1   97.74  5330.6   99.02  5360.4   98.66
  5383.8  103.14  5408.9  110.79  5445.4  120.24  5464.7   121.9  5497.3  128.53
#Mann= 3 ,-1,0
  3804.5     .15       0  4992.9     .05       0  5007.1     .15       0
Bank Sta=4992.9,5007.1
XS Rating Curve= 0 ,0
Exp/Cntr=0.3,0.1