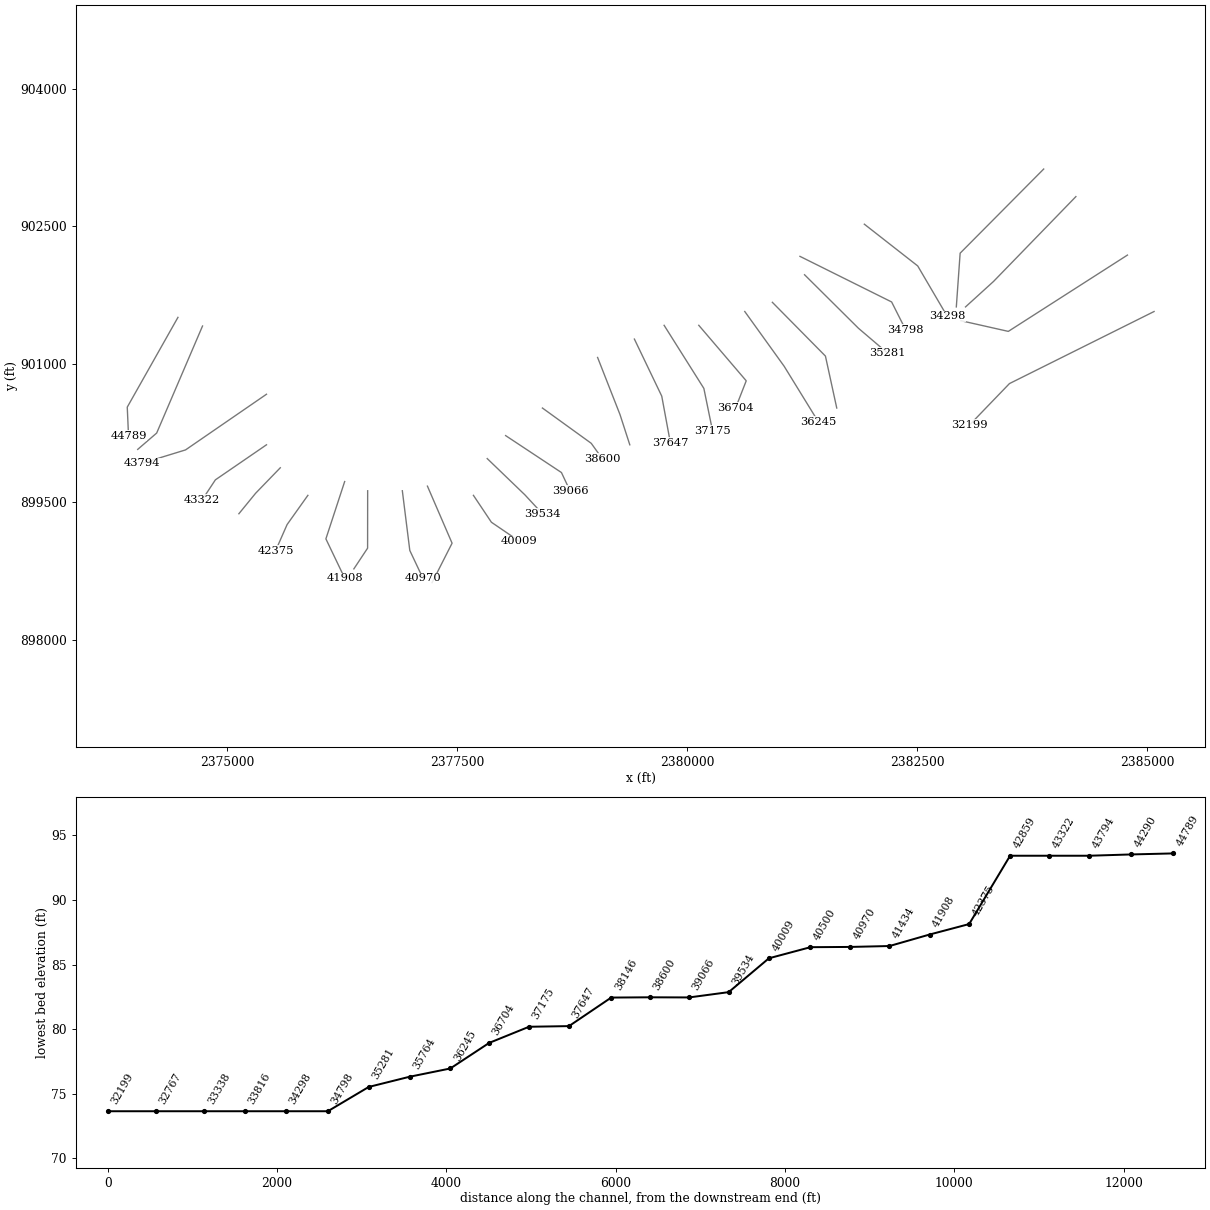
HEC-RAS study BackSwamp.prj: S-16-495 over Back Swamp

--- BackSwamp.g03 (geometry) --- (continued)

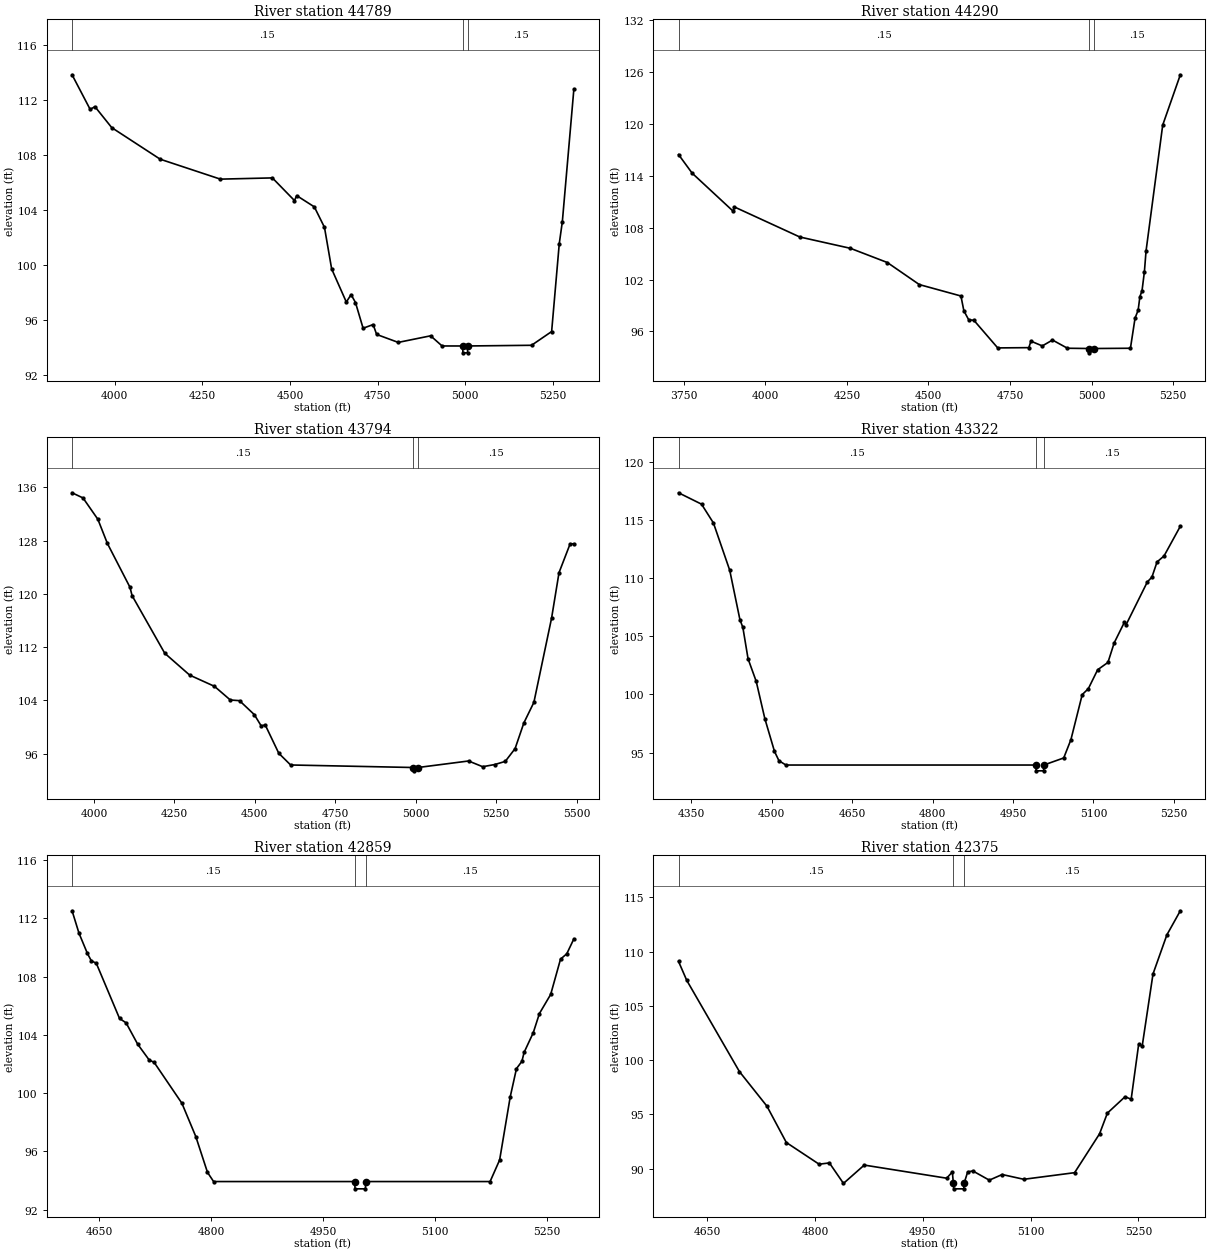
Type RM Length L Ch R = 1 ,44789   ,499,499,499
BEGIN DESCRIPTION:
Back Swamp 68.0
END DESCRIPTION:
XS GIS Cut Line= 3
      2374462.41       901511.31      2373911.32       900534.67
        2373925.       900224.97
#Sta/Elev= 30
  3878.6  113.86  3930.2  111.34  3943.8  111.54  3991.8  110.01  4130.1  107.71
  4301.6  106.26    4450  106.35    4513   104.7  4519.4  105.06  4569.7  104.24
  4598.6  102.75  4619.1   99.72  4660.9   97.31  4674.6   97.85  4687.1   97.27
  4708.8    95.4  4737.4   95.67  4747.4   94.95    4809   94.37  4901.4   94.85
  4934.1   94.11  4992.9   94.11  4993.4   93.61  5006.6   93.61  5007.1   94.11
  5189.3   94.16  5246.6   95.16  5268.4  101.57  5277.1  103.15    5310  112.81
#Mann= 3 ,-1,0
  3878.6     .15       0  4992.9     .05       0  5007.1     .15       0
Bank Sta=4992.9,5007.1
XS Rating Curve= 0 ,0
Exp/Cntr=0.3,0.1

Type RM Length L Ch R = 1 ,44290   ,496,496,496
BEGIN DESCRIPTION:
Back Swamp 67.0
END DESCRIPTION:
XS GIS Cut Line= 3
       2374729.7       901417.17      2374231.22       900252.89
      2374025.03       900075.03
#Sta/Elev= 30
  3733.5  116.45  3775.2   114.3  3900.7  109.91    3905  110.39  4105.4  106.92
  4260.7  105.61  4373.8  103.97  4471.9  101.42  4599.5   100.1  4608.5   98.39
  4623.3   97.35  4639.3   97.29  4712.3    94.1  4807.7   94.13  4814.2   94.88
    4849   94.33  4880.3   95.01  4926.2   94.06  4992.8   94.03  4993.3   93.53
  5007.2   94.03  5119.3   94.06  5133.5   97.55  5142.9   98.45  5148.3  100.03
  5154.8   100.7  5162.1  102.89  5167.2  105.31  5218.3  119.86  5272.3  125.67
#Mann= 3 ,-1,0
  3733.5     .15       0  4992.8     .05       0  5007.2     .15       0
Bank Sta=4992.8,5007.2
XS Rating Curve= 0 ,0
Exp/Cntr=0.3,0.1

Type RM Length L Ch R = 1 ,43794   ,472,472,472
BEGIN DESCRIPTION:
Back Swamp 66.0
END DESCRIPTION:
XS GIS Cut Line= 3
      2375424.96       900674.97        2374545.        900069.4
      2374074.98       899924.99
#Sta/Elev= 30
  3931.8  135.19  3965.9  134.41    4012  131.21  4041.6  127.58  4111.8     121
  4118.4  119.74  4219.9  111.09  4297.3  107.81  4374.5  106.12  4423.7  104.07
  4452.3  103.97  4498.4  101.87  4519.7  100.18  4532.2  100.33  4574.4   96.07
  4611.2   94.31  4992.8   93.93  4993.3   93.43  5007.2   93.93  5164.4   94.91
  5208.2   94.05  5246.1   94.38  5278.5   94.85    5309   96.77  5336.3  100.63
  5367.4  103.71  5422.5  116.38  5445.6   123.2  5480.1  127.52  5491.7  127.53
#Mann= 3 ,-1,0
  3931.8     .15       0  4992.8     .05       0  5007.2     .15       0
Bank Sta=4992.8,5007.2
XS Rating Curve= 0 ,0
Exp/Cntr=0.3,0.1

Type RM Length L Ch R = 1 ,43322   ,463,463,463
BEGIN DESCRIPTION:
Back Swamp 65.0
END DESCRIPTION:
XS GIS Cut Line= 3
      2375425.04       900125.03      2374869.33       899743.63
      2374724.99       899524.98
#Sta/Elev= 30
    4326  117.36  4368.9  116.38  4391.1  114.76  4421.5  110.69  4440.5  106.44
    4446  105.77  4455.7  103.07  4470.9  101.13    4487   97.92    4505    95.1
  4513.3    94.3  4526.3   93.93  4992.6   93.93  4993.1   93.43  5006.9   93.43
  5007.4   93.93  5044.5   94.54  5057.9   96.11    5079   99.99  5090.4   100.5
  5107.8  102.13    5127  102.76  5138.6  104.44  5157.6  106.21    5161  106.02
  5200.5  109.69    5209   110.1  5218.6  111.41  5231.6  111.92    5262  114.48
#Mann= 3 ,-1,0
    4326     .15       0  4992.6     .05       0  5007.4     .15       0
Bank Sta=4992.6,5007.4
XS Rating Curve= 0 ,0
Exp/Cntr=0.3,0.1

Type RM Length L Ch R = 1 ,42859   ,484,484,484
BEGIN DESCRIPTION:
Back Swamp 64.0
END DESCRIPTION:
XS GIS Cut Line= 3
      2375575.01       899875.01      2375306.25        899597.1
      2375124.98       899374.98
#Sta/Elev= 30
  4613.4  112.51  4622.7  110.97    4634  109.58  4639.2  109.08  4645.9  108.91
  4677.1  105.12  4685.9  104.82  4701.5  103.35  4716.9  102.27  4723.5  102.11
  4760.8    99.3  4779.4   97.02  4795.1   94.56  4803.3   93.93  4992.6   93.93
  4993.1   93.43    5007   93.43  5007.5   93.93  5174.3   93.93  5187.1   95.41
  5201.3   99.74  5209.7  101.68    5217  102.18  5219.9  102.79  5232.2  104.14
  5240.5  105.46  5255.6  106.77  5268.8  109.19  5277.2  109.56  5286.7  110.58
#Mann= 3 ,-1,0
  4613.4     .15       0  4992.6     .05       0  5007.5     .15       0
Bank Sta=4992.6,5007.5
XS Rating Curve= 0 ,0
Exp/Cntr=0.3,0.1

Type RM Length L Ch R = 1 ,42375   ,467,467,467
BEGIN DESCRIPTION:
Back Swamp 63.0
END DESCRIPTION:
XS GIS Cut Line= 3
      2375875.02       899575.03      2375649.18       899257.31
      2375525.01       898975.02
#Sta/Elev= 30
  4610.2   109.1  4621.6  107.36  4694.9   98.95  4733.1   95.77  4760.2   92.41
  4805.8   90.41  4820.1   90.53  4839.7   88.64  4868.6   90.33  4983.3   89.12
  4991.2    89.7  4992.6   88.64  4993.1   88.14    5007   88.14  5007.5   88.64
  5012.5    89.7  5019.7   89.79  5042.6   88.94  5060.5   89.46  5090.6   89.02
  5161.3   89.63    5196   93.21  5206.9   95.12  5231.5   96.63    5240    96.4
  5250.4  101.45  5255.4  101.32  5270.4  107.95  5289.7  111.55  5308.4  113.77
#Mann= 3 ,-1,0
  4610.2     .15       0  4992.6     .05       0  5007.5     .15       0
Bank Sta=4992.6,5007.5
XS Rating Curve= 0 ,0
Exp/Cntr=0.3,0.1

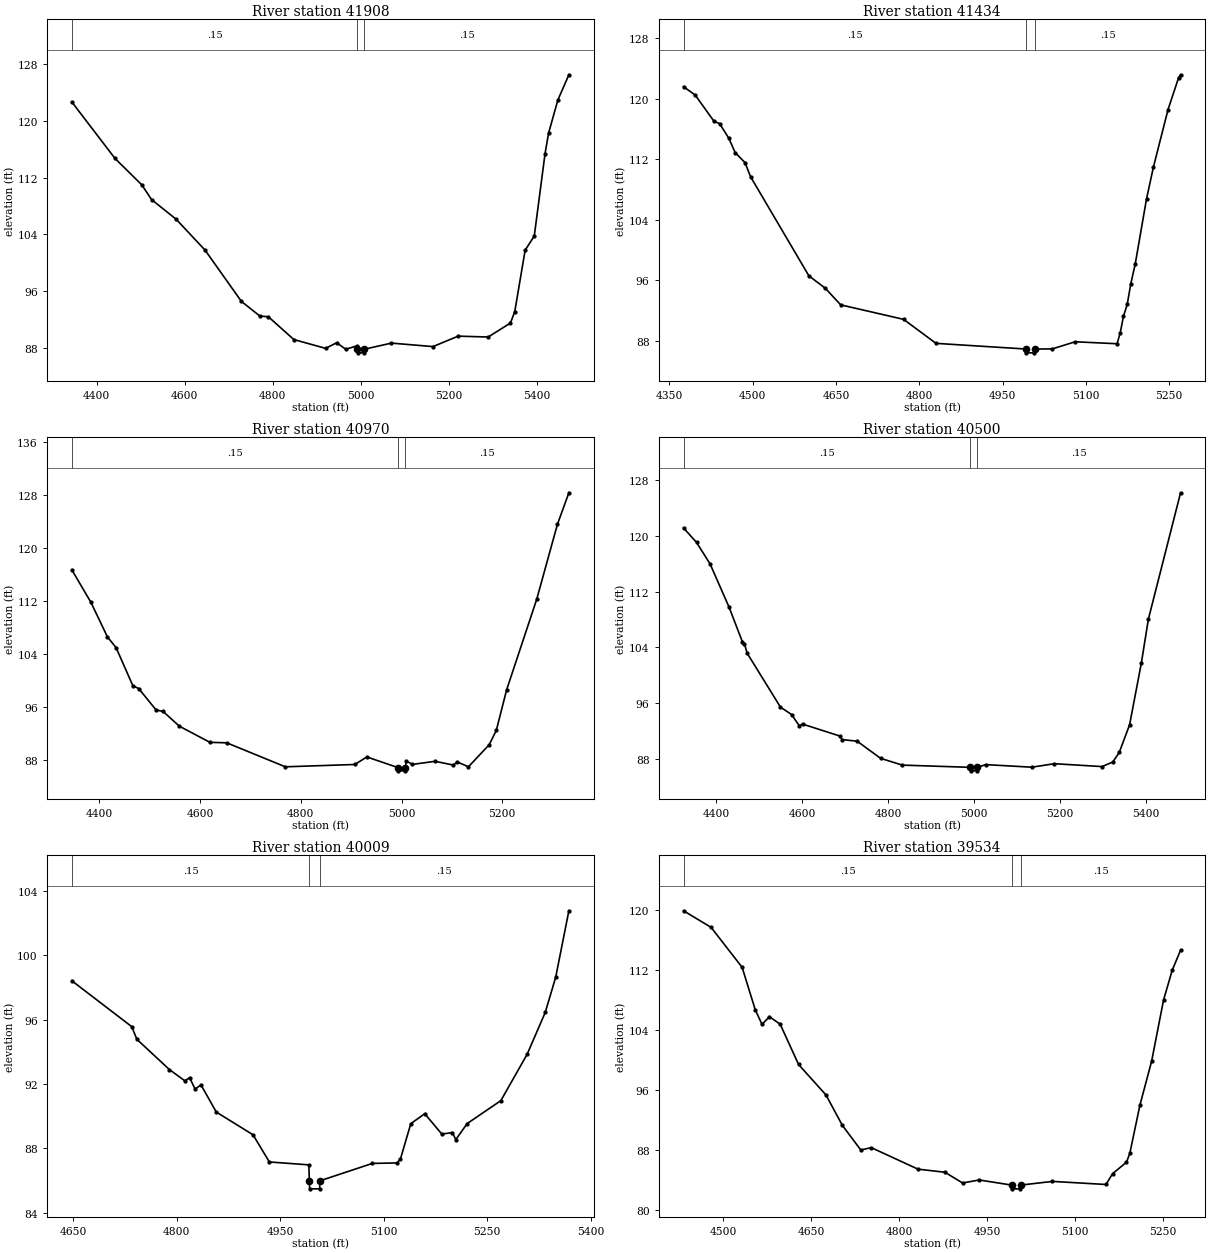
Type RM Length L Ch R = 1 ,41908   ,474,474,474
BEGIN DESCRIPTION:
Back Swamp 62.0
END DESCRIPTION:
XS GIS Cut Line= 3
        2376275.       899725.01      2376070.87       899101.48
      2376274.99       898675.01
#Sta/Elev= 30
  4343.9  122.66  4441.9  114.71  4502.8  110.99  4524.9  108.92  4580.7  106.15
  4646.4   101.8  4729.1   94.57    4771   92.51  4790.3   92.41  4848.2    89.2
  4920.2   87.96  4945.5   88.75  4966.2   87.83  4991.6   88.32  4992.5   87.83
    4993   87.33    5007   87.33  5007.5   87.83  5069.8    88.7  5164.1   88.21
  5221.3   89.68  5289.5   89.56  5340.2   91.53  5349.9   93.14  5373.5  101.79
  5394.2  103.78  5418.6  115.35  5426.7  118.27  5447.7  122.92  5472.8  126.49
#Mann= 3 ,-1,0
  4343.9     .15       0  4992.5     .05       0  5007.5     .15       0
Bank Sta=4992.5,5007.5
XS Rating Curve= 0 ,0
Exp/Cntr=0.3,0.1

Type RM Length L Ch R = 1 ,41434   ,464,464,464
BEGIN DESCRIPTION:
Back Swamp 61.0
END DESCRIPTION:
XS GIS Cut Line= 3
        2376525.       899624.96      2376524.28       899000.46
        2376375.         898775.
#Sta/Elev= 30
  4375.5  121.56  4396.5  120.46  4430.3     117  4440.4  116.69  4457.3  114.73
  4468.4  112.87  4486.2  111.54  4496.2  109.68  4601.2    96.6  4630.8   94.96
  4658.5   92.77  4771.7   90.86  4830.1   87.69  4992.5   86.94    4993   86.44
  5007.1   86.44  5007.6   86.94  5039.4   86.96  5080.7    87.9  5156.1   87.64
  5161.8    89.1  5167.6   91.26  5174.4   92.85  5180.7   95.52  5188.8   98.17
  5209.1  106.75  5221.4  110.91  5247.8  118.53    5267  122.77  5270.4  123.13
#Mann= 3 ,-1,0
  4375.5     .15       0  4992.5     .05       0  5007.6     .15       0
Bank Sta=4992.5,5007.6
XS Rating Curve= 0 ,0
Exp/Cntr=0.3,0.1

Type RM Length L Ch R = 1 ,40970   ,470,470,470
BEGIN DESCRIPTION:
Back Swamp 60.0
END DESCRIPTION:
XS GIS Cut Line= 3
      2376901.99       899625.15      2376983.18        898975.4
        2377125.         898675.
#Sta/Elev= 30
  4345.2  116.74  4383.2  111.81  4415.8  106.62  4433.1  104.98  4466.4   99.23
    4478    98.8  4512.6   95.56  4526.3   95.35  4558.8   93.11  4619.4   90.68
  4652.9    90.6  4769.2   86.98  4907.1   87.33    4931   88.47  4992.5   86.87
    4993   86.37  5007.1   86.37  5007.6   86.87  5009.2   87.87  5021.4   87.34
  5066.6   87.81    5103   87.24  5110.3   87.72  5132.8   86.98    5174   90.32
  5188.1   92.48  5208.6   98.61  5268.3  112.28  5309.4   123.6  5332.2  128.38
#Mann= 3 ,-1,0
  4345.2     .15       0  4992.5     .05       0  5007.6     .15       0
Bank Sta=4992.5,5007.6
XS Rating Curve= 0 ,0
Exp/Cntr=0.3,0.1

Type RM Length L Ch R = 1 ,40500   ,491,491,491
BEGIN DESCRIPTION:
Back Swamp 59.0
END DESCRIPTION:
XS GIS Cut Line= 3
      2377174.98       899675.05      2377442.85       899054.49
      2377224.99       898624.99
#Sta/Elev= 30
  4324.1   121.1  4354.5  119.02  4385.9  115.96  4430.2  109.76    4461  104.84
  4466.1  104.51  4472.2  103.19  4549.8   95.47  4575.6   94.41  4593.5   92.82
  4601.3   93.04  4687.5   91.34  4693.6   90.82  4728.5   90.59    4783   88.14
  4833.6   87.17  4992.4   86.85  4992.9   86.35  5007.1   86.35  5007.6   86.85
  5028.3   87.24  5135.3   86.87  5187.6   87.37  5298.6   86.96  5323.7   87.61
  5338.8   88.98  5362.9   92.94  5390.2  101.74  5406.7  108.06  5481.6  126.13
#Mann= 3 ,-1,0
  4324.1     .15       0  4992.4     .05       0  5007.6     .15       0
Bank Sta=4992.4,5007.6
XS Rating Curve= 0 ,0
Exp/Cntr=0.3,0.1

Type RM Length L Ch R = 1 ,40009   ,475,475,475
BEGIN DESCRIPTION:
Back Swamp 58.0
END DESCRIPTION:
XS GIS Cut Line= 3
      2377674.99       899575.02      2377870.42       899282.37
      2378175.02       899074.98
#Sta/Elev= 30
  4648.1   98.42  4734.9   95.57  4742.4   94.78  4789.6    92.9    4812    92.2
  4818.8    92.4  4826.7   91.69  4835.3   91.95  4857.5   90.26  4910.7   88.85
  4934.4   87.16  4991.7   86.98  4992.3   85.99  4992.8   85.49  5007.2   85.49
  5007.7   85.99  5083.7   87.07  5119.5    87.1  5124.4   87.35  5139.4   89.54
  5159.6   90.16  5184.4   88.89  5199.6   88.99  5204.6   88.55  5221.2   89.55
  5269.9   90.97  5308.1   93.86  5334.3   96.46  5349.4   98.64  5368.5  102.77
#Mann= 3 ,-1,0
  4648.1     .15       0  4992.3     .05       0  5007.7     .15       0
Bank Sta=4992.3,5007.7
XS Rating Curve= 0 ,0
Exp/Cntr=0.3,0.1

Type RM Length L Ch R = 1 ,39534   ,468,468,468
BEGIN DESCRIPTION:
Back Swamp 57.0
END DESCRIPTION:
XS GIS Cut Line= 3
      2377824.98       899975.02      2378234.14        899580.9
      2378425.03       899374.96
#Sta/Elev= 30
  4431.9   119.9    4479  117.69    4532  112.37  4554.6  106.67    4566  104.77
  4578.6   105.8    4597  104.79  4628.4   99.43  4675.3   95.36  4703.2   91.32
  4734.7   88.04  4752.5   88.36  4832.4   85.49  4878.3   85.08  4908.5   83.65
    4937   84.05  4992.3   83.37  4992.8   82.87  5007.3   82.87  5007.8   83.37
    5062   83.86  5153.4   83.45  5164.8    84.9  5188.4   86.41  5194.1   87.59
  5211.4   94.02  5231.4   99.88  5251.7     108  5266.7  112.02  5280.8  114.64
#Mann= 3 ,-1,0
  4431.9     .15       0  4992.3     .05       0  5007.8     .15       0
Bank Sta=4992.3,5007.8
XS Rating Curve= 0 ,0
Exp/Cntr=0.3,0.1

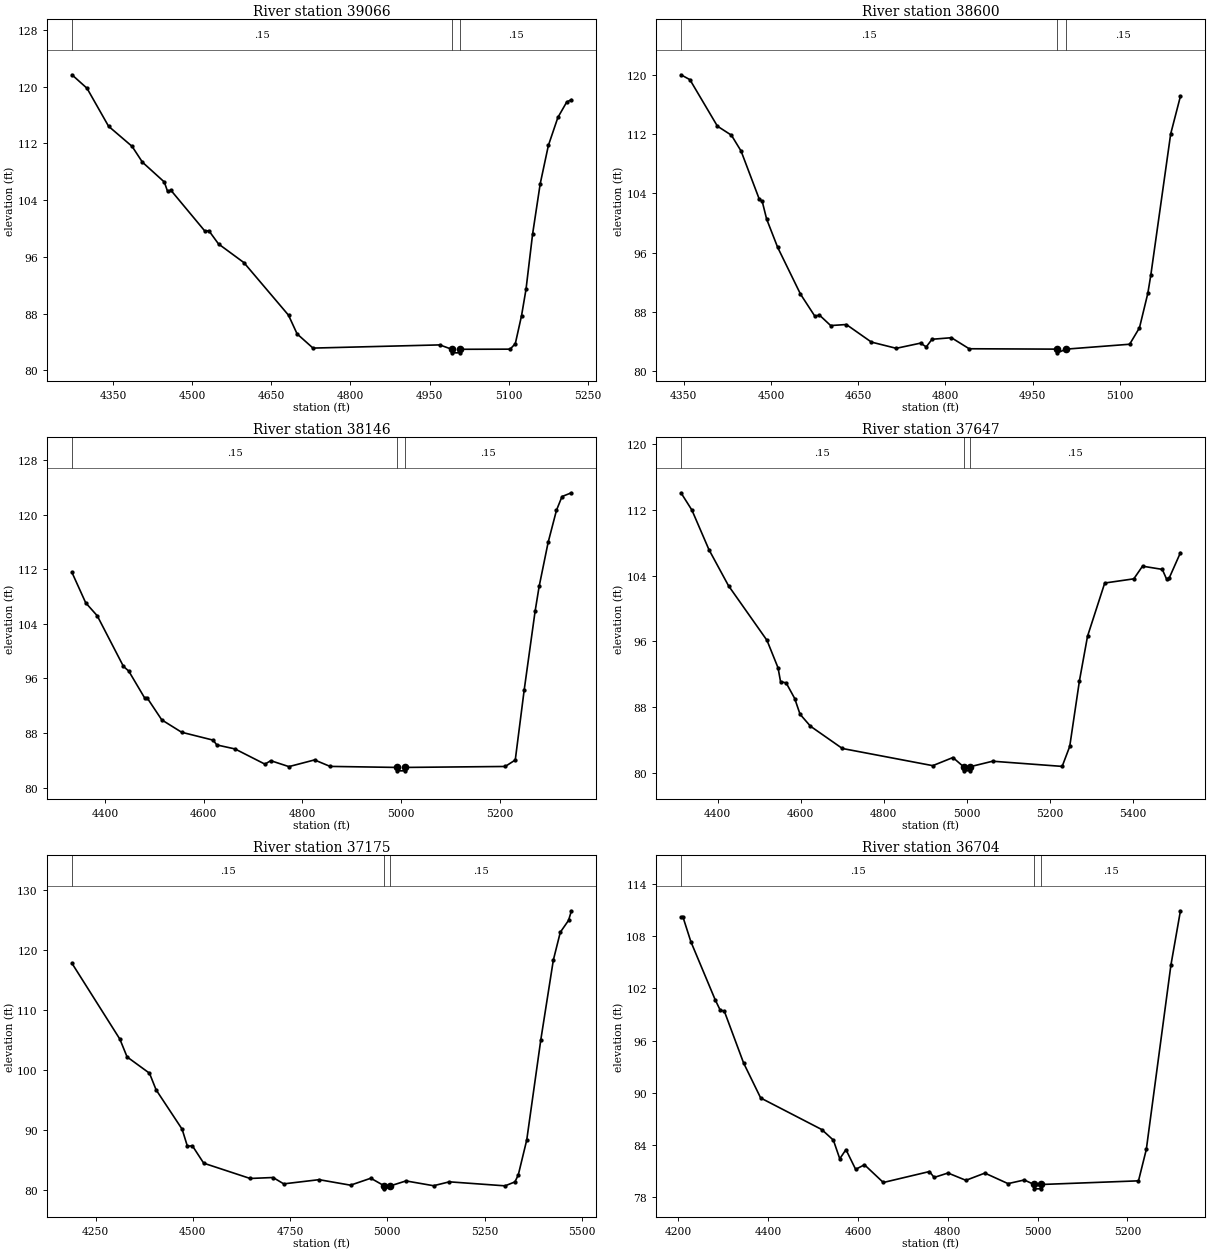
Type RM Length L Ch R = 1 ,39066   ,466,466,466
BEGIN DESCRIPTION:
Back Swamp 56.0
END DESCRIPTION:
XS GIS Cut Line= 3
        2378025.         900225.      2378631.85       899823.23
      2378724.99       899625.02
#Sta/Elev= 30
  4272.2  121.68  4300.7  119.78  4341.6  114.42  4386.2  111.58  4405.8  109.35
  4447.2  106.56  4453.4  105.25  4459.9  105.38  4524.3   99.62  4531.7   99.69
    4550   97.82  4598.1   95.19  4682.7   87.77    4699   85.13  4729.1   83.13
  4969.4   83.58  4992.3   82.96  4992.8   82.46  5007.3   82.46  5007.8   82.96
  5102.8   82.98  5112.6   83.75  5124.4   87.69  5132.9   91.42  5145.4   99.22
  5159.8   106.3  5175.3  111.71  5193.3  115.66  5210.1  117.84    5219  118.17
#Mann= 3 ,-1,0
  4272.2     .15       0  4992.3     .05       0  5007.8     .15       0
Bank Sta=4992.3,5007.8
XS Rating Curve= 0 ,0
Exp/Cntr=0.3,0.1

Type RM Length L Ch R = 1 ,38600   ,454,454,454
BEGIN DESCRIPTION:
Back Swamp 55.0
END DESCRIPTION:
XS GIS Cut Line= 3
      2378425.03       900524.98      2378955.78       900141.14
      2379075.01       899974.99
#Sta/Elev= 30
    4345  119.98  4360.4  119.32  4407.7  113.05  4431.8  111.83  4448.4   109.7
  4479.9  103.17  4484.8  102.91  4492.4  100.52  4511.4    96.7  4550.7   90.39
  4575.5    87.4  4583.2   87.57  4602.6   86.15  4629.6   86.29  4672.7   83.92
  4715.5   83.08  4757.3   83.78  4767.1   83.27    4777    84.3  4810.4   84.51
    4841   83.02  4992.3   82.97  4992.8   82.47  5007.8   82.97  5117.1   83.63
    5134   85.85  5148.4   90.51  5153.6      93  5187.7     112  5204.5  117.09
#Mann= 3 ,-1,0
    4345     .15       0  4992.3     .05       0  5007.8     .15       0
Bank Sta=4992.3,5007.8
XS Rating Curve= 0 ,0
Exp/Cntr=0.3,0.1

Type RM Length L Ch R = 1 ,38146   ,499,499,499
BEGIN DESCRIPTION:
Back Swamp 54.0
END DESCRIPTION:
XS GIS Cut Line= 3
      2379024.99       901075.02       2379268.5       900453.85
      2379375.01       900124.97
#Sta/Elev= 30
  4332.8  111.55  4360.7  107.09  4384.1  105.19  4437.2   97.77  4447.9   97.09
  4480.7   93.08  4485.2   93.16    4515   89.92  4555.2   88.11  4619.2   86.95
  4626.5   86.25  4663.5   85.66  4724.2   83.43  4735.9   83.94  4772.8   83.07
  4824.7   84.05  4856.3    83.1  4992.2   82.95  4992.7   82.45  5007.3   82.45
  5007.8   82.95  5211.4   83.09  5231.8   84.04  5249.9   94.31    5272  105.84
  5280.2  109.49  5298.4  115.94  5315.4  120.67  5326.6  122.68  5345.7  123.23
#Mann= 3 ,-1,0
  4332.8     .15       0  4992.2     .05       0  5007.8     .15       0
Bank Sta=4992.2,5007.8
XS Rating Curve= 0 ,0
Exp/Cntr=0.3,0.1

Type RM Length L Ch R = 1 ,37647   ,472,472,472
BEGIN DESCRIPTION:
Back Swamp 53.0
END DESCRIPTION:
XS GIS Cut Line= 3
      2379424.99       901275.01      2379722.43        900654.3
      2379815.94       900148.47
#Sta/Elev= 30
  4311.7  114.07  4338.1  111.96  4379.1  107.15  4426.2  102.76  4518.9   96.11
  4545.5   92.77  4551.5   91.09    4565   90.94  4585.6   89.04  4598.4   87.13
  4623.5   85.67  4700.3   82.96    4918   80.87  4966.6   81.86  4992.1   80.74
  4992.6   80.24  5007.4   80.24  5007.9   80.74  5062.1   81.41  5229.6   80.78
  5247.8   83.21  5271.3   91.23  5290.7   96.62  5332.1  103.09  5402.1   103.6
  5423.1  105.14  5470.7  104.75    5481  103.57    5487  103.66  5514.4  106.78
#Mann= 3 ,-1,0
  4311.7     .15       0  4992.1     .05       0  5007.9     .15       0
Bank Sta=4992.1,5007.9
XS Rating Curve= 0 ,0
Exp/Cntr=0.3,0.1

Type RM Length L Ch R = 1 ,37175   ,471,471,471
BEGIN DESCRIPTION:
Back Swamp 52.0
END DESCRIPTION:
XS GIS Cut Line= 3
      2379748.16       901424.74      2380180.19       900738.63
      2380274.99       900275.03
#Sta/Elev= 30
  4189.2  117.82  4312.4  105.16  4330.9   102.2  4388.5   99.48  4405.5   96.71
  4472.4   90.14  4485.9   87.31  4498.9   87.36  4527.9   84.47  4647.2   81.92
  4706.2   82.08  4733.6   81.02  4824.5   81.72  4905.3    80.8  4957.5   81.96
    4992   80.69  4992.5   80.19    5008   80.69  5047.9   81.51  5118.7   80.71
  5159.4   81.36  5302.6   80.69    5328   81.35  5336.6   82.52  5358.3   88.34
  5394.5  105.07  5426.7  118.36  5444.6     123  5465.8  124.98  5473.2  126.58
#Mann= 3 ,-1,0
  4189.2     .15       0    4992     .05       0    5008     .15       0
Bank Sta=4992,5008
XS Rating Curve= 0 ,0
Exp/Cntr=0.3,0.1

Type RM Length L Ch R = 1 ,36704   ,459,459,459
BEGIN DESCRIPTION:
Back Swamp 51.0
END DESCRIPTION:
XS GIS Cut Line= 3
        2380125.       901425.01      2380640.83       900821.13
      2380524.99       900524.97
#Sta/Elev= 30
  4205.8  110.19  4209.9  110.26  4227.9  107.36  4281.8  100.71  4293.1    99.5
  4302.3   99.38  4345.3   93.41  4383.3   89.39  4519.3   85.76  4545.2   84.54
  4559.4    82.4  4573.2   83.45  4594.8   81.18  4614.4   81.71  4656.4   79.67
  4759.2   80.93  4769.5   80.25  4800.4   80.76  4840.3   79.92  4882.5   80.75
  4934.1   79.54  4970.3   79.96    4992   79.44  4992.5   78.94  5007.5   78.94
    5008   79.44  5224.6   79.86    5242   83.47  5296.8  104.68    5318  110.92
#Mann= 3 ,-1,0
  4205.8     .15       0    4992     .05       0    5008     .15       0
Bank Sta=4992,5008
XS Rating Curve= 0 ,0
Exp/Cntr=0.3,0.1

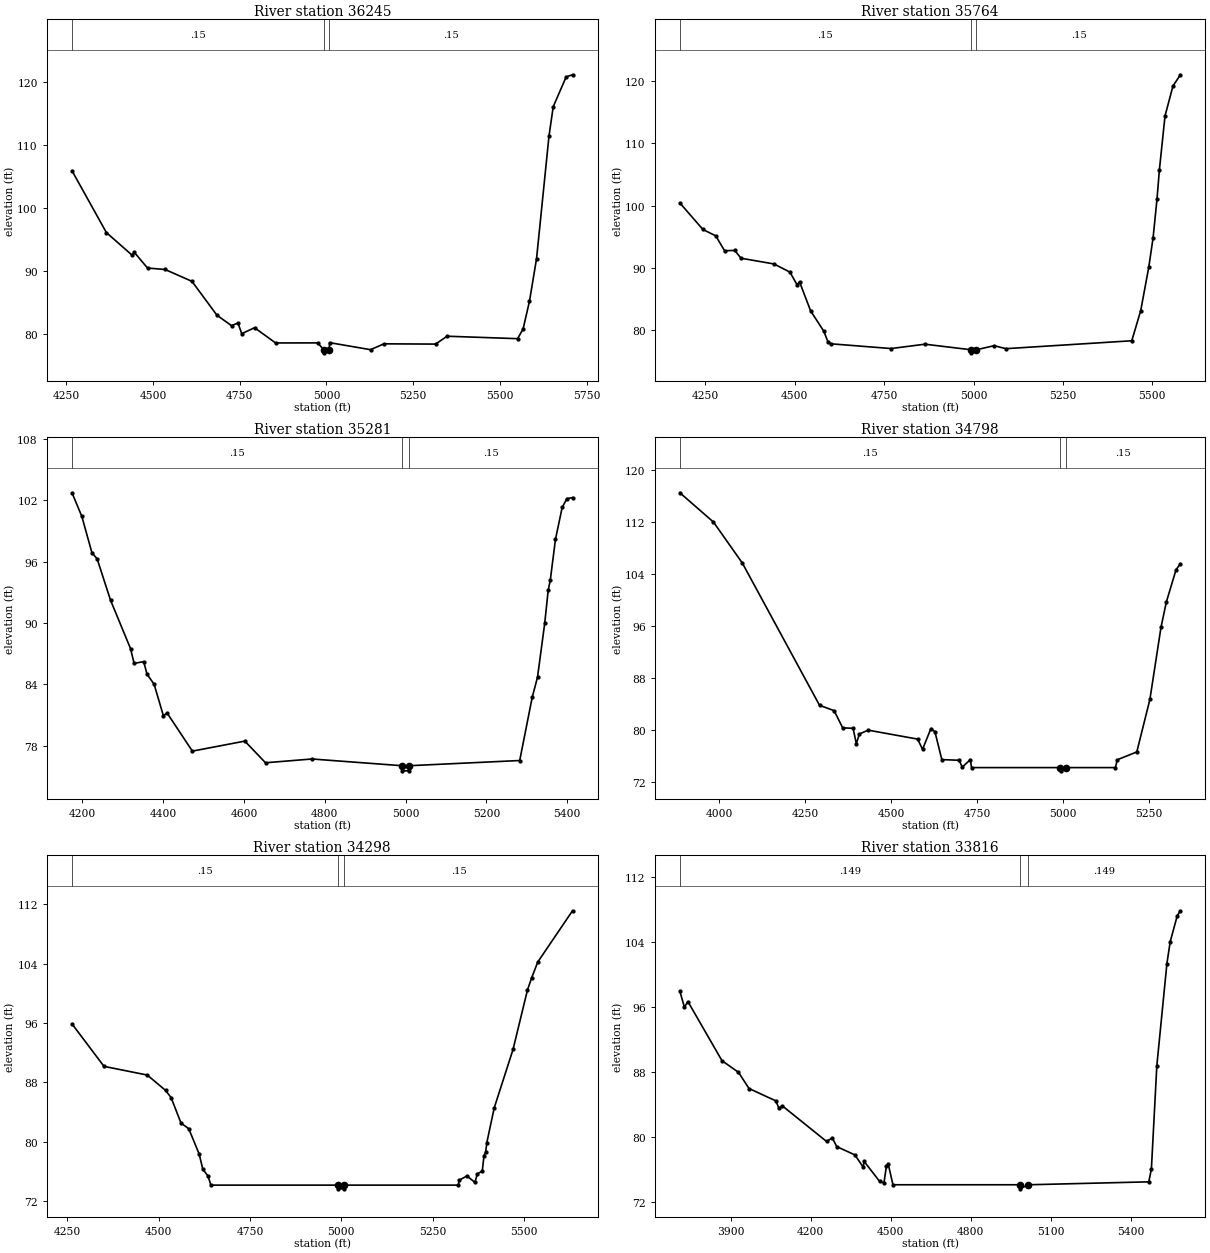
Type RM Length L Ch R = 1 ,36245   ,481,481,481
BEGIN DESCRIPTION:
Back Swamp 50.0
END DESCRIPTION:
XS GIS Cut Line= 3
      2380624.99       901575.01      2381053.28       900979.17
      2381425.02       900374.97
#Sta/Elev= 30
  4266.2  105.88  4365.3   96.07  4439.6   92.47  4445.6   92.94    4484   90.43
  4534.5    90.2    4612   88.32  4684.1   82.94  4726.2   81.28  4744.9   81.69
  4755.6      80  4792.6   80.95  4853.3   78.53  4974.6   78.54    4992   77.46
  4992.5   76.96  5008.1   77.46  5008.8   78.58    5127   77.46  5165.5   78.39
  5314.7   78.35  5347.7    79.6  5550.9   79.21  5566.8   80.73  5585.2   85.13
  5605.7   91.92  5641.6   111.4  5653.8  116.06  5691.1   120.8  5709.4  121.13
#Mann= 3 ,-1,0
  4266.2     .15       0    4992     .05       0  5008.1     .15       0
Bank Sta=4992,5008.1
XS Rating Curve= 0 ,0
Exp/Cntr=0.3,0.1

Type RM Length L Ch R = 1 ,35764   ,483,483,483
BEGIN DESCRIPTION:
Back Swamp 49.0
END DESCRIPTION:
XS GIS Cut Line= 3
      2380925.02       901674.98      2381501.98       901090.19
        2381625.       900525.02
#Sta/Elev= 30
  4178.5  100.41  4242.9   96.15  4278.8   95.13  4303.4   92.74    4332   92.78
  4349.4   91.53  4441.6   90.61  4486.3    89.3    4506   87.28  4513.2   87.73
  4544.2   83.06  4581.1   79.79  4592.9   78.05  4601.2   77.77  4769.4   77.01
  4863.8   77.71    4992   76.82  4992.5   76.32  5008.1   76.82  5057.5   77.47
  5090.2   76.99  5442.4   78.26  5467.4    83.1    5490    90.1  5502.1   94.84
    5513  101.04  5519.6   105.7  5535.4   114.4  5557.6  119.21  5578.4  121.02
#Mann= 3 ,-1,0
  4178.5     .15       0    4992     .05       0  5008.1     .15       0
Bank Sta=4992,5008.1
XS Rating Curve= 0 ,0
Exp/Cntr=0.3,0.1

Type RM Length L Ch R = 1 ,35281   ,483,483,483
BEGIN DESCRIPTION:
Back Swamp 48.0
END DESCRIPTION:
XS GIS Cut Line= 3
      2381275.01       901974.99      2381860.47       901393.17
      2382174.97       901125.02
#Sta/Elev= 30
  4174.6  102.75    4199  100.43  4223.8   96.89  4236.8   96.28    4270   92.23
  4319.5   87.49  4328.3   86.05  4352.1   86.22  4360.2   84.99  4377.8   84.01
  4400.6   80.94  4410.3   81.17  4472.5   77.46  4602.3   78.44  4653.5   76.32
  4768.5   76.69  4991.9   76.03  4992.4   75.53  5007.6   75.53  5008.1   76.03
  5282.6   76.54  5313.5   82.71  5326.7    84.7  5344.5   89.97  5353.1   93.19
  5358.4   94.22  5371.1   98.19  5387.7  101.31  5399.3  102.17  5413.3  102.28
#Mann= 3 ,-1,0
  4174.6     .15       0  4991.9     .05       0  5008.1     .15       0
Bank Sta=4991.9,5008.1
XS Rating Curve= 0 ,0
Exp/Cntr=0.3,0.1

Type RM Length L Ch R = 1 ,34798   ,500,500,500
BEGIN DESCRIPTION:
Back Swamp 47.0
END DESCRIPTION:
XS GIS Cut Line= 3
        2381225.         902175.      2382221.67       901678.92
      2382374.99       901375.01
#Sta/Elev= 30
  3886.7   116.5  3984.2  111.99    4068  105.68  4292.3   83.75  4334.7   82.92
  4359.5   80.28  4389.8    80.2  4399.2   77.82  4408.1   79.33  4433.5   79.92
  4577.3   78.54  4591.5   76.96  4615.8   80.17  4627.5   79.67  4647.5   75.38
  4697.8   75.28  4706.8   74.22  4730.4   75.38  4733.7   74.15  4991.9   74.15
  4992.4   73.65  5008.2   74.15  5151.6   74.15  5157.2   75.36  5213.8   76.56
  5251.9   84.68    5284   95.75  5299.5   99.65  5327.7  104.63  5340.4  105.56
#Mann= 3 ,-1,0
  3886.7     .15       0  4991.9     .05       0  5008.2     .15       0
Bank Sta=4991.9,5008.2
XS Rating Curve= 0 ,0
Exp/Cntr=0.3,0.1

Type RM Length L Ch R = 1 ,34298   ,482,482,482
BEGIN DESCRIPTION:
Back Swamp 46.0
END DESCRIPTION:
XS GIS Cut Line= 3
        2381925.         902525.      2382505.29        902070.8
      2382824.98       901525.04
#Sta/Elev= 30
  4263.1   95.87  4350.6   90.15  4469.1   88.98    4519   86.91  4534.2   85.95
  4561.3   82.51  4582.5   81.75  4611.1   78.33  4620.9    76.3  4635.4   75.36
    4643   74.15  4991.7   74.15  4992.2   73.65  5007.9   73.65  5008.4   74.15
  5319.8   74.15  5323.3   74.84  5343.8   75.39  5365.3   74.52  5372.2   75.66
  5385.6   76.05  5390.4   78.14  5394.8   78.59  5398.1   79.88  5418.2   84.54
  5469.8   92.43  5509.2  100.43    5521  102.12  5537.6  104.22  5632.5  111.11
#Mann= 3 ,-1,0
  4263.1     .15       0  4991.7     .05       0  5008.4     .15       0
Bank Sta=4991.7,5008.4
XS Rating Curve= 0 ,0
Exp/Cntr=0.3,0.1

Type RM Length L Ch R = 1 ,33816   ,478,478,478
BEGIN DESCRIPTION:
Back Swamp 45.0
END DESCRIPTION:
XS GIS Cut Line= 3
      2383875.01       903125.01      2382966.55       902209.57
        2382925.       901625.05
#Sta/Elev= 30
  3710.3   97.93    3727   95.99  3740.5   96.66    3868    89.4  3929.9   87.97
  3969.3   85.98    4070   84.46  4081.3   83.56  4094.5   83.84  4260.1   79.47
  4281.4   79.91  4298.2   78.84  4366.1   77.82  4397.5   76.31  4400.6   77.03
  4458.9   74.56  4475.1   74.37  4484.3   76.46  4491.2   76.68  4508.8   74.15
  4983.9   74.15  4984.4   73.65  5016.2   74.15  5467.5   74.51  5477.3   76.08
  5497.7   88.78  5535.5  101.34  5547.8  104.02  5574.4  107.23    5586  107.82
#Mann= 3 ,-1,0
  3710.3    .149       0  4983.9     .05       0  5016.2    .149       0
Bank Sta=4983.9,5016.2
XS Rating Curve= 0 ,0
Exp/Cntr=0.3,0.1

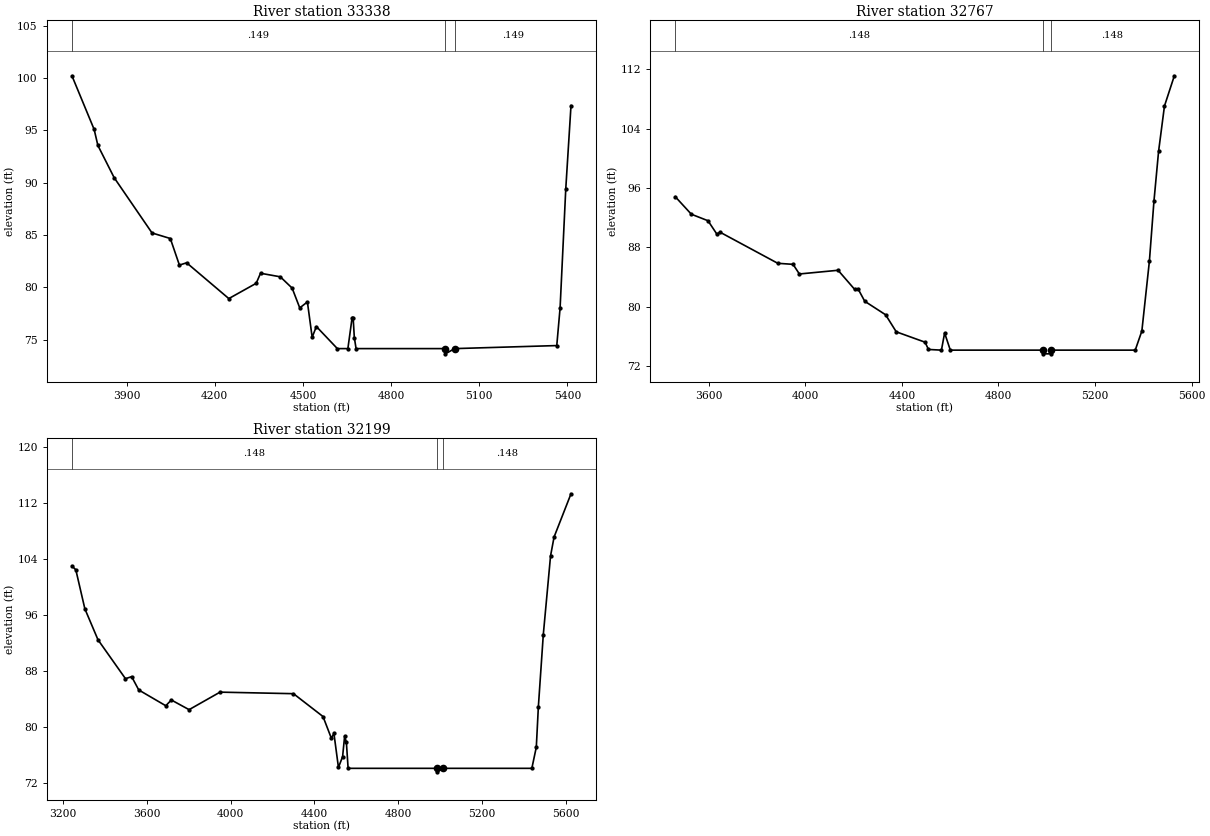
Type RM Length L Ch R = 1 ,33338   ,571,571,571
BEGIN DESCRIPTION:
Back Swamp 44.0
END DESCRIPTION:
XS GIS Cut Line= 3
      2384225.01       902825.01      2383329.64        901902.2
      2383024.98       901624.98
#Sta/Elev= 30
  3714.2  100.22  3789.8   95.09  3802.5   93.56  3857.9   90.48  3986.7    85.2
  4048.9   84.67  4079.8   82.13  4104.4   82.35  4247.9   78.93    4341   80.39
  4355.8   81.35  4423.1   81.01  4463.3   79.93  4489.2   78.04  4515.2   78.61
  4531.4   75.23  4545.7   76.26  4617.1   74.15  4652.9   74.15  4667.4   77.12
  4670.8   77.11  4674.8   75.21  4680.8   74.15  4983.8   74.15  4984.4   73.65
  5016.2   74.15  5363.5   74.44  5374.8   78.04  5394.1   89.41  5411.9   97.37
#Mann= 3 ,-1,0
  3714.2    .149       0  4983.8     .05       0  5016.2    .149       0
Bank Sta=4983.8,5016.2
XS Rating Curve= 0 ,0
Exp/Cntr=0.3,0.1

Type RM Length L Ch R = 1 ,32767   ,568,568,568
BEGIN DESCRIPTION:
Back Swamp 43.0
END DESCRIPTION:
XS GIS Cut Line= 3
      2384785.52       902188.99      2383490.35       901358.81
      2382974.98         901475.
#Sta/Elev= 30
  3461.6   94.84  3528.1   92.48  3597.1    91.6    3634   89.79  3646.7   90.06
  3886.1   85.86  3949.4   85.72  3975.5   84.42  4135.8   84.92  4204.8   82.33
    4218   82.44  4246.2   80.74  4332.6   78.92  4376.7   76.62    4496   75.22
  4510.1   74.24  4563.8   74.15    4577   76.46  4600.6   74.15  4983.8   74.15
  4984.3   73.65  5015.7   73.65  5016.3   74.15  5366.4   74.15  5393.8   76.73
    5425   86.15  5443.8   94.21    5463  100.95  5487.4  107.07  5528.3  111.15
#Mann= 3 ,-1,0
  3461.6    .148       0  4983.8     .05       0  5016.3    .148       0
Bank Sta=4983.8,5016.3
XS Rating Curve= 0 ,0
Exp/Cntr=0.3,0.1

Type RM Length L Ch R = 1 ,32199   ,461,461,461
BEGIN DESCRIPTION:
Back Swamp 42.0
END DESCRIPTION:
XS GIS Cut Line= 3
      2385075.04       901575.02       2383502.6       900790.92
      2383068.75       900340.47
#Sta/Elev= 30
  3242.9  103.03  3261.6  102.46  3304.6   96.91  3367.3   92.49  3498.5   86.94
    3528   87.23  3561.9   85.33  3690.9   83.08  3717.5    83.9  3802.2   82.52
  3949.9   85.02  4300.5    84.8  4441.5   81.54  4481.3   78.45  4493.6   79.14
  4515.2   74.28    4535   75.81  4544.8   78.76  4553.1   77.86  4561.4   74.15
  4983.8   74.15  4984.3   73.65  5016.3   74.15  5438.5   74.15  5459.8   77.17
  5469.6   82.93  5493.2   93.24  5527.8  104.46  5544.6  107.15  5625.4  113.32
#Mann= 3 ,-1,0
  3242.9    .148       0  4983.8     .05       0  5016.3    .148       0
Bank Sta=4983.8,5016.3
XS Rating Curve= 0 ,0
Exp/Cntr=0.3,0.1