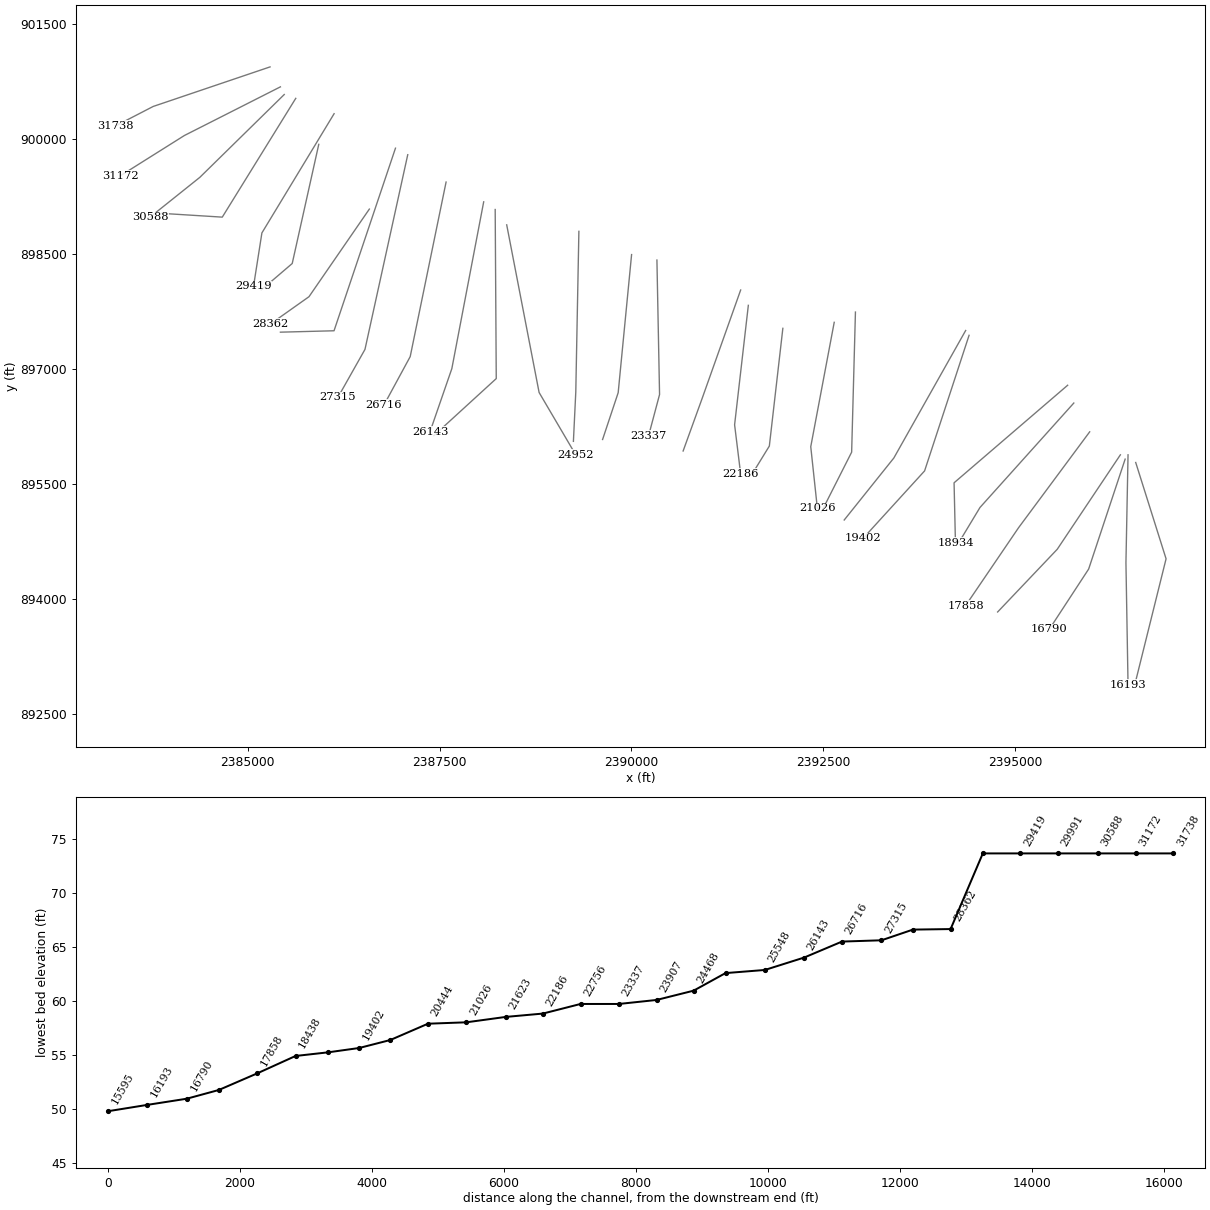
HEC-RAS study BackSwamp.prj: S-16-495 over Back Swamp

--- BackSwamp.g03 (geometry) --- (continued)

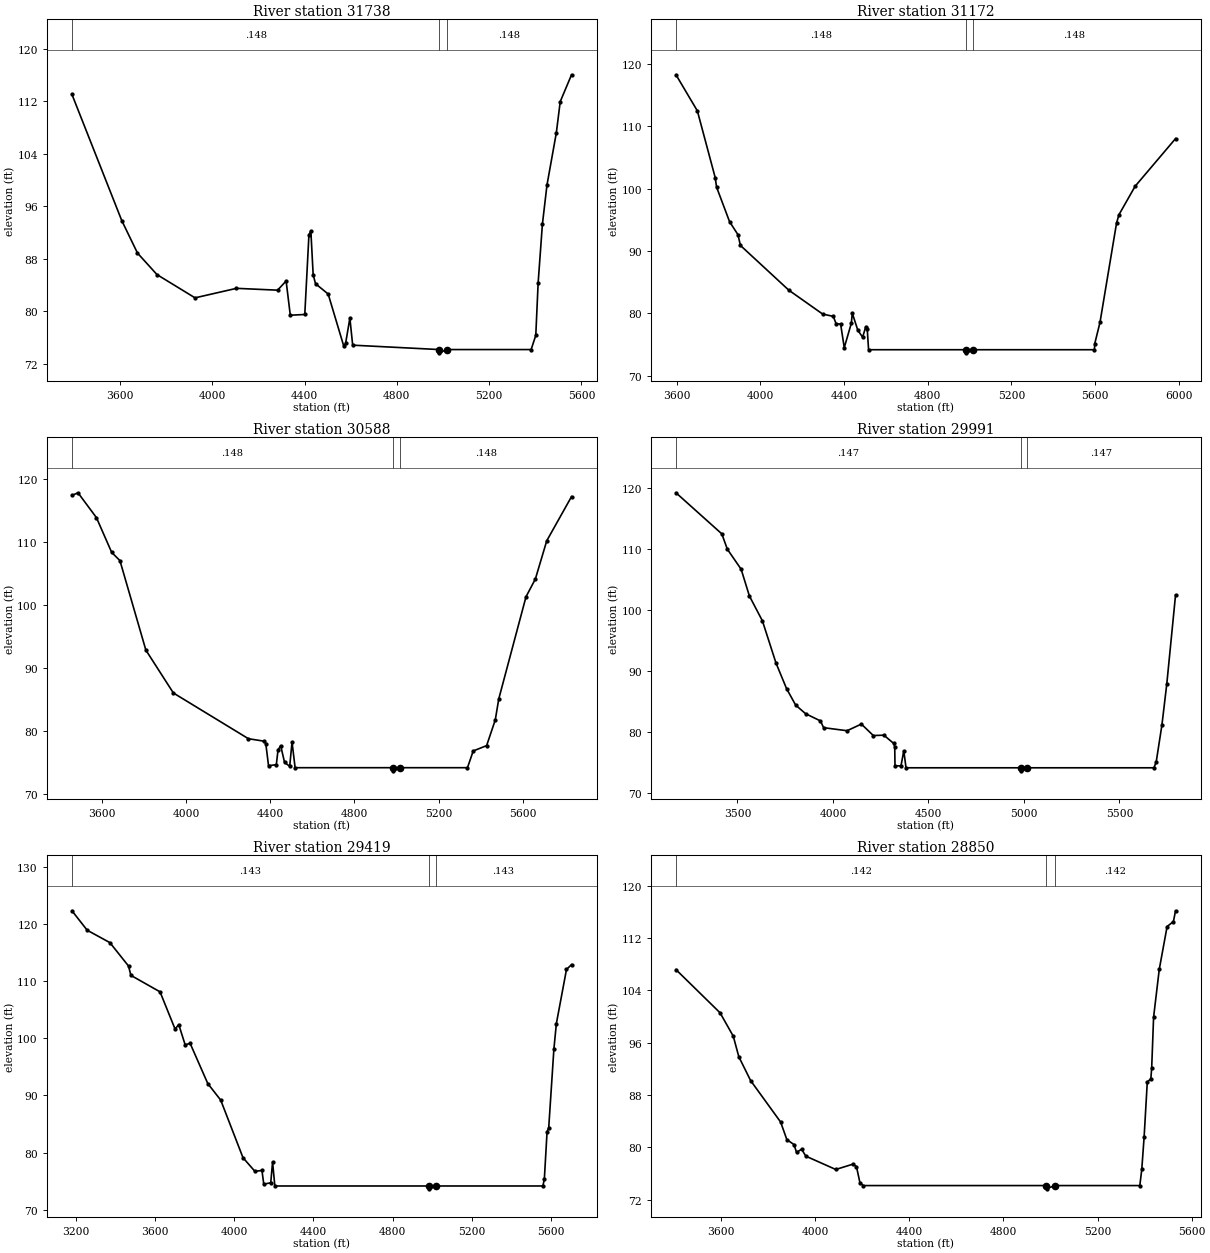
Type RM Length L Ch R = 1 ,31738   ,566,566,566
BEGIN DESCRIPTION:
Back Swamp 41.0
END DESCRIPTION:
XS GIS Cut Line= 3
      2385289.98       900935.29      2383766.76       900419.44
      2383272.04       900163.51
#Sta/Elev= 30
  3391.8  113.07  3607.6   93.83  3675.8   88.87  3760.2   85.59  3925.2   82.04
  4104.9   83.49    4283   83.21    4320   84.61  4338.1   79.39  4400.9    79.5
  4418.9   91.65  4427.2   92.26  4437.2   85.57  4447.4    84.2  4502.3   82.62
  4569.7   74.69  4577.9    75.1  4596.3   78.95  4608.5   74.82  4983.7   74.15
  4984.3   73.65  5016.3   74.15  5381.9   74.15  5402.1   76.32  5412.3   84.32
  5430.7   93.25  5450.6   99.25  5491.1   107.2    5508  111.97    5557  116.07
#Mann= 3 ,-1,0
  3391.8    .148       0  4983.7    .049       0  5016.3    .148       0
Bank Sta=4983.7,5016.3
XS Rating Curve= 0 ,0
Exp/Cntr=0.3,0.1

Type RM Length L Ch R = 1 ,31172   ,584,584,584
BEGIN DESCRIPTION:
Back Swamp 40.0
END DESCRIPTION:
XS GIS Cut Line= 3
      2385424.99         900675.      2384173.56       900040.48
      2383339.82       899515.97
#Sta/Elev= 30
  3596.9  118.26  3699.1  112.47  3784.3  101.78    3791  100.23  3853.1   94.69
  3893.1   92.61    3905   90.88  4136.4    83.7  4298.1   79.87    4349    79.5
  4362.2   78.33    4384   78.26  4401.3   74.48  4435.1   78.39  4439.8      80
  4466.2   77.27  4489.1   76.16  4504.4   77.86  4511.1   77.51  4517.6   74.15
  4983.7   74.15  4984.2   73.65  5016.4   74.15  5597.3   74.15  5598.7   75.11
  5623.9   78.55    5703   94.47  5714.3    95.8  5791.7  100.37    5985  108.02
#Mann= 3 ,-1,0
  3596.9    .148       0  4983.7    .049       0  5016.4    .148       0
Bank Sta=4983.7,5016.4
XS Rating Curve= 0 ,0
Exp/Cntr=0.3,0.1

Type RM Length L Ch R = 1 ,30588   ,597,597,597
BEGIN DESCRIPTION:
Back Swamp 39.0
END DESCRIPTION:
XS GIS Cut Line= 3
      2385474.98       900574.98      2384374.48       899494.56
      2383725.02       898975.02
#Sta/Elev= 30
  3457.8  117.45  3486.5  117.87  3573.9  113.93  3646.6  108.39  3685.8  107.08
    3809   92.85  3939.8   86.03  4296.3   78.76  4371.8   78.36    4379   77.96
  4391.9   74.47  4428.9   74.63  4437.1   76.98  4449.7   77.65  4467.9      75
  4492.5   74.37  4503.6   78.22  4518.2   74.15  4983.7   74.15  4984.2   73.65
  5016.4   74.15  5337.3   74.15  5364.5   76.81  5428.2   77.66  5469.4   81.75
  5485.8   85.07  5615.5  101.34  5659.9  104.16    5714  110.24  5831.7  117.26
#Mann= 3 ,-1,0
  3457.8    .148       0  4983.7    .049       0  5016.4    .148       0
Bank Sta=4983.7,5016.4
XS Rating Curve= 0 ,0
Exp/Cntr=0.3,0.1

Type RM Length L Ch R = 1 ,29991   ,572,572,572
BEGIN DESCRIPTION:
Back Swamp 38.0
END DESCRIPTION:
XS GIS Cut Line= 3
        2385625.         900525.      2384667.18       898975.55
      2383875.03         899025.
#Sta/Elev= 30
  3178.4  119.26  3418.4  112.52  3447.2  110.01  3519.5  106.72  3562.8  102.33
  3630.9   98.25  3701.9   91.34  3757.1   87.15    3805   84.43  3857.1   83.02
  3934.6   81.84  3951.3   80.73    4074   80.23    4149   81.32  4211.5   79.44
  4266.8    79.5  4318.3   78.14  4323.6   77.61    4325   74.47  4356.4   74.47
    4371   76.95  4382.7   74.15  4983.6   74.15  4984.1   73.65  5016.5   74.15
  5680.5   74.15  5692.4    75.1  5722.4   81.17    5748   87.95  5793.7  102.49
#Mann= 3 ,-1,0
  3178.4    .147       0  4983.6    .049       0  5016.5    .147       0
Bank Sta=4983.6,5016.5
XS Rating Curve= 0 ,0
Exp/Cntr=0.3,0.1

Type RM Length L Ch R = 1 ,29419   ,569,569,569
BEGIN DESCRIPTION:
Back Swamp 37.0
END DESCRIPTION:
XS GIS Cut Line= 3
      2386124.98       900324.96      2385183.71        898769.6
      2385074.99       898074.96
#Sta/Elev= 30
    3182  122.29  3258.8  118.89  3373.4  116.72  3467.4  112.63  3479.5  110.99
  3626.5  108.11  3702.4  101.59  3720.9  102.39  3753.1   98.86  3778.4   99.09
  3867.4   92.07  3932.7   89.17  4045.1    79.1  4105.5    76.7  4140.8   76.87
    4150   74.47  4185.2   74.71  4194.4   78.34  4205.9   74.15  4982.9   74.15
  4983.6   73.65  5017.1   74.15  5558.5   74.15  5565.9   75.33  5579.7   83.65
    5588   84.33  5614.1   98.09  5626.6  102.56  5677.7  112.03  5703.1  112.87
#Mann= 3 ,-1,0
    3182    .143       0  4982.9    .048       0  5017.1    .143       0
Bank Sta=4982.9,5017.1
XS Rating Curve= 0 ,0
Exp/Cntr=0.3,0.1

Type RM Length L Ch R = 1 ,28850   ,488,488,488
BEGIN DESCRIPTION:
Back Swamp 36.0
END DESCRIPTION:
XS GIS Cut Line= 3
      2385924.99       899924.97      2385578.96       898370.62
      2385175.03       898025.02
#Sta/Elev= 30
  3407.6  107.18  3594.9  100.58  3651.2      97  3674.7   93.86  3724.9   90.21
  3852.5   83.87    3879   81.18  3909.4   80.42  3920.2   79.23  3941.7   79.71
  3959.7   78.65    4087   76.61  4160.4   77.43    4175   77.04  4189.7   74.59
  4203.8   74.15  4982.9   74.15  4983.6   73.65  5017.2   74.15  5379.7   74.15
    5388   76.62  5397.9   81.53  5411.4   89.96  5426.7   90.52  5430.2   92.18
  5438.3   99.92  5462.4  107.23  5495.7  113.77  5522.6  114.54  5531.6  116.18
#Mann= 3 ,-1,0
  3407.6    .142       0  4982.9    .048       0  5017.2    .142       0
Bank Sta=4982.9,5017.2
XS Rating Curve= 0 ,0
Exp/Cntr=0.3,0.1

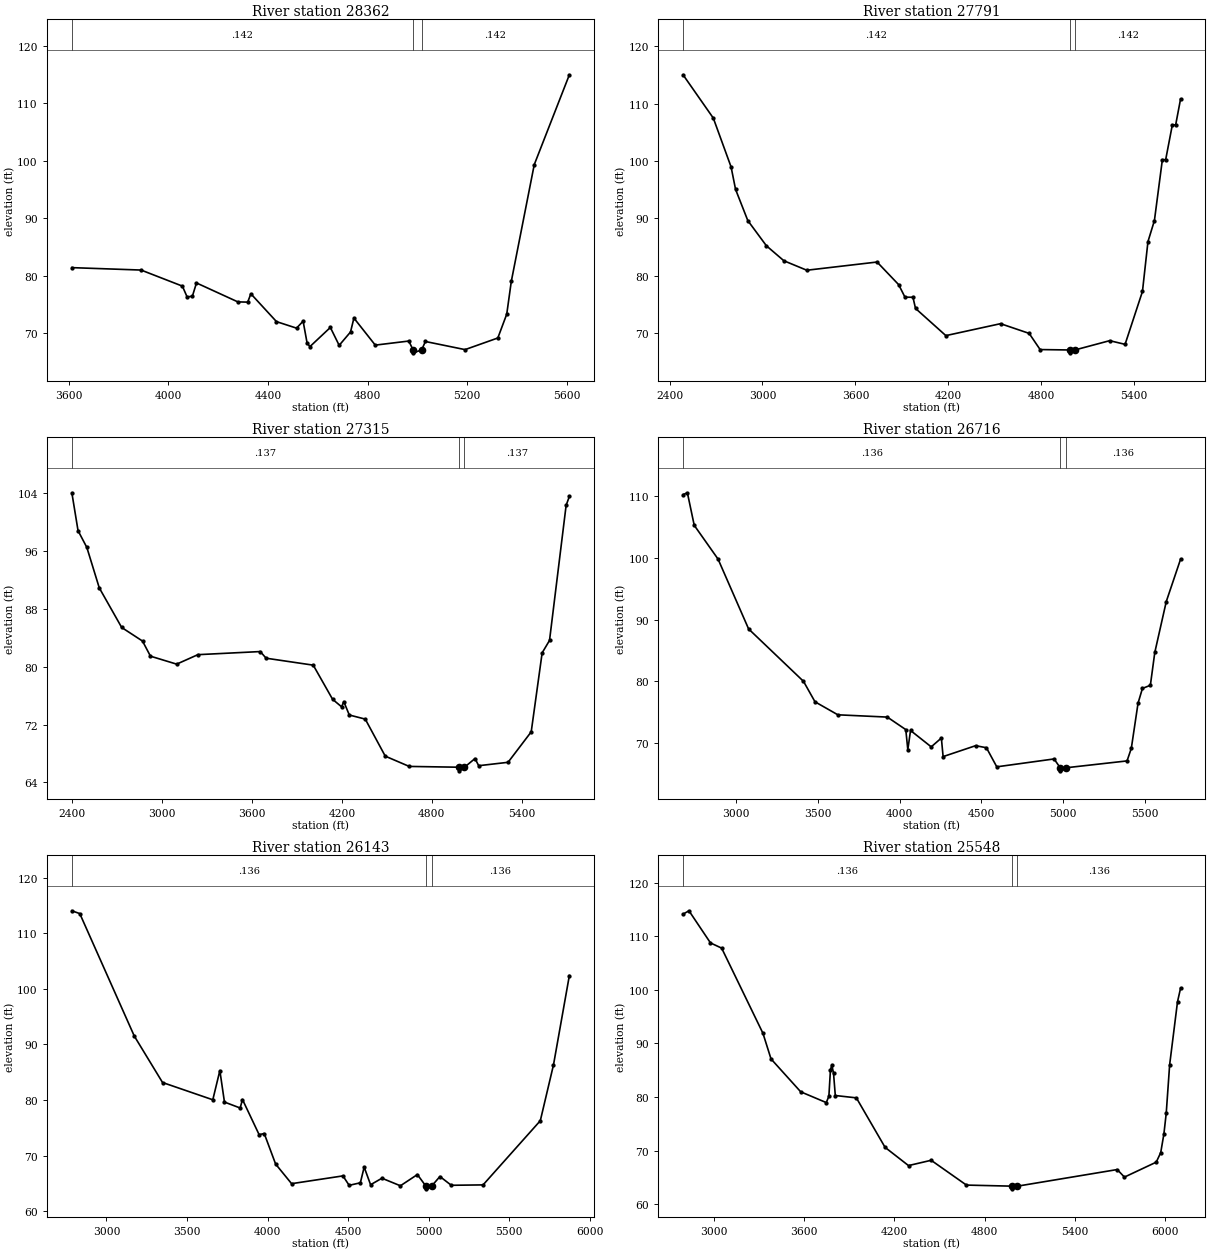
Type RM Length L Ch R = 1 ,28362   ,571,571,571
BEGIN DESCRIPTION:
Back Swamp 35.0
END DESCRIPTION:
XS GIS Cut Line= 3
      2386584.41       899080.47       2385797.5       897937.58
      2385299.37       897584.61
#Sta/Elev= 30
  3612.4   81.44  3890.4   81.02  4056.3   78.23  4075.3   76.35  4096.5   76.48
  4112.9   78.78  4279.1   75.49  4318.7   75.45  4331.3    76.9  4434.3   72.06
  4514.8   70.93  4541.2   72.14  4556.9   68.41  4568.3   67.71  4650.6   71.05
    4686   67.94  4731.6   70.26  4745.2   72.68    4831   67.98  4965.8   68.69
  4982.9   67.14  4983.5   66.64  5017.2   67.14  5032.3   68.61  5191.6    67.2
  5323.2   69.22    5359   73.36  5377.3   79.05  5469.5   99.33  5610.5  114.94
#Mann= 3 ,-1,0
  3612.4    .142       0  4982.9    .048       0  5017.2    .142       0
Bank Sta=4982.9,5017.2
XS Rating Curve= 0 ,0
Exp/Cntr=0.3,0.1

Type RM Length L Ch R = 1 ,27791   ,476,476,476
BEGIN DESCRIPTION:
Back Swamp 34.0
END DESCRIPTION:
XS GIS Cut Line= 3
        2386925.         899875.      2386124.03       897493.28
      2385424.97         897475.
#Sta/Elev= 30
  2487.2  115.03  2682.7  107.48  2797.4   98.98  2826.3   95.07  2905.4   89.63
  3025.5   85.24  3138.3   82.63  3286.3   80.98    3740   82.41  3879.3   78.47
    3920   76.29  3971.7   76.27  3988.1   74.33  4184.1   69.59  4537.2   71.67
  4721.8   69.98  4792.7   67.16  4982.8   67.09  4983.5   66.59  5017.2   67.09
  5241.8   68.71  5341.2   68.07  5453.4   77.28  5488.9   85.96  5530.6   89.63
    5582  100.24  5603.4  100.25  5646.3  106.29  5667.8   106.3  5699.3  110.78
#Mann= 3 ,-1,0
  2487.2    .142       0  4982.8    .048       0  5017.2    .142       0
Bank Sta=4982.8,5017.2
XS Rating Curve= 0 ,0
Exp/Cntr=0.3,0.1

Type RM Length L Ch R = 1 ,27315   ,599,599,599
BEGIN DESCRIPTION:
Back Swamp 33.0
END DESCRIPTION:
XS GIS Cut Line= 3
        2387085.       899789.94      2386527.28       897249.94
        2386175.         896625.
#Sta/Elev= 30
  2399.5  104.04  2440.8    98.8  2499.5   96.48  2582.4   90.89  2731.8   85.42
  2870.7   83.54  2923.8   81.45  3098.5   80.35    3240   81.66    3656   82.09
  3695.2   81.17  4009.3   80.21  4138.4   75.49  4198.4   74.45  4213.1   75.17
  4249.7   73.32  4356.3   72.75  4489.6   67.63  4649.5   66.21    4982    66.1
  4982.9    65.6    5018    66.1  5088.1    67.3  5112.7   66.31  5308.6   66.78
    5463   70.99  5535.9   81.91  5585.1   83.63  5695.9  102.31  5717.4  103.53
#Mann= 3 ,-1,0
  2399.5    .137       0    4982    .047       0    5018    .137       0
Bank Sta=4982,5018
XS Rating Curve= 0 ,0
Exp/Cntr=0.3,0.1

Type RM Length L Ch R = 1 ,26716   ,573,573,573
BEGIN DESCRIPTION:
Back Swamp 32.0
END DESCRIPTION:
XS GIS Cut Line= 3
      2387584.75         899433.        2387117.       897156.04
      2386774.98       896524.97
#Sta/Elev= 30
  2675.5  110.29  2702.1  110.59    2744  105.31  2889.7   99.83  3076.5    88.5
  3412.1      80  3482.5   76.68  3622.2   74.57  3924.7    74.2  4037.6   72.17
  4050.1   68.91  4066.7   72.03  4193.2   69.37  4255.2    70.8  4265.9   67.79
  4464.6   69.56  4530.7   69.23  4594.1   66.13  4944.4   67.41    4982   65.98
  4982.8   65.48  5018.1   65.98  5390.7   67.09  5416.8   69.13    5458   76.47
  5484.8   78.85  5533.3   79.36  5560.3   84.68  5630.6   92.95  5717.8    99.8
#Mann= 3 ,-1,0
  2675.5    .136       0    4982    .047       0  5018.1    .136       0
Bank Sta=4982,5018.1
XS Rating Curve= 0 ,0
Exp/Cntr=0.3,0.1

Type RM Length L Ch R = 1 ,26143   ,595,595,595
BEGIN DESCRIPTION:
Back Swamp 31.0
END DESCRIPTION:
XS GIS Cut Line= 3
      2388075.01       899175.04      2387659.88       896999.69
        2387375.       896175.01
#Sta/Elev= 30
  2785.4  114.05  2834.6  113.54  3172.8    91.5  3348.1   83.14    3660   80.03
  3703.8   85.29  3732.3   79.62  3829.8   78.55  3844.1   80.08  3947.3   73.76
  3979.2   73.95  4049.8   68.46  4148.9   64.93  4467.5   66.33  4506.1   64.63
  4575.6   65.09  4599.2   67.91  4639.1   64.74  4709.5   65.91  4824.1   64.55
  4929.5   66.57    4982    64.5  4982.8      64  5018.1    64.5  5069.3   66.22
  5139.9   64.64    5337   64.71  5692.2   76.26    5774   86.31  5872.5  102.39
#Mann= 3 ,-1,0
  2785.4    .136       0    4982    .047       0  5018.1    .136       0
Bank Sta=4982,5018.1
XS Rating Curve= 0 ,0
Exp/Cntr=0.3,0.1

Type RM Length L Ch R = 1 ,25548   ,596,596,596
BEGIN DESCRIPTION:
Back Swamp 30.0
END DESCRIPTION:
XS GIS Cut Line= 3
        2388225.       899074.98      2388238.78       896869.33
      2387425.03       896125.03
#Sta/Elev= 30
  2794.3  114.12  2833.7  114.75  2976.9  108.75  3051.1  107.78  3325.8   91.88
  3379.4    87.1  3576.9   80.96  3746.9   78.95  3764.2   80.13  3774.6   85.06
  3783.8   85.96  3795.1   84.43  3806.9   80.27    3947   79.83    4138   70.59
  4293.7   67.19  4444.3   68.18    4679   63.55  4981.9   63.35  4982.8   62.85
  5018.1   63.35  5681.7   66.45  5729.7   65.04  5941.2   67.83    5971   69.61
  5992.2   73.11  6007.6   76.95  6030.4   86.03  6082.6   97.76  6102.8  100.28
#Mann= 3 ,-1,0
  2794.3    .136       0  4981.9    .047       0  5018.1    .136       0
Bank Sta=4981.9,5018.1
XS Rating Curve= 0 ,0
Exp/Cntr=0.3,0.1

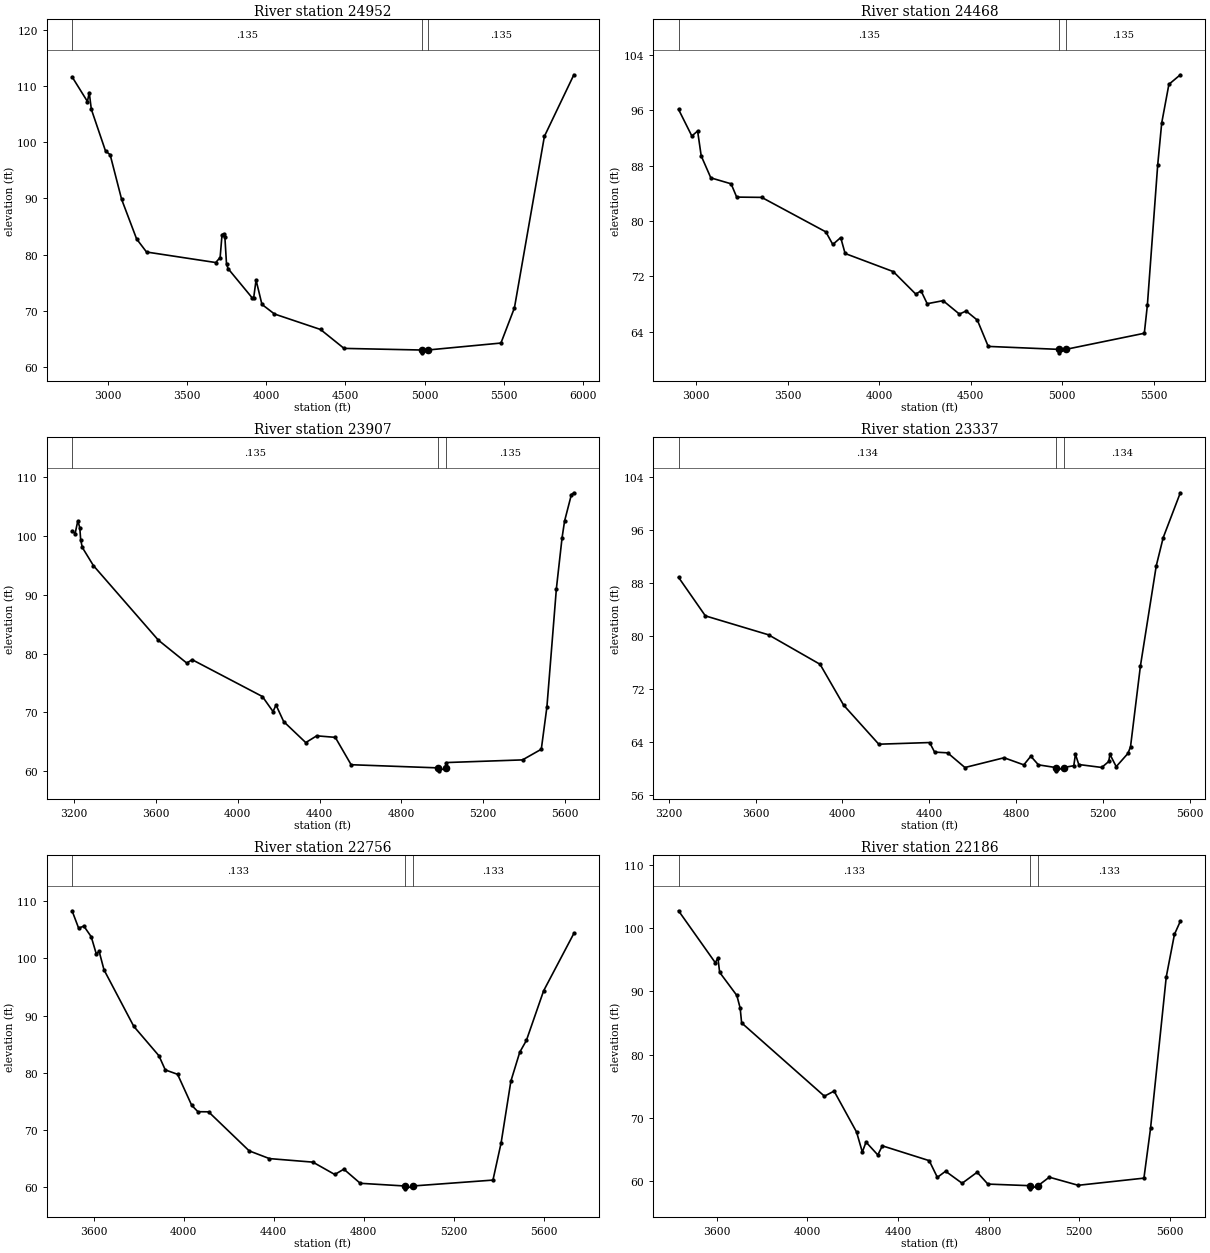
Type RM Length L Ch R = 1 ,24952   ,484,484,484
BEGIN DESCRIPTION:
Back Swamp 29.0
END DESCRIPTION:
XS GIS Cut Line= 3
      2388375.01       898874.96      2388797.49         896688.
      2389275.02       895874.96
#Sta/Elev= 30
  2772.6  111.62  2869.7  107.23    2881  108.82  2894.3  105.85  2984.1   98.42
  3013.1   97.78  3085.6   89.85  3180.4    82.8    3243   80.48  3680.2   78.61
    3708    79.5  3720.1   83.56  3731.9   83.72  3738.1   83.12  3748.3   78.37
  3757.9   77.54  3910.4   72.34  3919.8    72.3  3935.1   75.49  3972.2   71.17
  4051.5   69.46  4342.4   66.71  4490.9   63.35  4981.8   63.06  4982.6   62.56
  5018.3   63.06  5482.2    64.3  5567.4   70.55  5756.8  101.04  5942.9  111.98
#Mann= 3 ,-1,0
  2772.6    .135       0  4981.8    .046       0  5018.3    .135       0
Bank Sta=4981.8,5018.3
XS Rating Curve= 0 ,0
Exp/Cntr=0.3,0.1

Type RM Length L Ch R = 1 ,24468   ,561,561,561
BEGIN DESCRIPTION:
Back Swamp 28.0
END DESCRIPTION:
XS GIS Cut Line= 3
        2389316.       898790.46      2389275.58       896694.35
       2389244.6        896050.8
#Sta/Elev= 30
  2903.5   96.12  2976.2   92.27  3007.7   92.99  3027.3    89.4  3079.9   86.22
  3190.7   85.36  3221.1   83.44  3357.7    83.4  3708.2   78.41  3746.1   76.59
  3789.3   77.59  3813.3   75.29  4076.6   72.67  4199.3   69.42  4228.1   69.89
  4261.7   68.03  4348.4   68.47  4437.7   66.53  4474.4   66.98  4535.8   65.65
  4595.1   61.86  4981.8   61.43  4982.6   60.93  5018.3   61.43  5447.6   63.76
  5464.3   67.82  5520.7   88.08  5542.6   94.15  5581.9   99.74  5644.3  101.12
#Mann= 3 ,-1,0
  2903.5    .135       0  4981.8    .046       0  5018.3    .135       0
Bank Sta=4981.8,5018.3
XS Rating Curve= 0 ,0
Exp/Cntr=0.3,0.1

Type RM Length L Ch R = 1 ,23907   ,570,570,570
BEGIN DESCRIPTION:
Back Swamp 27.0
END DESCRIPTION:
XS GIS Cut Line= 3
      2390003.14       898487.09      2389828.27       896685.65
        2389625.         896075.
#Sta/Elev= 30
  3190.1  100.82    3205   100.4  3218.3  102.56  3227.9  101.38  3232.2   99.33
  3240.2   98.03  3294.6   94.94  3611.9   82.28  3751.1   78.38  3777.1   78.96
  4120.7    72.7  4172.6   70.15  4187.4   71.25  4224.8   68.44  4332.7   64.87
  4386.2   66.02  4477.1   65.76  4554.5   61.11  4981.7   60.57  4982.6   60.07
  5018.3   60.57  5020.6   61.48  5392.6   61.93  5484.4   63.74  5511.8   70.92
  5558.2   91.05  5586.1   99.72  5598.3  102.53  5631.6  107.02  5643.6  107.32
#Mann= 3 ,-1,0
  3190.1    .135       0  4981.7    .046       0  5018.3    .135       0
Bank Sta=4981.7,5018.3
XS Rating Curve= 0 ,0
Exp/Cntr=0.3,0.1

Type RM Length L Ch R = 1 ,23337   ,581,581,581
BEGIN DESCRIPTION:
Back Swamp 26.0
END DESCRIPTION:
XS GIS Cut Line= 3
      2390333.33       898415.64      2390367.74       896661.68
      2390225.01       896125.04
#Sta/Elev= 30
  3245.7   88.83  3369.2   83.03  3659.8   80.18  3897.1   75.74  4005.8   69.58
  4167.4   63.71  4401.3   63.96  4424.3   62.52  4484.2   62.41  4563.8    60.2
  4744.1   61.67  4834.9    60.6  4867.1    61.9  4902.2    60.6  4981.6    60.2
  4982.5    59.7  5018.4    60.2  5064.9   60.47  5072.6   62.19  5087.9   60.65
  5193.6   60.21  5225.9   61.11  5231.2   62.19  5260.2   60.33  5314.1   62.32
    5326   63.31  5371.6   75.48  5444.6   90.58  5476.5   94.81  5555.3  101.56
#Mann= 3 ,-1,0
  3245.7    .134       0  4981.6    .046       0  5018.4    .134       0
Bank Sta=4981.6,5018.4
XS Rating Curve= 0 ,0
Exp/Cntr=0.3,0.1

Type RM Length L Ch R = 1 ,22756   ,570,570,570
BEGIN DESCRIPTION:
Back Swamp 25.0
END DESCRIPTION:
XS GIS Cut Line= 3
        2391425.         898025.      2390924.35       896614.94
        2390675.       895925.01
#Sta/Elev= 30
  3503.7  108.33  3532.8   105.3  3556.1  105.65  3588.8  103.79  3611.4  100.78
  3623.9  101.24  3645.6      98  3777.9   88.12  3889.8   82.97  3917.9    80.5
  3972.6   79.73  4035.3   74.31    4063   73.19  4110.2   73.17  4290.8   66.34
  4380.7   64.99  4573.9   64.37  4671.1   62.21  4711.5   63.14  4784.3   60.67
  4981.5    60.2  4982.4    59.7  5018.6    60.2  5374.1   61.23  5410.5   67.77
  5453.7   78.53  5493.1   83.59  5522.7   85.66  5599.3   94.34  5733.6  104.37
#Mann= 3 ,-1,0
  3503.7    .133       0  4981.5    .046       0  5018.6    .133       0
Bank Sta=4981.5,5018.6
XS Rating Curve= 0 ,0
Exp/Cntr=0.3,0.1

Type RM Length L Ch R = 1 ,22186   ,563,563,563
BEGIN DESCRIPTION:
Back Swamp 24.0
END DESCRIPTION:
XS GIS Cut Line= 3
        2391525.       897825.02      2391345.99       896266.67
        2391425.       895625.01
#Sta/Elev= 30
  3431.4  102.71  3593.7   94.51  3605.2   95.28  3612.9   92.99  3688.8   89.34
  3703.4   87.36  3709.9   85.01  4075.4   73.44  4118.1   74.24  4217.3   67.78
  4242.7   64.62  4259.1   66.19  4311.1   64.16  4331.1    65.6    4538   63.26
    4574   60.62  4610.2   61.59  4683.3   59.69  4749.6   61.43  4796.9   59.56
  4981.5   59.31  4982.4   58.81  5018.6   59.31    5068   60.65  5195.7   59.37
  5485.8    60.5    5515   68.35  5584.4   92.27  5620.5   98.98  5646.5  101.06
#Mann= 3 ,-1,0
  3431.4    .133       0  4981.5    .046       0  5018.6    .133       0
Bank Sta=4981.5,5018.6
XS Rating Curve= 0 ,0
Exp/Cntr=0.3,0.1

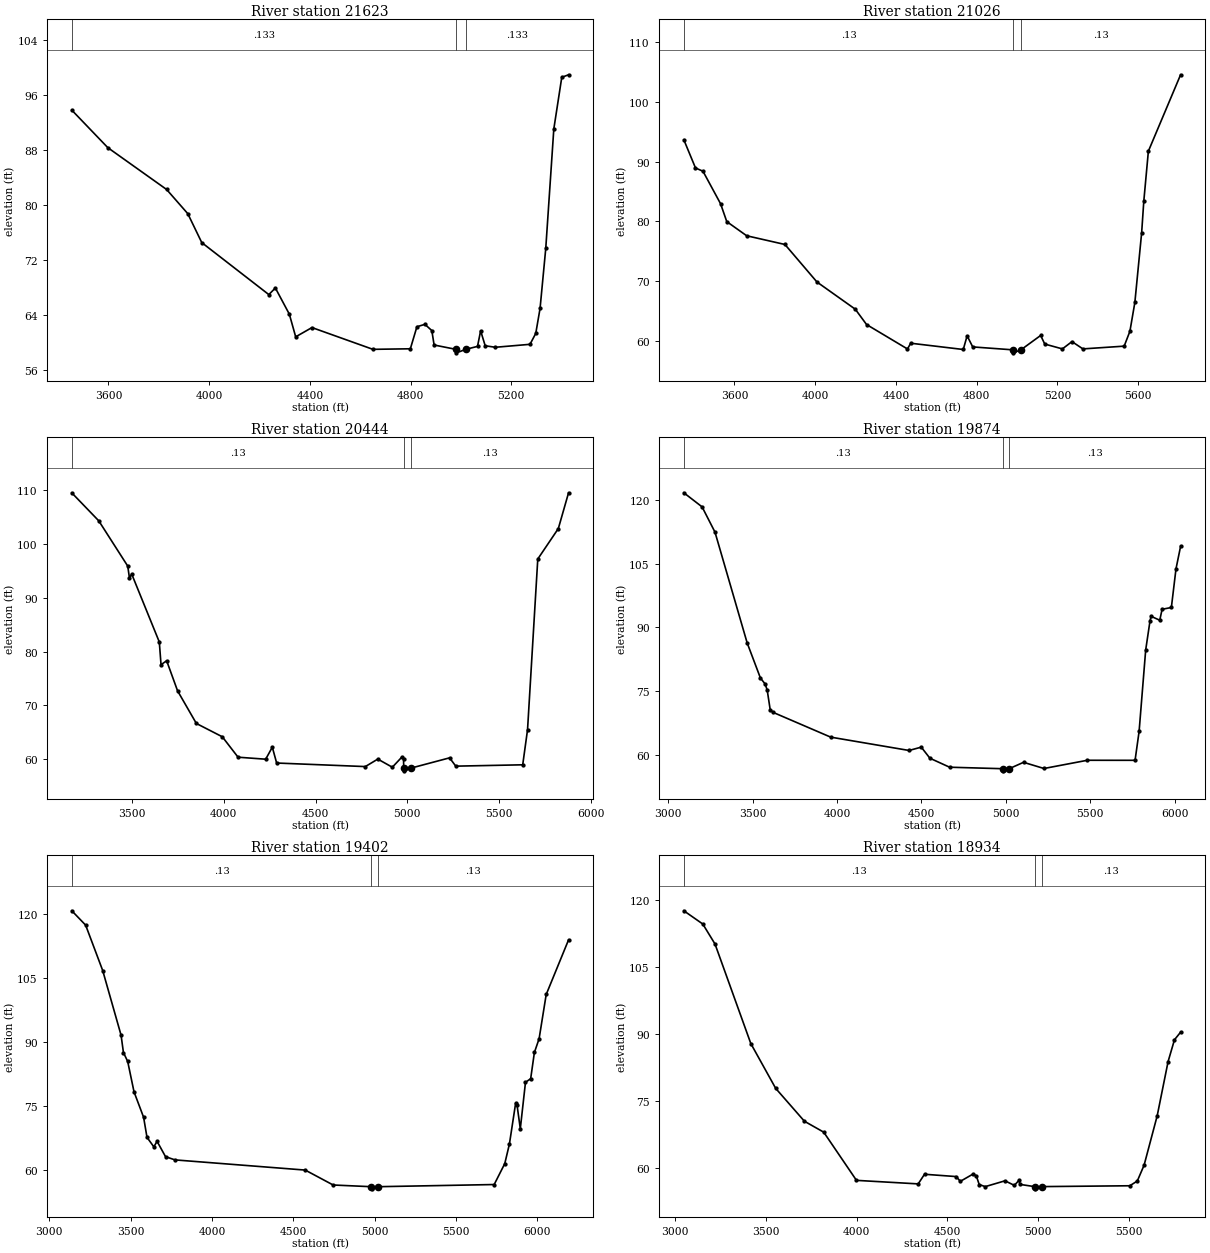
Type RM Length L Ch R = 1 ,21623   ,597,597,597
BEGIN DESCRIPTION:
Back Swamp 23.0
END DESCRIPTION:
XS GIS Cut Line= 3
        2391975.       897525.01      2391798.84       895989.48
      2391575.01       895625.02
#Sta/Elev= 30
  3454.4   93.83  3597.4   88.37    3831   82.28  3915.1   78.76  3970.6   74.55
    4237   66.98    4263   67.94  4318.5   64.13  4343.7   60.83  4408.4   62.18
  4650.5   59.01  4799.2   59.09  4825.3    62.3  4857.1   62.65  4884.5   61.74
  4893.6   59.64  4981.4      59  4982.4    58.5  5018.6      59    5066   59.44
  5078.4   61.71  5096.5   59.53  5136.8   59.31  5274.5   59.74  5297.4   61.33
  5314.5   64.97  5337.1    73.7  5369.1   91.09  5400.7   98.61  5427.7   98.98
#Mann= 3 ,-1,0
  3454.4    .133       0  4981.4    .046       0  5018.6    .133       0
Bank Sta=4981.4,5018.6
XS Rating Curve= 0 ,0
Exp/Cntr=0.3,0.1

Type RM Length L Ch R = 1 ,21026   ,582,582,582
BEGIN DESCRIPTION:
Back Swamp 22.0
END DESCRIPTION:
XS GIS Cut Line= 3
      2392644.63       897603.54      2392338.74       895981.02
        2392425.       895175.03
#Sta/Elev= 30
  3348.9   93.67  3406.7   88.95  3443.8    88.4    3531   82.96  3561.7   79.97
  3660.3    77.6    3850   76.14  4008.6   69.86  4198.7    65.3  4254.4   62.74
  4457.1   58.65  4473.3   59.61  4733.7   58.56  4752.8   60.85  4780.5   58.99
  4980.7    58.5  4981.7      58  5019.3    58.5  5117.2   60.91  5137.5   59.47
  5224.9   58.66  5272.4   59.88  5326.6   58.66  5531.1   59.12  5559.5   61.61
    5584   66.43  5617.7   78.11  5628.3   83.37    5651   91.76  5810.6  104.55
#Mann= 3 ,-1,0
  3348.9     .13       0  4980.7    .045       0  5019.3     .13       0
Bank Sta=4980.7,5019.3
XS Rating Curve= 0 ,0
Exp/Cntr=0.3,0.1

Type RM Length L Ch R = 1 ,20444   ,570,570,570
BEGIN DESCRIPTION:
Back Swamp 21.0
END DESCRIPTION:
XS GIS Cut Line= 3
      2392921.28       897737.41      2392871.76       895909.48
        2392475.       895125.01
#Sta/Elev= 30
  3171.4  109.45  3318.4  104.26  3476.3   95.86  3485.7   93.61  3497.6   94.41
  3648.3   81.78  3657.7   77.56  3688.3    78.3  3747.9   72.71  3850.3   66.66
  3991.7   64.19  4077.6    60.4  4228.1   60.03  4264.3   62.26  4287.9   59.32
  4771.3   58.66  4839.3   60.05  4918.4   58.54  4971.4   60.46  4979.5   60.08
  4980.7   58.37  4981.7   57.87  5019.3   58.37  5230.5   60.28  5264.3   58.74
  5629.2   58.99  5655.5   65.51  5711.3   97.18  5823.3  102.83  5879.1  109.47
#Mann= 3 ,-1,0
  3171.4     .13       0  4980.7    .045       0  5019.3     .13       0
Bank Sta=4980.7,5019.3
XS Rating Curve= 0 ,0
Exp/Cntr=0.3,0.1

Type RM Length L Ch R = 1 ,19874   ,472,472,472
BEGIN DESCRIPTION:
Back Swamp 20.0
END DESCRIPTION:
XS GIS Cut Line= 3
      2394358.01       897496.45      2393421.79       895833.47
      2392774.98       895024.97
#Sta/Elev= 30
  3091.6  121.61  3199.8   118.3  3276.3  112.37  3466.9   86.38  3545.5   78.14
  3573.5   76.73  3585.7   75.31  3603.3   70.74  3619.4    70.1  3961.8   64.27
  4426.2   61.14  4498.7   61.92  4549.9   59.32  4666.6   57.21  4980.5   56.86
  4981.5   56.36  5019.6   56.86  5104.8   58.36  5225.9   56.91  5482.9   58.84
  5765.7   58.83  5789.6    65.6  5828.6   84.71  5854.4   91.59  5860.9   92.62
    5912    91.7  5925.9   94.27  5980.8   94.69  6008.3  103.78  6035.4  109.02
#Mann= 3 ,-1,0
  3091.6     .13       0  4980.5    .045       0  5019.6     .13       0
Bank Sta=4980.5,5019.6
XS Rating Curve= 0 ,0
Exp/Cntr=0.3,0.1

Type RM Length L Ch R = 1 ,19402   ,468,468,468
BEGIN DESCRIPTION:
Back Swamp 19.0
END DESCRIPTION:
XS GIS Cut Line= 3
      2394402.64       897433.98      2393822.74       895665.22
      2393019.44        894783.6
#Sta/Elev= 30
  3138.6  120.85  3223.6  117.48  3328.6  106.82  3441.4   91.67    3456   87.59
  3482.1   85.51  3521.1   78.37    3580    72.4  3600.8    67.7  3642.9   65.47
  3662.7   66.77  3714.7   63.17  3772.8   62.41  4573.7   60.02  4745.3   56.52
  4980.5   56.12  4981.5   55.62  5019.6   56.12  5735.4   56.63  5800.5   61.54
    5829   66.12  5867.2   75.69  5875.9   75.27    5896   69.72  5927.8   80.61
  5959.7   81.46  5982.6   87.61  6011.6   90.84  6055.2  101.21  6192.7  114.03
#Mann= 3 ,-1,0
  3138.6     .13       0  4980.5    .045       0  5019.6     .13       0
Bank Sta=4980.5,5019.6
XS Rating Curve= 0 ,0
Exp/Cntr=0.3,0.1

Type RM Length L Ch R = 1 ,18934   ,496,496,496
BEGIN DESCRIPTION:
Back Swamp 18.0
END DESCRIPTION:
XS GIS Cut Line= 3
      2395687.74       896782.61      2394207.09       895510.15
        2394225.       894724.96
#Sta/Elev= 30
  3047.7  117.58  3152.2  114.61  3219.5  110.13  3416.9    87.8    3554   77.75
  3712.3   70.38  3818.7   67.93  3999.2   57.12  4339.3   56.33  4374.1   58.49
  4548.7   57.97  4571.5    56.9  4639.6   58.49  4659.2   58.18  4675.6   56.18
    4709   55.72  4817.7   57.02  4869.2      56  4895.6   57.16  4899.6   56.22
  4980.5   55.72  4981.5   55.22  5019.6   55.72  5505.5   55.91  5546.8   56.97
  5584.2   60.51  5656.3   71.56  5716.6   83.76  5751.7   88.65  5785.4   90.35
#Mann= 3 ,-1,0
  3047.7     .13       0  4980.5    .045       0  5019.6     .13       0
Bank Sta=4980.5,5019.6
XS Rating Curve= 0 ,0
Exp/Cntr=0.3,0.1

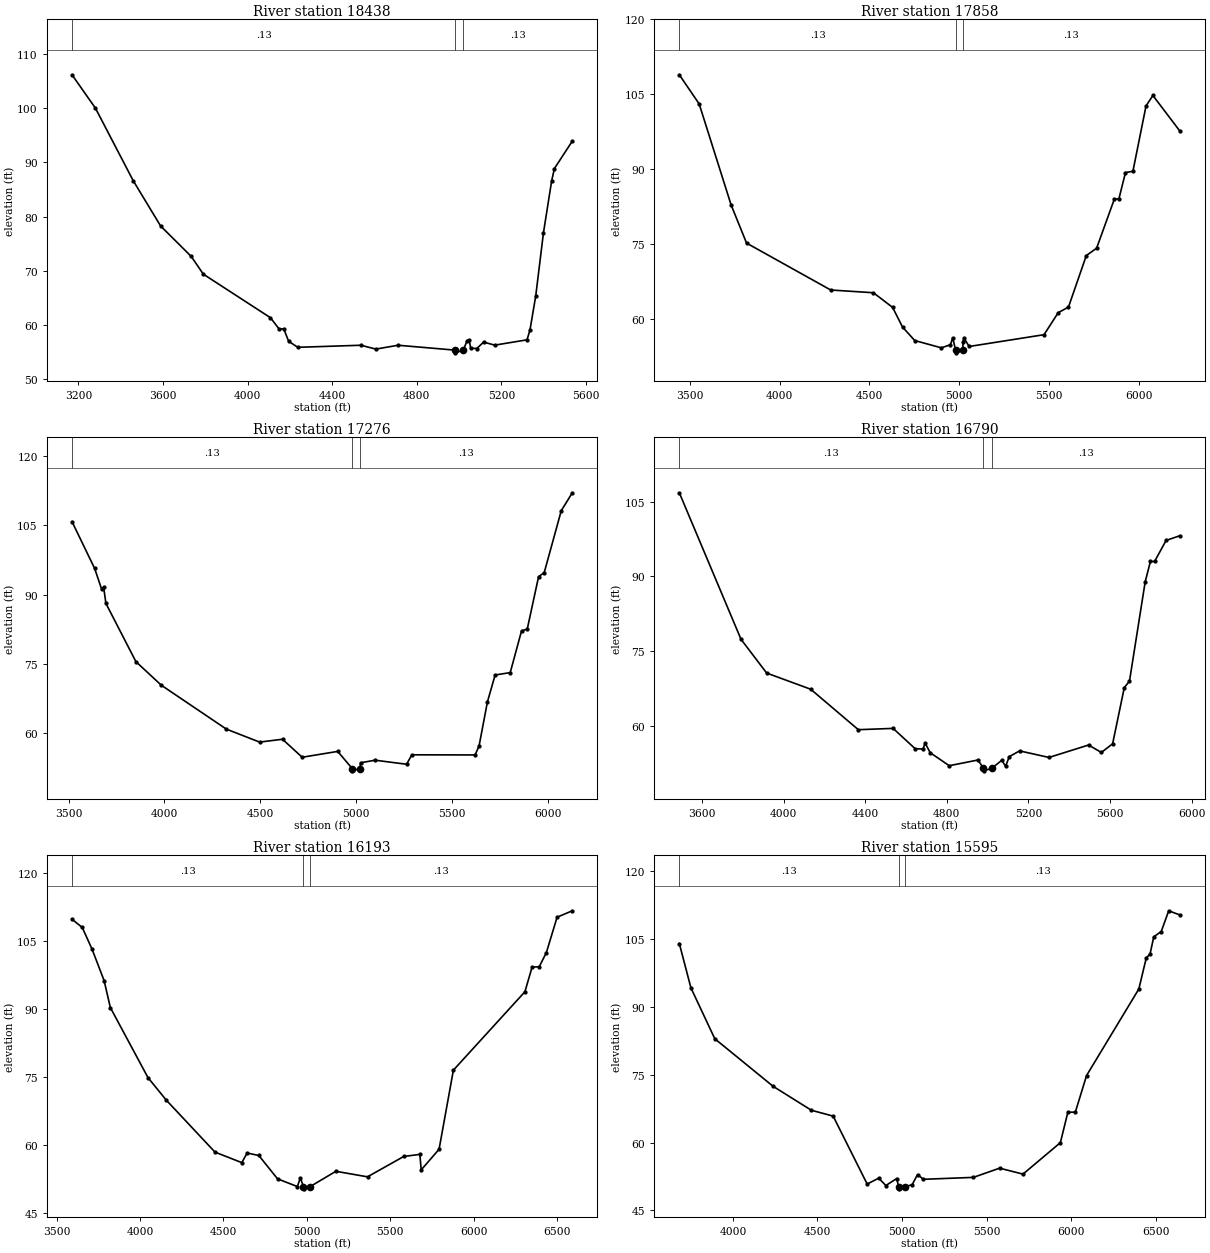
Type RM Length L Ch R = 1 ,18438   ,580,580,580
BEGIN DESCRIPTION:
Back Swamp 17.0
END DESCRIPTION:
XS GIS Cut Line= 3
      2395768.02       896550.55      2394545.01       895188.31
      2394268.77       894730.02
#Sta/Elev= 30
  3169.3  106.17  3280.2  100.01    3459   86.62  3588.2   78.29    3733   72.67
  3790.4   69.39  4107.8   61.36    4149   59.26  4170.6   59.33  4193.8   57.01
    4237    55.9  4535.6   56.28  4606.2   55.57  4711.3   56.28  4980.4   55.38
  4981.4   54.88  5019.6   55.38  5037.8   57.13  5047.8   57.21  5054.6   55.74
  5083.5   55.68  5115.8   56.86  5168.4    56.3    5321   57.28    5335   59.08
  5362.4   65.41  5398.7      77  5437.3   86.54  5450.5   88.87  5535.1   93.93
#Mann= 3 ,-1,0
  3169.3     .13       0  4980.4    .045       0  5019.6     .13       0
Bank Sta=4980.4,5019.6
XS Rating Curve= 0 ,0
Exp/Cntr=0.3,0.1

Type RM Length L Ch R = 1 ,17858   ,582,582,582
BEGIN DESCRIPTION:
Back Swamp 16.0
END DESCRIPTION:
XS GIS Cut Line= 3
      2395975.03       896175.03      2395047.27       894923.38
      2394358.06       893909.09
#Sta/Elev= 30
    3442  108.89  3552.5  103.06  3730.2   82.86  3816.2   75.22  4284.6   65.84
  4522.3   65.29  4629.1   62.36  4684.2   58.43  4752.3   55.73  4900.7   54.27
  4951.1    54.9  4963.4   56.28    4980   53.77    4981   53.27    5020   53.77
  5020.7   55.45  5025.6   56.26  5055.2   54.54  5471.7    56.9  5550.9   61.31
  5607.8   62.42  5707.2   72.74  5764.4    74.2  5862.7   83.98  5888.7   84.11
  5925.1   89.34  5966.4   89.58  6039.5  102.67  6077.7  104.75  6226.3    97.7
#Mann= 3 ,-1,0
    3442     .13       0    4980    .045       0    5020     .13       0
Bank Sta=4980,5020
XS Rating Curve= 0 ,0
Exp/Cntr=0.3,0.1

Type RM Length L Ch R = 1 ,17276   ,486,486,486
BEGIN DESCRIPTION:
Back Swamp 15.0
END DESCRIPTION:
XS GIS Cut Line= 3
      2396374.98       895874.97      2395551.91       894642.78
      2394774.99       893824.99
#Sta/Elev= 30
  3518.2  105.84  3636.4   95.67  3672.4   91.21  3683.3    91.6  3695.1   88.08
  3851.6   75.44  3983.8   70.33  4323.4   60.79  4496.9   57.97  4616.4   58.59
    4719   54.68  4904.4   55.95    4980   52.23    4981   51.73    5020   52.23
  5023.4   53.48  5099.3   54.04  5263.7   53.16    5291   55.21  5621.1   55.18
  5641.8   57.14  5685.3    66.7  5725.5   72.54  5804.3   73.06  5863.4   82.13
    5893   82.49  5952.2   93.88  5981.7   94.78  6070.5  108.21    6128   112.1
#Mann= 3 ,-1,0
  3518.2     .13       0    4980    .045       0    5020     .13       0
Bank Sta=4980,5020
XS Rating Curve= 0 ,0
Exp/Cntr=0.3,0.1

Type RM Length L Ch R = 1 ,16790   ,597,597,597
BEGIN DESCRIPTION:
Back Swamp 14.0
END DESCRIPTION:
XS GIS Cut Line= 3
      2396437.32       895818.78      2395961.46       894384.77
      2395446.78       893596.76
#Sta/Elev= 30
  3489.1   106.8  3791.4   77.36  3917.2   70.57  4133.1   67.32  4366.5   59.19
  4537.1   59.45  4644.9   55.37    4684    55.3  4693.6   56.51  4718.9   54.56
  4812.1   51.95    4953    53.1    4980   51.42    4981   50.92  5020.1   51.42
  5069.7   53.04  5088.3   51.83  5106.4   53.78  5156.9   54.93  5300.9   53.61
  5495.1   56.11  5557.7   54.61  5612.9   56.36    5670   67.63  5695.6   68.97
  5772.5   88.91  5798.1      93  5818.6      93  5874.9   97.22  5941.2   98.15
#Mann= 3 ,-1,0
  3489.1     .13       0    4980    .045       0  5020.1     .13       0
Bank Sta=4980,5020.1
XS Rating Curve= 0 ,0
Exp/Cntr=0.3,0.1

Type RM Length L Ch R = 1 ,16193   ,598,598,598
BEGIN DESCRIPTION:
Back Swamp 13.0
END DESCRIPTION:
XS GIS Cut Line= 3
        2396475.       895874.95      2396447.59       894466.72
        2396475.       892874.95
#Sta/Elev= 30
  3591.5  109.82    3653  108.01  3711.9  103.21  3784.2   96.28  3821.5   90.34
  4047.3   74.88  4157.4    69.9  4449.3   58.45  4610.1   56.13  4641.9   58.25
  4711.9   57.71  4824.4   52.55  4943.4   50.85  4960.9   52.78  4979.9   50.85
  4980.9   50.35  5020.1   50.85  5174.1   54.22  5363.9      53  5581.1   57.49
  5677.7   57.95  5685.9   54.53  5793.1   59.08  5878.9   76.53  6307.9   93.83
  6350.8   99.25  6393.7   99.35  6436.6  102.46  6500.9  110.27    6592  111.69
#Mann= 3 ,-1,0
  3591.5     .13       0  4979.9    .045       0  5020.1     .13       0
Bank Sta=4979.9,5020.1
XS Rating Curve= 0 ,0
Exp/Cntr=0.3,0.1

Type RM Length L Ch R = 1 ,15595   ,593,593,593
BEGIN DESCRIPTION:
Back Swamp 12.0
END DESCRIPTION:
XS GIS Cut Line= 3
      2396575.01       895774.98      2396970.79       894518.54
      2396574.99       892924.96
#Sta/Elev= 30
  3682.7  103.97  3751.4   94.17  3892.5   82.93    4237   72.43  4463.7   67.13
  4592.7   65.83  4793.9   50.82  4862.3   52.12  4904.4   50.49  4968.5   52.04
  4979.9   50.26  4980.9   49.76  5020.2   50.26    5060   50.67  5091.8   52.92
  5126.5   51.87  5421.6   52.29  5577.5   54.33  5715.5   53.01  5936.8   59.97
    5981    66.7  6025.2    66.7  6091.5   74.79  6400.8   93.92    6445  100.81
  6467.1  101.64  6489.2  105.46  6533.4  106.63  6577.6  111.21    6642  110.31
#Mann= 3 ,-1,0
  3682.7     .13       0  4979.9    .045       0  5020.2     .13       0
Bank Sta=4979.9,5020.2
XS Rating Curve= 0 ,0
Exp/Cntr=0.3,0.1