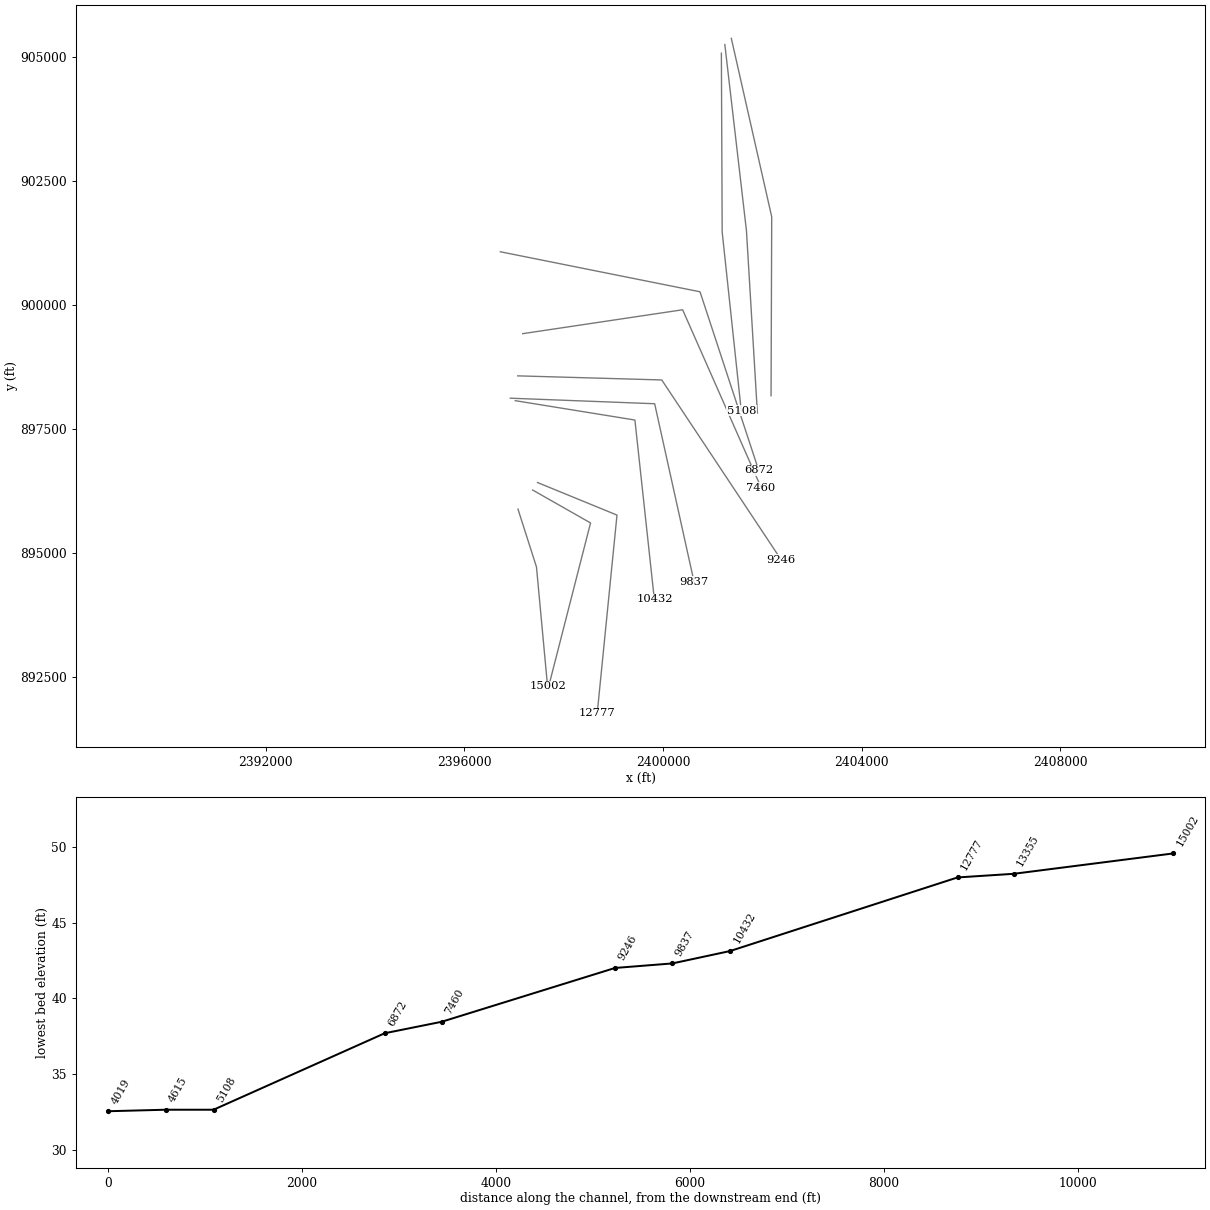
HEC-RAS study BackSwamp.prj: S-16-495 over Back Swamp

--- BackSwamp.g03 (geometry) --- (continued)

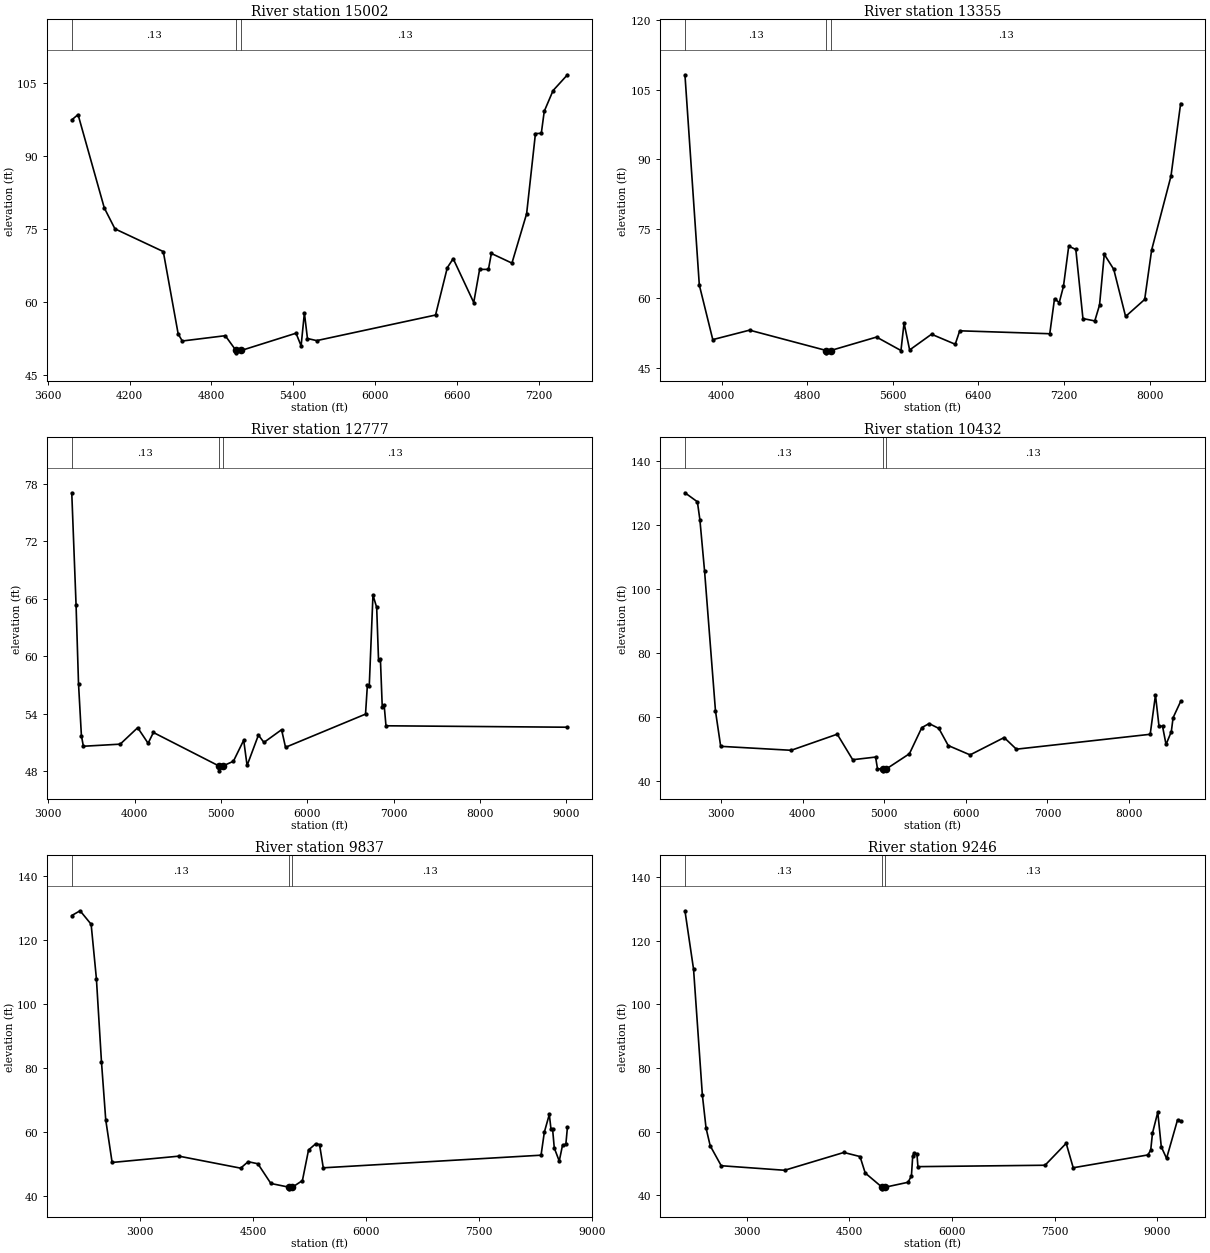
Type RM Length L Ch R = 1 ,15002   ,1647,1647,1647
BEGIN DESCRIPTION:
Back Swamp 11.0
END DESCRIPTION:
XS GIS Cut Line= 3
      2397079.84       895890.19      2397452.37       894724.57
        2397675.       892324.98
#Sta/Elev= 30
  3776.3   97.42  3822.4   98.51  4014.8   79.34  4092.9   75.05  4447.2   70.39
  4556.4   53.47  4586.4   52.03  4901.6   53.12  4979.9    50.1  4980.9    49.6
  5020.2    50.1  5420.3   53.63  5457.5   51.03  5481.6   57.79    5504   52.54
    5572   52.11    6443   57.36  6529.2   67.08  6572.3   68.93    6723   59.93
  6766.1   66.73  6830.7   66.73  6852.2      70    7003   68.02  7110.7   78.16
  7175.3   94.61  7218.3   94.66  7239.9   99.19  7304.5  103.44  7409.9  106.68
#Mann= 3 ,-1,0
  3776.3     .13       0  4979.9    .045       0  5020.2     .13       0
Bank Sta=4979.9,5020.2
XS Rating Curve= 0 ,0
Exp/Cntr=0.3,0.1

Type RM Length L Ch R = 1 ,13355   ,578,578,578
BEGIN DESCRIPTION:
Back Swamp 10.0
END DESCRIPTION:
XS GIS Cut Line= 3
      2397375.01       896274.99      2398540.98       895611.58
        2397725.       892424.99
#Sta/Elev= 30
  3658.5  108.19  3792.7   62.87  3918.5    51.1  4262.3   53.14  4979.7   48.75
  4980.7   48.25  5020.3   48.75  5448.5   51.65  5676.6   48.75  5705.5   54.69
  5757.6   48.87  5962.2   52.26  6183.6    50.1  6225.6      53  7066.8   52.37
  7111.1   59.91  7155.4   59.09  7194.7   62.58  7243.9   71.24  7310.3   70.53
  7376.7   55.64  7487.4   55.13  7531.7   58.54    7576   69.49  7664.5   66.26
  7775.2   56.09  7953.5   59.76  8018.7   70.43  8199.2   86.34  8289.4  101.98
#Mann= 3 ,-1,0
  3658.5     .13       0  4979.7    .045       0  5020.3     .13       0
Bank Sta=4979.7,5020.3
XS Rating Curve= 0 ,0
Exp/Cntr=0.3,0.1

Type RM Length L Ch R = 1 ,12777   ,2345,2345,2345
BEGIN DESCRIPTION:
Back Swamp 9.0
END DESCRIPTION:
XS GIS Cut Line= 3
      2397475.04       896424.98       2399073.3        895769.9
        2398675.       891775.01
#Sta/Elev= 30
  3272.7   77.08  3322.4   65.38  3350.9   57.13  3384.3    51.7  3407.1   50.58
  3833.8    50.8  4036.4   52.52  4157.1   50.89  4218.2   52.02  4979.5   48.51
  4980.5   48.01  5020.6   48.51    5145   49.01  5264.4   51.21  5303.7   48.57
  5435.1   51.75  5498.8   50.98  5703.2   52.31  5748.9   50.47  6675.6   53.94
  6697.1   56.95  6718.7   56.84  6761.8   66.39  6804.9   65.09  6826.4   59.58
    6848   59.71  6869.5   54.67  6891.1   54.92  6912.6   52.72  9014.7   52.57
#Mann= 3 ,-1,0
  3272.7     .13       0  4979.5    .045       0  5020.6     .13       0
Bank Sta=4979.5,5020.6
XS Rating Curve= 0 ,0
Exp/Cntr=0.3,0.1

Type RM Length L Ch R = 1 ,10432   ,595,595,595
BEGIN DESCRIPTION:
Back Swamp 8.0
END DESCRIPTION:
XS GIS Cut Line= 3
      2397025.02         898075.      2399434.06         897685.
        2399825.         894075.
#Sta/Elev= 30
  2559.6  130.17  2711.9  127.35  2742.6  121.74  2800.1  105.61  2933.6   61.86
  2997.3   50.81  3860.7   49.57    4425   54.61  4614.4   46.62  4894.6   47.45
  4917.8   43.83  4979.4   43.64  4980.4   43.14  5020.7   43.64    5309   48.49
  5460.4   56.65  5550.2   57.94  5669.8   56.41  5784.5   51.06  6052.2   48.13
  6469.5   53.56    6619   49.92  8258.2   54.58    8323   66.86  8366.1   57.12
  8409.2   57.12  8452.4   51.39  8517.1   55.41  8538.7   59.77  8631.1   64.85
#Mann= 3 ,-1,0
  2559.6     .13       0  4979.4    .045       0  5020.7     .13       0
Bank Sta=4979.4,5020.7
XS Rating Curve= 0 ,0
Exp/Cntr=0.3,0.1

Type RM Length L Ch R = 1 ,9837    ,591,591,591
BEGIN DESCRIPTION:
Back Swamp 7.0
END DESCRIPTION:
XS GIS Cut Line= 3
      2396924.95         898125.      2399831.71       898013.27
        2400625.       894425.01
#Sta/Elev= 30
  2091.1   127.7  2201.7  129.18  2348.4  124.97  2418.4  107.96  2485.9   81.92
  2542.5   63.83  2627.2   50.56  3514.4   52.53  4334.4   48.78  4433.5    50.8
  4563.2   50.15  4735.6      44  4979.1   42.82  4980.1   42.32  5020.9   42.82
  5154.7   44.91  5236.2   54.47  5331.8   56.41  5382.1   56.16  5431.8   48.89
  8324.3   52.83  8368.2   60.04  8434.1   65.56  8456.1   61.01    8478   60.91
    8500   55.08  8565.9      51  8609.8   55.97  8653.7   56.21  8674.9   61.61
#Mann= 3 ,-1,0
  2091.1     .13       0  4979.1    .045       0  5020.9     .13       0
Bank Sta=4979.1,5020.9
XS Rating Curve= 0 ,0
Exp/Cntr=0.3,0.1

Type RM Length L Ch R = 1 ,9246    ,1786,1786,1786
BEGIN DESCRIPTION:
Back Swamp 6.0
END DESCRIPTION:
XS GIS Cut Line= 3
      2397075.05         898575.      2399974.97       898492.42
      2402375.01       894874.98
#Sta/Elev= 30
  2098.9  129.46  2224.7  111.07  2353.4   71.51  2407.1   61.14  2467.8   55.56
  2628.7   49.29  3554.8   47.86  4420.8   53.46    4657   52.17  4732.6      47
  4979.1   42.52  4980.1   42.02  5020.9   42.52  5357.8   44.08  5407.8   46.08
  5426.9   52.38  5449.7   53.32  5488.6   52.96  5502.8      49  7360.1   49.44
  7668.9   56.34  7771.9   48.65  8862.6   52.68  8904.2    54.2  8929.9   59.54
  9007.2   66.11  9058.6   55.23  9135.8    51.6  9295.8   63.69  9341.2   63.36
#Mann= 3 ,-1,0
  2098.9     .13       0  4979.1    .045       0  5020.9     .13       0
Bank Sta=4979.1,5020.9
XS Rating Curve= 0 ,0
Exp/Cntr=0.3,0.1

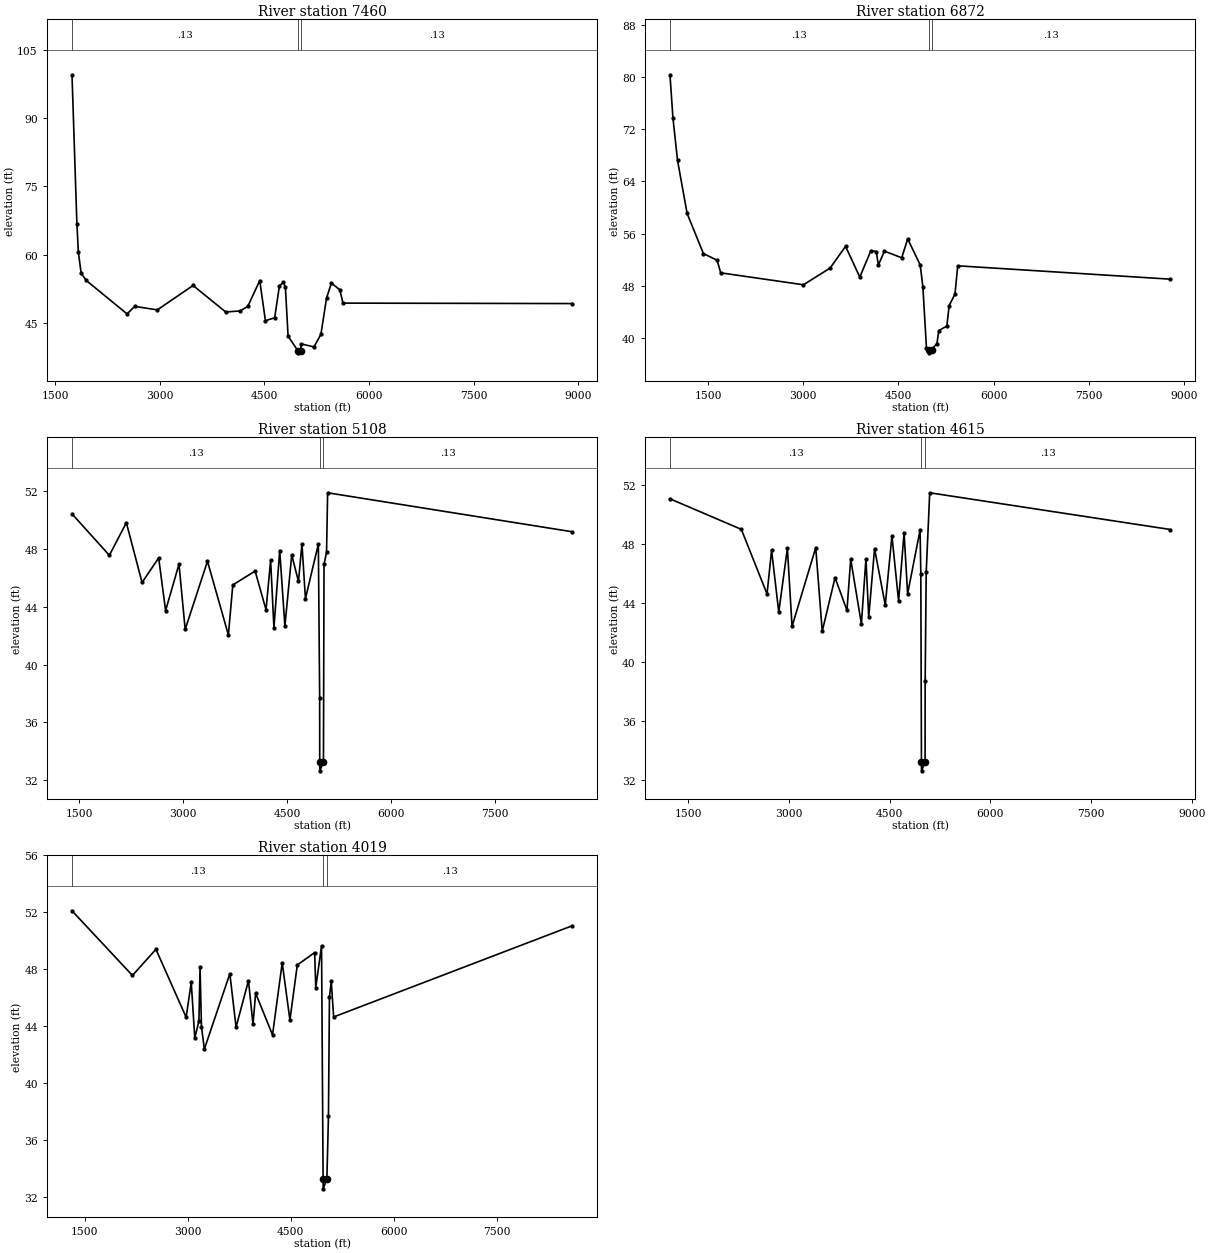
Type RM Length L Ch R = 1 ,7460    ,588,588,588
BEGIN DESCRIPTION:
Back Swamp 5.0
END DESCRIPTION:
XS GIS Cut Line= 3
      2397175.02         899425.      2400395.02       899906.49
      2401974.99       896325.01
#Sta/Elev= 30
  1744.2   99.52  1814.6   66.68    1836   60.53  1875.2   55.95    1948   54.36
  2533.3   47.01  2642.7   48.67  2966.7   47.89  3479.3   53.25  3947.4   47.43
  4152.9   47.66  4263.5   48.66  4435.1   54.33  4516.1   45.51  4648.8   46.17
  4716.4   53.11    4771   53.94  4802.2   52.95    4841   42.14  4979.1   38.96
  4980.1   38.46    5021   38.96  5028.4   40.42  5211.5   39.77  5311.6   42.52
    5392   50.48  5461.1   53.76  5582.4   52.31  5627.6   49.38  8914.5   49.28
#Mann= 3 ,-1,0
  1744.2     .13       0  4979.1    .045       0    5021     .13       0
Bank Sta=4979.1,5021
XS Rating Curve= 0 ,0
Exp/Cntr=0.3,0.1

Type RM Length L Ch R = 1 ,6872    ,1764,1764,1764
BEGIN DESCRIPTION:
Back Swamp 4.0
END DESCRIPTION:
XS GIS Cut Line= 3
      2396725.02         901075.        2400745.       900268.92
      2401925.01       896674.98
#Sta/Elev= 30
     900   80.35   946.4   73.74    1019   67.21  1169.9   59.08  1426.5   52.93
  1642.6    51.9  1699.1   49.97  3002.7   48.14  3422.7    50.7  3666.1   54.03
  3890.9   49.32  4066.4   53.39  4150.9   53.22  4182.8   51.15  4278.5    53.3
  4550.9   52.28  4645.1   55.17  4842.2   51.18    4884   47.87  4940.9   38.44
    4979    38.2    4980    37.7    5021    38.2  5106.1   39.12  5134.8   41.11
    5262    41.8  5298.3   44.95  5390.5   46.72  5433.4   51.05  8782.7      49
#Mann= 3 ,-1,0
     900     .13       0    4979    .045       0    5021     .13       0
Bank Sta=4979,5021
XS Rating Curve= 0 ,0
Exp/Cntr=0.3,0.1

Type RM Length L Ch R = 1 ,5108    ,493,493,493
BEGIN DESCRIPTION:
Back Swamp 3.0
END DESCRIPTION:
XS GIS Cut Line= 3
        2401175.       905074.99      2401191.04       901473.23
        2401575.       897874.96
#Sta/Elev= 30
  1398.2   50.43  1937.4   47.56  2182.5   49.82  2409.4   45.68    2649   47.38
    2749   43.73  2942.3   46.95  3031.6   42.43  3353.3   47.15  3655.1   42.05
  3718.9   45.51  4040.9   46.47  4198.5   43.79  4264.6   47.22  4312.4   42.55
  4395.8   47.89  4470.7   42.66  4569.3   47.59  4666.7   45.75  4716.7   48.35
  4767.1   44.56  4953.5   48.34  4972.4   37.67    4973   33.24  4974.1   32.64
  5027.1   33.24  5035.3   46.93  5071.8   47.77  5087.2   51.89  8618.7   49.19
#Mann= 3 ,-1,0
  1398.2     .13       0    4973    .045       0  5027.1     .13       0
Bank Sta=4973,5027.1
XS Rating Curve= 0 ,0
Exp/Cntr=0.3,0.1

Type RM Length L Ch R = 1 ,4615    ,596,596,596
BEGIN DESCRIPTION:
Back Swamp 2.0
END DESCRIPTION:
XS GIS Cut Line= 3
      2401244.53        905250.4      2401679.63       901500.86
      2401900.28       897825.68
#Sta/Elev= 30
  1225.3   51.08  2288.9   49.01  2671.8   44.63  2739.3   47.59  2846.4   43.41
  2975.1   47.72  3044.5   42.43  3397.5   47.77  3494.2    42.1  3685.4   45.74
  3862.8   43.52  3918.5   46.99  4077.8    42.6  4145.7      47  4187.4   43.05
    4274    47.7  4433.8   43.88  4533.1   48.58  4632.3   44.15  4713.9   48.78
    4767   44.64  4952.6   48.97  4963.5   45.99    4973   33.24  4974.1   32.64
  5027.1   33.24  5028.2   38.71    5044   46.11  5096.1   51.49  8681.8      49
#Mann= 3 ,-1,0
  1225.3     .13       0    4973    .045       0  5027.1     .13       0
Bank Sta=4973,5027.1
XS Rating Curve= 0 ,0
Exp/Cntr=0.3,0.1

Type RM Length L Ch R = 1 ,4019    ,0,0,0
BEGIN DESCRIPTION:
Back Swamp 1.0
END DESCRIPTION:
XS GIS Cut Line= 3
      2401374.99       905375.04      2402188.32       901779.28
        2402175.         898175.
#Sta/Elev= 30
  1313.4    52.1    2194   47.55  2536.6   49.39  2976.8   44.61  3051.2   47.06
  3102.7   43.15  3162.9   44.35  3179.4   48.12  3200.1   43.94  3242.1   42.37
  3613.6   47.67  3704.1   43.92  3885.3   47.18  3950.9   44.11  3989.4    46.3
  4235.5   43.37  4376.7   48.44  4488.9   44.42  4596.8   48.29  4849.5   49.16
  4865.6    46.7  4949.9   49.63  4972.6   33.24  4973.8   32.54  5027.4   33.24
  5050.7   37.68  5065.1   46.05  5091.5   47.13  5125.9   44.63  8604.3   51.05
#Mann= 3 ,-1,0
  1313.4     .13       0  4972.6    .045       0  5027.4     .13       0
Bank Sta=4972.6,5027.4
XS Rating Curve= 0 ,0
Exp/Cntr=0.3,0.1
LCMann Table=0

--- BackSwamp.g05 (geometry) ---

Geom Title=Proposed Conditions
Program Version=6.60

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
River Reach=Back Swamp      ,Reach-1

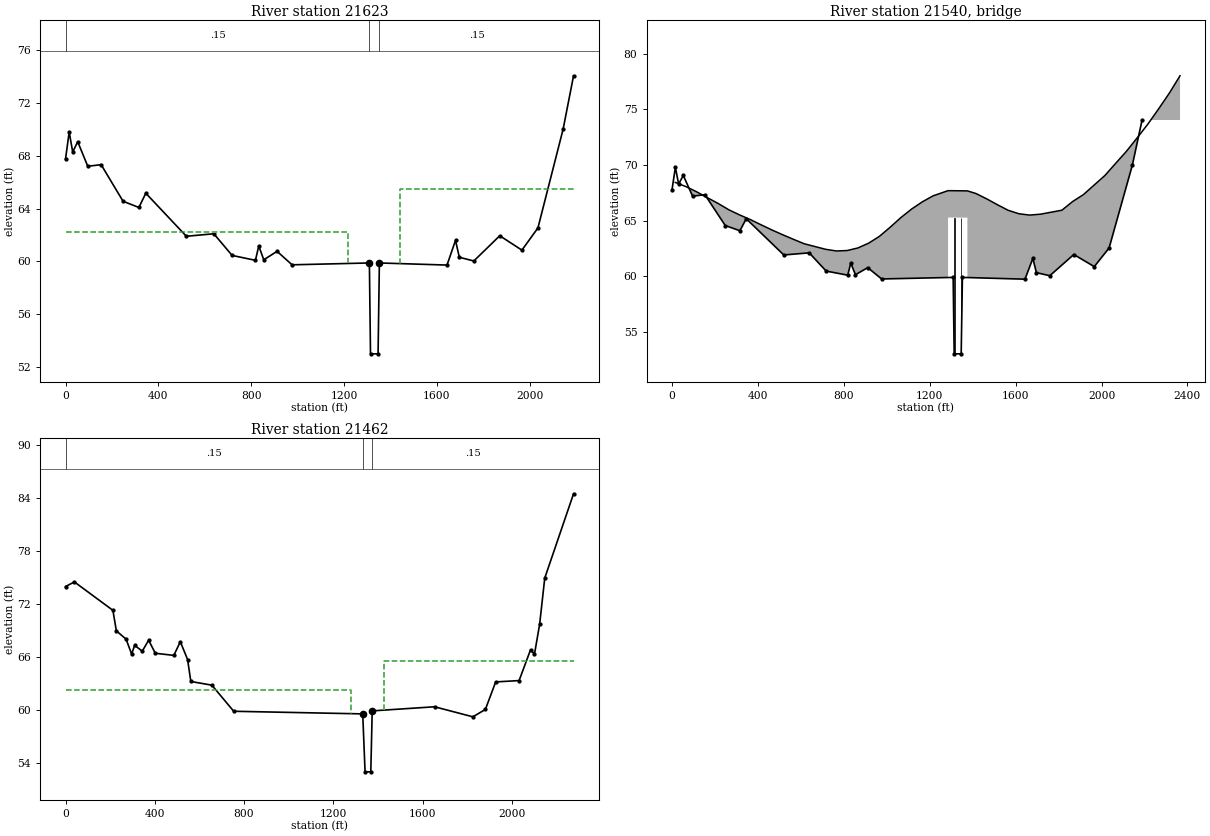
Type RM Length L Ch R = 1 ,21623   ,149.4,160.4,147.4
BEGIN DESCRIPTION:
Back Swamp 23.0
END DESCRIPTION:
XS GIS Cut Line= 6
2391240.37120011897201.4469594312391341.05151061897026.749313328
2391854.40541507895840.6757685532391902.05240594895687.819938989
2391913.31070653895505.8456908272391888.87865009 895154.57618795
#Sta/Elev= 30
       0   67.74   15.86   69.79      31   68.28   52.62   69.06   95.86    67.2
  153.52   67.32  248.06   64.55   316.2   64.08  345.89   65.16  520.63    61.9
  638.98   62.09  717.88   60.45  818.31   60.08  832.65   61.17  854.17   60.12
  911.55   60.76  976.11   59.74 1309.21   59.88 1314.03      53 1346.65      53
  1352.3   59.88 1643.71   59.72 1680.27   61.59 1696.71   60.31 1759.17   60.03
 1870.95   61.94  1966.3   60.85 2035.35   62.53 2143.92   70.01 2188.83   74.05
#Mann= 3 ,0,0
       0     .15       0 1309.21     .05       0  1352.3     .15       0
#XS Ineff= 2 , 0
         1218.33   62.26 1442.67           65.49
Permanent Ineff=
       F       F
Bank Sta=1309.21,1352.3
XS Rating Curve= 0 ,0
Exp/Cntr=0.5,0.3

Type RM Length L Ch R = 3 ,21540   ,,,
Node Name=Georgetown Rd Br
Bridge Culvert-0,0,0,0, 0
Deck Dist Width WeirC Skew NumUp NumDn MinLoCord MaxHiCord MaxSubmerge Is_Ogee
67.17072,36.25,2.6,0, 49, 49, , , 0.98, 0, 2,2,,
    15.5    65.5   115.5   165.5   215.5   265.5   315.5   365.5   415.5   465.5
   515.5   565.5   615.5   665.5   715.5   765.5   815.5   865.5   915.5   965.5
  1015.5  1065.5  1115.5  1165.5  1215.5  1285.5  1285.5  1375.5  1375.5  1415.5
  1465.5  1515.5  1565.5  1615.5  1665.5  1715.5  1765.5  1815.5  1865.5  1915.5
  1965.5  2015.5  2065.5  2115.5  2165.5  2215.5  2265.5  2315.5  2365.5
   68.43   68.05   67.58   67.05   66.53   65.96    65.5   65.08   64.61   64.15
   63.72   63.31   62.91   62.66   62.41   62.26    62.3   62.53   62.96   63.57
   64.39   65.26   66.03   66.68   67.22   67.69   67.69   67.67   67.67   67.43
   66.95   66.42   65.92   65.61   65.49   65.57   65.75   65.93   66.71   67.33
   68.19   69.05   70.14   71.22   72.43   73.67   75.04   76.46   78.03
                                                                                
                                                                                
                                                   65.27   65.26
                                                                                
                                                                        
    38.5    88.5   138.5   188.5   238.5   288.5   338.5   388.5   438.5   488.5
   538.5   588.5   638.5   688.5   738.5   788.5   838.5   888.5   938.5   988.5
  1038.5  1088.5  1138.5  1188.5  1238.5  1308.5  1308.5  1398.5  1398.5  1438.5
  1488.5  1538.5  1588.5  1638.5  1688.5  1738.5  1788.5  1838.5  1888.5  1938.5
  1988.5  2038.5  2088.5  2138.5  2188.5  2238.5  2288.5  2338.5  2388.5
   68.43   68.05   67.58   67.05   66.53   65.96    65.5   65.08   64.61   64.15
   63.72   63.31   62.91   62.66   62.41   62.26    62.3   62.53   62.96   63.57
   64.39   65.26   66.03   66.68   67.22   67.69   67.69   67.67   67.67   67.43
   66.95   66.42   65.92   65.61   65.49   65.57   65.75   65.93   66.71   67.33
   68.19   69.05   70.14   71.22   72.43   73.67   75.04   76.46   78.03
                                                                                
                                                                                
                                                   65.27   65.26
                                                                                
                                                                        
Pier Skew, UpSta & Num, DnSta & Num=  ,1315.5, 2 ,1338.5, 2 , 0 , 0 , 0 ,,
       2       2
       0      68
       2       2
       0      68
Pier Skew, UpSta & Num, DnSta & Num=  ,1345.5, 2 ,1368.5, 2 , 0 , 0 , 0 ,,
       2       2
       0      68
       2       2
       0      68
Abutment Skew #Up #Dn= , 3 , 3
  1285.5  1287.5  1317.5
      63      63      48
  1308.5  1310.5  1340.5
      63      63      48
Abutment Skew #Up #Dn= , 3 , 3
  1343.5  1373.5  1375.5
      48      63      63
  1366.5  1396.5  1398.5
      48      63      63
BR Coef=-1 , 1 , 1 ,0.9, 0 ,,,0.8,0,1.2,0,
WSPro=,,,, 1 ,,,, 0 ,,,, 0 ,,,,-1 ,-1 ,-1 , 0 , 0 , 0 , 0 , 0
BC Design=,, 0 ,, 0 ,,,,,,
BC HTab FreeFlow Pts= 100
BC HTab Sub Flow Curves= 60
BC HTab Sub Flow Pts= 50
BC HTab HWMax=70
BC HTab TWMax=70
BC Use User HTab Curves=0
BC User HTab FreeFlow(D)= 0

Type RM Length L Ch R = 1 ,21462   ,825.7,658.2,471.5
XS GIS Cut Line= 6
2391355.56908569897259.9680733282391464.40929705897075.329941747
2392012.51961844895908.8818954972392056.79132566895631.699397543
2392038.74965832895267.1051859812392027.01499591895139.761903067
#Sta/Elev= 30
       0   73.97   39.85   74.49  212.38   71.27  227.93   68.94  271.46      68
  296.14   66.32  310.04   67.29     344   66.64  372.57   67.88   402.4    66.4
  485.47   66.16  514.49   67.71  547.13   65.69  561.64    63.2  655.95   62.78
  753.88   59.82 1331.97  59.523 1342.47   52.95 1368.15   52.95 1374.45  59.863
 1653.94   60.33 1825.79   59.19 1881.64   60.03 1927.83   63.15 2032.76    63.3
 2083.96   66.79 2101.74   66.31 2124.74   69.68 2147.74   74.93 2276.76   84.49
#Mann= 3 ,0,0
       0     .15       0 1331.97     .05       0 1374.45     .15       0
#XS Ineff= 2 , 0
         1280.01   62.26 1426.99           65.49
Permanent Ineff=
       F       F
Bank Sta=1331.97,1374.45
XS Rating Curve= 0 ,0
Exp/Cntr(USF)=0,0
Exp/Cntr=0.5,0.3