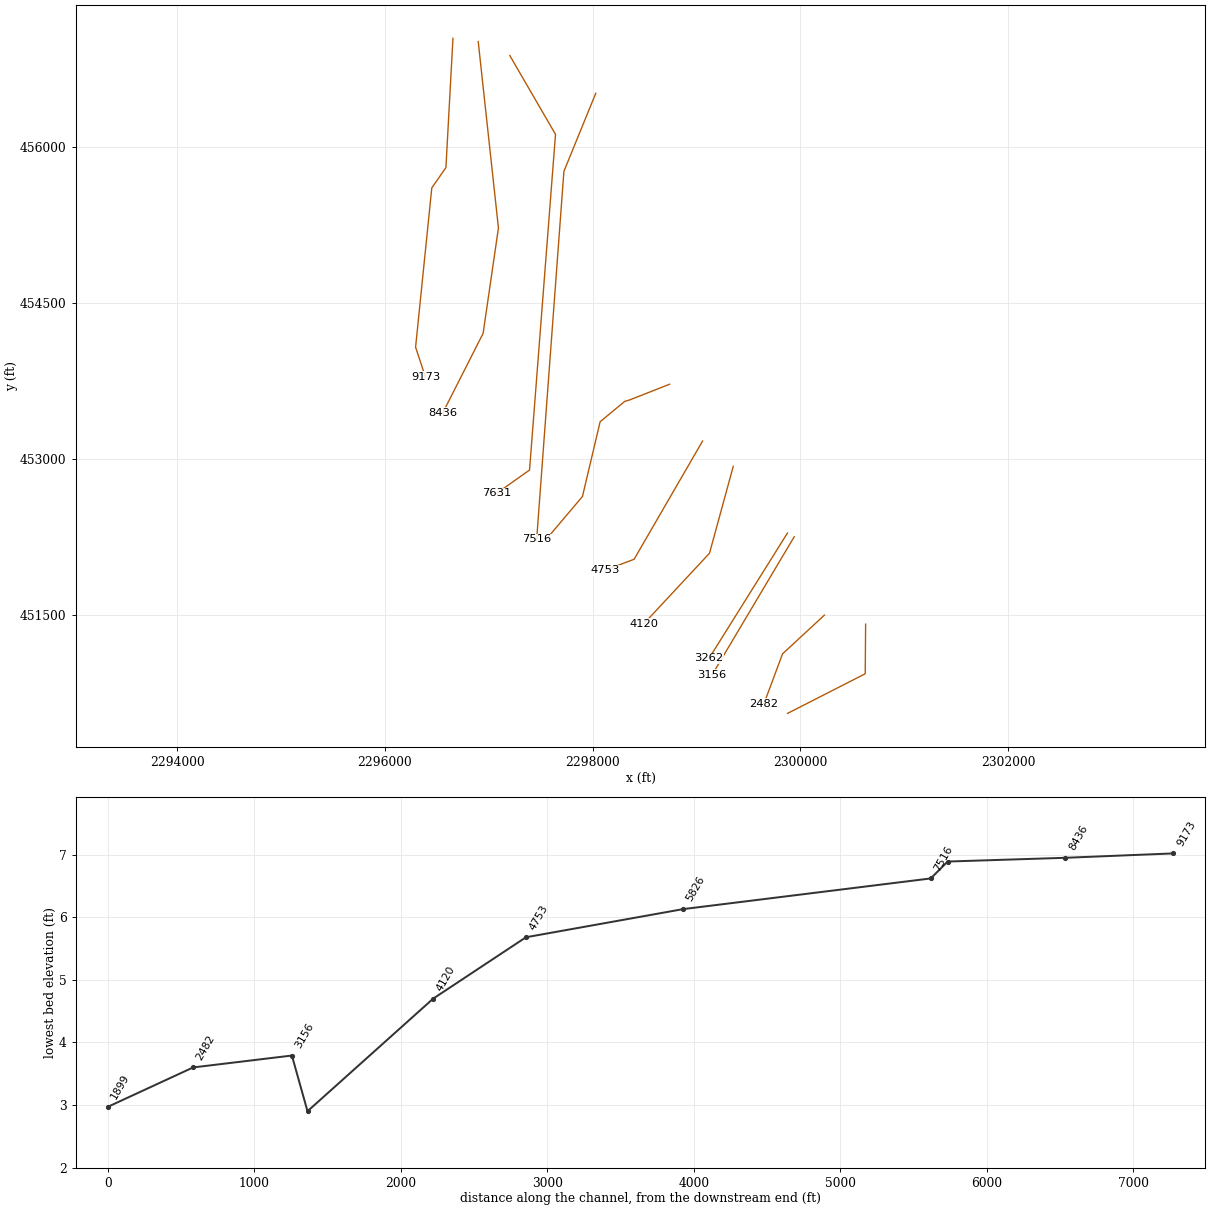
HEC-RAS study CanterhillSwamp.prj: S-8-791 over Canterhill Swamp

--- CanterhillSwamp.g01 (geometry) --- (continued)

Type RM Length L Ch R = 2 ,9336    ,,,
Node Name=Culvert Asset ID
Bridge Culvert-0,0,0,0, 0
Deck Dist Width WeirC Skew NumUp NumDn MinLoCord MaxHiCord MaxSubmerge Is_Ogee
163.0878,120,2.6,0, 60, 60, , , 0.98, 0, 2,2,,
       0 203.125 335.062 641.214 862.809 974.9551001.3431024.6531034.3271057.416
1254.6731397.1531519.1951538.9851631.7251766.5761786.3671793.319 1905.111957.885
1977.6751994.1672000.7642126.1042168.9842211.8632225.0572311.0182317.413 2406.47
2564.7942591.1812601.0772611.8392779.1912924.132  2970.52980.395 3033.173187.815
3224.4783297.0443317.2553442.1723461.965 3603.773702.5213795.1053825.2133844.581
3867.1083936.9373950.1314108.4554233.7954296.4654372.3294448.1924497.6694582.904
  29.701  28.531  27.938  26.034  24.966  24.296  24.052  23.993  23.864  23.836
  22.828  21.887  21.219  21.218  20.693  20.309  20.145  20.193  19.833  19.875
  19.743  19.805  19.677  19.612  19.498  19.598  19.523  19.588  19.496  19.566
  19.194  19.262   19.19  19.292  19.222  19.405  19.269  19.385  19.439  19.184
  19.297  19.234  19.365  19.438  19.356    19.5  19.403  19.504   19.42  19.502
  19.393  19.385  19.305   19.48  20.029  20.439  21.167  21.651  22.205   23.34
                                                                                
                                                                                
                                                                                
                                                                                
                                                                                
                                                                                
       0 203.125 335.062 641.214 862.809 974.9551001.3431024.6531034.3271057.416
1254.6731397.1531519.1951538.9851631.7251766.5761786.3671793.319 1905.111957.885
1977.6751994.1672000.7642126.1042168.9842211.8632225.0572311.0182317.413 2406.47
2564.7942591.1812601.0772611.8392779.1912924.132  2970.52980.395 3033.173187.815
3224.4783297.0443317.2553442.1723461.965 3603.773702.5213795.1053825.2133844.581
3867.1083936.9373950.1314108.4554233.7954296.4654372.3294448.1924497.6694582.904
  29.701  28.531  27.938  26.034  24.966  24.296  24.052  23.993  23.864  23.836
  22.828  21.887  21.219  21.218  20.693  20.309  20.145  20.193  19.833  19.875
  19.743  19.805  19.677  19.612  19.498  19.598  19.523  19.588  19.496  19.566
  19.194  19.262   19.19  19.292  19.222  19.405  19.269  19.385  19.439  19.184
  19.297  19.234  19.365  19.438  19.356    19.5  19.403  19.504   19.42  19.502
  19.393  19.385  19.305   19.48  20.029  20.439  21.167  21.651  22.205   23.34
                                                                                
                                                                                
                                                                                
                                                                                
                                                                                
                                                                                
BR Coef=-1 , 0 , 0 ,, 0 ,,,0.8,0,,1,
WSPro=,,,, 1 ,,,, 0 ,,,, 0 ,,,,-1 ,-1 ,-1 , 0 , 0 , 0 , 0 , 0
Multiple Barrel Culv=2,8,10,144,0.012,0.4,1,8,1,7.02,7.02, 2,Culvert #1  , 0 ,152
2904.0222518.5522915.6882530.218
BC Culvert Barrel=1,1,0
BC Culvert Barrel=2,2,0
Culvert Bottom n=0.012
BC Design=,, 0 ,, 0 ,,,,,,
BC Use User HTab Curves=0
BC User HTab FreeFlow(D)= 0

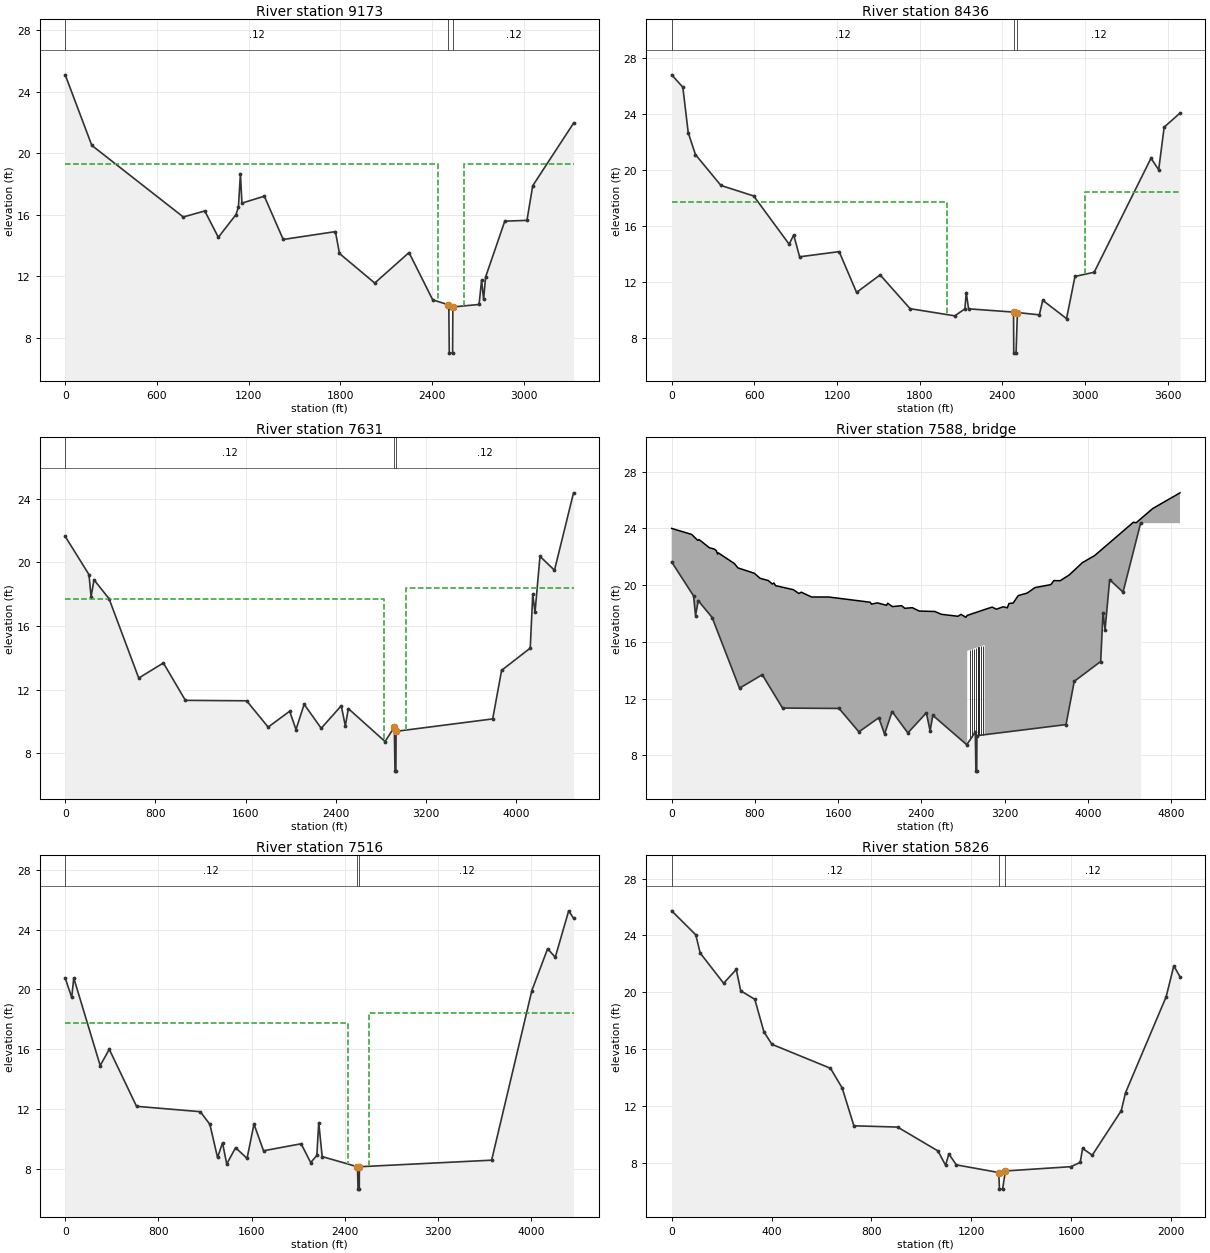
Type RM Length L Ch R = 1 ,9173    ,736.8,736.8,736.8
BEGIN DESCRIPTION:
FEMA XS G
END DESCRIPTION:
XS GIS Cut Line= 5
2296654.87488918457046.4016854812296587.13255457455802.154313453
2296451.03627635 455606.300874372296295.13973395454073.328001448
2296389.69578971453787.425688628
#Sta/Elev= 30
       0   25.09     174   20.51   772.8   15.86   913.4   16.25  1002.1   14.54
  1117.1   16.01  1133.5   16.49  1146.7   18.67  1156.5   16.76    1303   17.21
  1426.6    14.4  1768.4   14.91  1794.8   13.49  2025.7   11.57    2250   13.55
    2405   10.48    2504   10.17  2510.6    9.92 2513.55    7.02 2535.22    7.02
 2536.69    9.95 2539.64   10.02  2708.4   10.18  2724.9   11.76  2738.1   10.52
  2751.3   11.97  2876.7   15.59  3021.8   15.64  3059.6   17.893326.599   21.95
#Mann= 3 ,0,0
       0     .12       0    2504     .06       0 2539.64     .12       0
#XS Ineff= 2 , 0
         2438.55    19.3 2610.22            19.3
Permanent Ineff=
       F       F
Bank Sta=2504,2539.64
XS Rating Curve= 0 ,0
Pilot Channel=0,0,0
Exp/Cntr(USF)=0,0
Minor Loss Coefficient=0
Exp/Cntr=0.5,0.3

Type RM Length L Ch R = 1 ,8436    ,804.3,804.3,804.3
XS GIS Cut Line= 4
2296897.98575589457014.876603508 2297092.6755918455221.370236408
2296945.18329187454206.6232129172296555.80362007453439.663253302
#Sta/Elev= 30
       0    26.8      81   25.92   120.2   22.67   172.7   21.11   357.6   18.91
   595.2   18.16   852.7   14.72   885.7   15.38   928.6   13.82  1215.7   14.19
    1342   11.28  1513.1   12.53  1730.6   10.12  2055.2    9.61  2128.2   10.11
  2138.1   11.27    2155   10.11  2481.39.877311    2483    6.95  2499.5    6.95
  2509.69.845121  2668.7    9.68  2693.4   10.72  2866.1    9.41  2927.4   12.42
  3066.8   12.72    3479   20.85  3534.9   20.03  3574.7   23.07  3689.6   24.07
#Mann= 3 ,0,0
       0     .12       0  2481.3     .06       0  2509.6     .12       0
#XS Ineff= 2 , 0
            2000   17.73    3000           18.42
Permanent Ineff=
       F       F
Bank Sta=2481.3,2509.6
XS Rating Curve= 0 ,0
Exp/Cntr(USF)=0,0
Exp/Cntr=0.5,0.3

Type RM Length L Ch R = 1 ,7631    ,115.6,115.6,115.6
BEGIN DESCRIPTION:
FEMA XS F
END DESCRIPTION:
XS GIS Cut Line= 4
 2297201.9317566456880.9282523462297642.01754985456122.132376047
2297392.00228352452890.6296651932297074.01032327452666.181571252
#Sta/Elev= 30
       0  21.634  210.58  19.238 229.371   17.85 255.533  18.906 388.863  17.719
 652.028  12.735 870.606  13.6851065.653  11.3361608.688  11.3081799.573   9.656
1990.459  10.6522046.408     9.52118.812  11.0892270.204   9.5812447.925  10.997
2484.127   9.7252510.456   10.822836.277    8.75 2918.54    9.65 2924.33    6.89
 2932.29    6.89 2933.98    9.393790.702   10.17 3869.69  13.2194123.763  14.618
4145.873  18.0074165.954  16.8664210.134  20.3814338.658  19.5084507.565  24.371
#Mann= 3 ,0,0
       0     .12       0 2918.54     .06       0 2933.98     .12       0
#XS Ineff= 2 , 0
         2824.62   17.73 3024.45           18.42
Permanent Ineff=
       F       F
Bank Sta=2918.54,2933.98
XS Rating Curve= 0 ,0
Pilot Channel=0,0,0
Exp/Cntr(USF)=0,0
Minor Loss Coefficient=0
Exp/Cntr=0.5,0.3

Type RM Length L Ch R = 3 ,7588    ,,,
Node Name=Rail Bridge
Bridge Culvert-0,0,0,0, 0
Deck Dist Width WeirC Skew NumUp NumDn MinLoCord MaxHiCord MaxSubmerge Is_Ogee
14.58214,50,2.6,0, 60, 60, , , 0.98, 0, 2,2,,
       0 191.638 250.748 264.094  363.11 408.597 428.766  441.94  448.02 603.318
  636.51 793.727 850.326 929.369  966.58 982.064 998.5311169.8271222.4851245.952
1344.3421509.4011907.7631920.9491976.987 2065.992076.1432122.0282210.7572240.698
2313.2182379.1462530.0882593.6012751.6362781.3042827.4532840.6222840.6223008.449
3008.4493080.1523120.471 3186.273225.9183242.3943281.9373331.3653417.0413492.831
3644.4113674.0683733.3823822.3533947.572  4066.24438.5394464.9224622.6244886.115
      24  23.579  23.156  23.213  22.635  22.549  22.436  22.191  22.277   21.52
  21.218  20.841  20.481  20.323  20.079  20.153  19.965  19.681  19.412  19.504
  19.166  19.165  18.797  18.662  18.752   18.58  18.724  18.489  18.553  18.367
  18.413  18.174  18.144  17.944  17.807  17.943  17.733  17.867  17.867  18.282
  18.282  18.454  18.303  18.478  18.401  18.709  18.738  19.266  19.442   19.83
  20.038  20.325   20.31  20.726  21.586  22.089  24.438    24.4  25.395  26.509
                                                                                
                                                                                
                                                                                
                                                                  15.367  15.782
                                                                                
                                                                                
    -270-215.362-156.252-104.541  -43.89   1.597  21.766   34.94   41.02 153.504
  229.51 386.727 443.326 522.369  559.58 575.064 591.531 762.827 815.485 838.952
 937.3421102.4011500.7631513.9491569.987 1658.991669.1431715.0281803.7571833.698
1906.2181972.1462123.0882186.6012344.6362374.3042420.4532433.6222433.6222601.449
2601.4492673.1522713.471 2779.272818.9182835.3942874.9372924.3653010.0413085.831
3237.4113267.0683326.3823415.3533540.572  3659.24031.5394057.9224215.6244479.115
  23.745  23.579  23.156   23.05  22.635  22.549  22.436  22.191  22.277  21.744
  21.218  20.841  20.481  20.323  20.079  20.153  19.965  19.681  19.412  19.504
  19.166  19.165  18.797  18.662  18.752   18.58  18.724  18.489  18.553  18.367
  18.413  18.174  18.144  17.944  17.807  17.943  17.733  17.867  17.867  18.282
  18.282  18.454  18.303  18.478  18.401  18.709  18.738  19.266  19.442   19.83
  20.038  20.325   20.31  20.726  21.586  22.089  24.438    24.4  25.395  26.509
                                                                                
                                                                                
                                                                                
                                                                  15.367  15.782
                                                                                
                                                                                
Pier Skew, UpSta & Num, DnSta & Num=  ,2865.44, 2 ,2456, 2 , 0 , 0 , 0 ,,
       3       3
       0      16
       3       3
       0      16
Pier Skew, UpSta & Num, DnSta & Num=  ,2886.44, 2 ,2477, 2 , 0 , 0 , 0 ,,
       3       3
       0      16
       3       3
       0      16
Pier Skew, UpSta & Num, DnSta & Num=  ,2907.44, 2 ,2498, 2 , 0 , 0 , 0 ,,
       3       3
       0      16
       3       3
       0      16
Pier Skew, UpSta & Num, DnSta & Num=  ,2928.44, 2 ,2519, 2 , 0 , 0 , 0 ,,
       3       3
       0      16
       3       3
       0      16
Pier Skew, UpSta & Num, DnSta & Num=  ,2949.44, 2 ,2540, 2 , 0 , 0 , 0 ,,
       3       3
       0      16
       3       3
       0      16
Pier Skew, UpSta & Num, DnSta & Num=  ,2970.44, 2 ,2561, 2 , 0 , 0 , 0 ,,
       3       3
       0      16
       3       3
       0      16
Pier Skew, UpSta & Num, DnSta & Num=  ,2991.44, 2 ,2582, 2 , 0 , 0 , 0 ,,
       3       3
       0      16
       3       3
       0      16
Abutment Skew #Up #Dn= , 2 , 2
 2840.62 2860.62
   14.37    4.37
 2433.62 2453.62
   14.37    4.37
Abutment Skew #Up #Dn= , 2 , 2
 2988.45 3008.45
    4.78   14.78
 2581.45 2601.45
    4.78   14.78
BR Coef=-1 ,-1 ,-1 ,0.9, 0 ,,,0.8,0,1.2,0,
WSPro=,,,, 1 ,,,, 0 ,,,, 0 ,,,,-1 ,-1 ,-1 , 0 , 0 , 0 , 0 , 0
BC Design=,, 0 ,, 0 ,,,,,,
BC Use User HTab Curves=0
BC User HTab FreeFlow(D)= 0

Type RM Length L Ch R = 1 ,7516    ,1689.4,1689.4,1689.4
BEGIN DESCRIPTION:
FEMA XS E (Relocated)
END DESCRIPTION:
XS GIS Cut Line= 3
2298029.47657414456517.4316239892297722.82902754455766.024950072
2297460.59124242452224.186436314
#Sta/Elev= 30
       0   20.76   55.77   19.47   73.49   20.77  300.31    14.9  378.28   15.99
  612.18   12.17 1159.49   11.81 1241.75   10.96 1307.55    8.74 1350.33    9.72
 1386.52     8.3  1462.2     9.4 1560.91    8.68 1620.13   10.98 1702.39    9.19
 2024.84    9.66 2107.09     8.4 2159.74    8.88 2176.19   11.07  2205.8     8.8
 2508.51    8.12 2513.69    6.62 2524.05    6.62 2524.96    8.12 3660.12    8.56
  4005.6   19.93  4140.5   22.73  4206.3   22.16 4321.47   25.27  4363.1   24.78
#Mann= 3 ,0,0
       0     .12       0 2508.51     .06       0 2524.96     .12       0
#XS Ineff= 2 , 0
         2425.62   17.73 2609.45           18.42
Permanent Ineff=
       F       F
Bank Sta=2508.51,2524.96
XS Rating Curve= 0 ,0
Pilot Channel=0,0,0
Exp/Cntr(USF)=0,0
Minor Loss Coefficient=0
Exp/Cntr=0.5,0.3

Type RM Length L Ch R = 1 ,5826    ,1073.3,1073.3,1073.3
XS GIS Cut Line= 6
2298739.70143586453716.7488376262298356.96342013453566.211777453
2298307.76830242453551.4532421422298071.65023935453356.140505962
 2297901.3355709452636.1739529812297560.70623401452233.612009378
#Sta/Elev= 30
       0   25.73    96.6   24.04   114.2   22.76   208.1   20.63   258.8    21.6
   276.4    20.1   332.9    19.5   369.5   17.21   401.4   16.33   636.2   14.64
   683.1   13.25   729.9   10.59     905    10.5  1066.6    8.82  1097.2    7.81
  1110.3    8.61  1140.2    7.84  1310.27.298237    1313    6.13  1325.7    6.13
  1336.6    7.41  1598.7    7.71  1636.5    8.01    1646       9  1684.7    8.52
  1800.8   11.65    1818   12.92  1980.8   19.68  2011.4   21.85  2036.2   21.09
#Mann= 3 ,0,0
       0     .12       0  1310.2     .06       0  1336.6     .12       0
Bank Sta=1310.2,1336.6
XS Rating Curve= 0 ,0
Exp/Cntr(USF)=0,0
Exp/Cntr=0.3,0.1

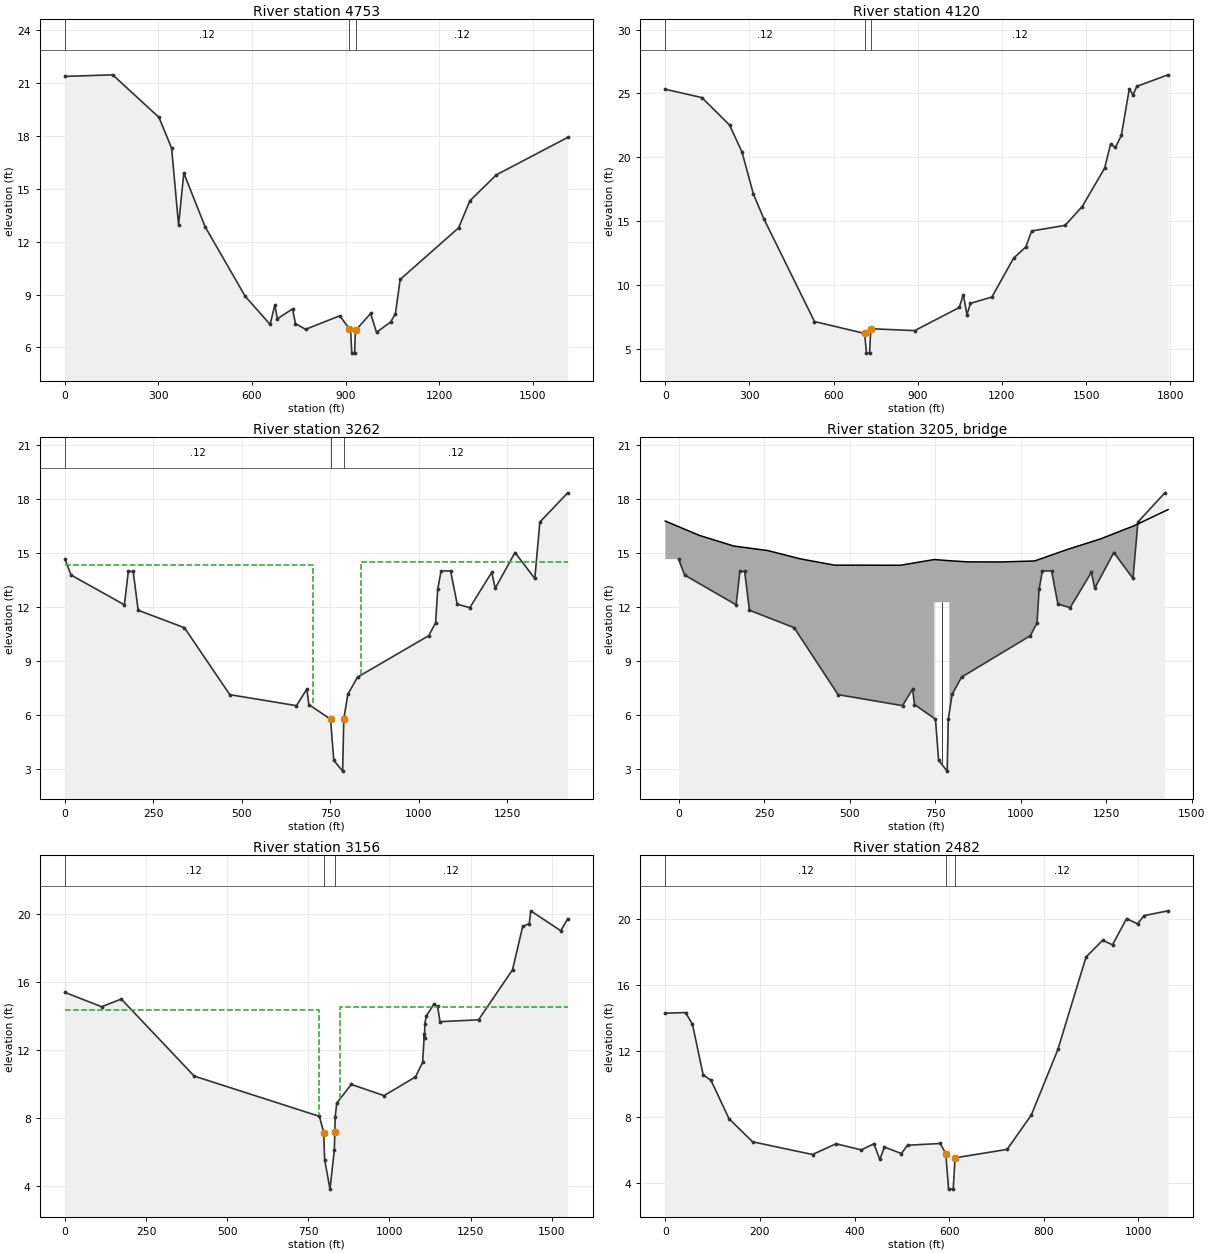
Type RM Length L Ch R = 1 ,4753    ,632.8,632.8,632.8
BEGIN DESCRIPTION:
FEMA XS D
END DESCRIPTION:
XS GIS Cut Line= 3
2299057.51933441453169.6784263482298398.50033637452031.832550533
2298120.22668773451927.269564396
#Sta/Elev= 30
       0   21.38   153.1   21.47   301.4   19.06   342.1   17.31   364.4   12.95
   381.2    15.9   449.3   12.86   578.2     8.9   657.9    7.31     673    8.41
   681.3    7.63   729.9    8.19     739    7.36   771.6    7.03   881.6     7.8
   911.9    7.06   915.7    7.09  919.88    5.68     929    5.68   931.4       7
   934.7    7.02   980.2    7.93   999.1    6.86  1044.6    7.45  1059.8    7.92
    1075    9.86  1262.4   12.79  1298.4   14.32    1383   15.79  1612.2   17.92
#Mann= 3 ,0,0
       0     .12       0   911.9     .06       0   934.7     .12       0
Bank Sta=911.9,934.7
XS Rating Curve= 0 ,0
Pilot Channel=0,0,0
Exp/Cntr(USF)=0,0
Minor Loss Coefficient=0
Exp/Cntr=0.3,0.1

Type RM Length L Ch R = 1 ,4120    ,858.2,858.2,858.2
XS GIS Cut Line= 3
2299352.88104062452926.4830469252299124.50455339452090.392856366
2298493.56612255451413.004970496
#Sta/Elev= 30
       0   25.33   130.5   24.68   229.2   22.53   273.4   20.43   314.3   17.12
   351.7   15.19   531.9    7.17   710.86.237648  717.19     4.7  728.39     4.7
   732.56.610002   889.2    6.46  1048.1    8.27  1062.3    9.28  1075.6    7.71
  1087.8    8.59  1164.5    9.09  1241.5   12.12  1285.2      13  1306.1   14.25
  1425.3   14.69  1486.2   16.16  1566.1   19.16  1587.3   21.02  1604.7   20.79
  1625.8   21.72    1654   25.34  1667.5   24.89  1680.9   25.56  1792.4   26.46
#Mann= 3 ,0,0
       0     .12       0   710.8     .06       0   732.5     .12       0
Bank Sta=710.8,732.5
XS Rating Curve= 0 ,0
Exp/Cntr(USF)=0,0
Exp/Cntr=0.5,0.3

Type RM Length L Ch R = 1 ,3262    ,106.5,106.5,106.5
XS GIS Cut Line= 2
2299874.69414978452284.4255250752299120.54639226451079.427551152
#Sta/Elev= 30
       0   14.65    17.5   13.77   168.2   12.12   179.1   13.97     193   13.97
   207.1   11.82   337.9   10.85   466.1    7.14   654.6    6.53     684    7.45
   689.6    6.59  750.95    5.78  760.15     3.5   785.2     2.9   788.4    5.78
   799.7    7.15   827.2    8.11  1028.6   10.41  1047.9   11.12  1054.1      13
  1063.6      14  1090.4      14    1109   12.16  1144.7   11.96  1206.6   13.92
  1216.6   13.04  1272.4   15.02  1328.5   13.58  1342.8   16.71  1421.5   18.33
#Mann= 3 ,0,0
       0     .12       0  750.95     .06       0   788.4     .12       0
#XS Ineff= 2 , 0
          701.47   14.31  837.87            14.5
Permanent Ineff=
       F       F
Bank Sta=750.95,788.4
XS Rating Curve= 0 ,0
Exp/Cntr(USF)=0,0
Exp/Cntr=0.5,0.3

Type RM Length L Ch R = 3 ,3205    ,,,
Node Name=S-791 over Cante
Bridge Culvert-0,0,0,0, 0
Deck Dist Width WeirC Skew NumUp NumDn MinLoCord MaxHiCord MaxSubmerge Is_Ogee
45.41141,41.6,2.6,0, 19, 19, , , 0.98, 0, 2,2,,
     -39      61     161     261     356     456     551   648.5 747.675 747.675
 791.675 791.675   843.5     942    1041    1136  1232.5    1331    1431
  16.765  15.967  15.381  15.127  14.668  14.319  14.318  14.315  14.632  14.632
  14.567  14.567  14.503  14.497  14.552  15.188  15.768  16.499  17.401
                                                                          12.263
  12.263
       0     100     200     300     395     495     590   687.5 792.485 792.485
 836.485 836.485   882.5     981    1080    1175  1271.5    1370    1470
  16.765  15.967  15.381  15.127  14.668  14.319  14.318  14.315  14.632  14.632
  14.567  14.567  14.503  14.497  14.552  15.188  15.768  16.499  17.401
                                                                          12.263
  12.263
Pier Skew, UpSta & Num, DnSta & Num=  ,769.68, 2 ,814.49, 2 , 0 , 0 , 0 ,,
   1.667   1.667
       0      13
   1.667   1.667
       0      13
BR Coef=-1 ,-1 ,-1 ,0.9, 0 ,,,0.8,0,1.2,0,
WSPro=,,,, 1 ,,,, 0 ,,,, 0 ,,,,-1 ,-1 ,-1 , 0 , 0 , 0 , 0 , 0
BC Design=,, 0 ,, 0 ,,,,,,
BC HTab HWMax=55
BC Use User HTab Curves=0
BC User HTab FreeFlow(D)= 0

Type RM Length L Ch R = 1 ,3156    ,674.1,674.1,674.1
XS GIS Cut Line= 2
2299940.02838755452249.1647155182299148.04964891450917.645446147
#Sta/Elev= 30
       0   15.36   113.2   14.52   173.7   14.97   398.3   10.44   784.2    8.07
   797.4    7.12   800.3    5.52  816.77    3.79   830.2    6.11  831.57    7.16
   832.6    8.01   837.5    8.85   882.3    9.95   983.4    9.29  1080.1   10.39
  1102.2   11.25  1107.4   12.93  1108.2   12.67  1108.9   13.53  1113.8   13.98
  1136.6   14.67  1148.3   14.54  1155.7   13.64  1274.4   13.75  1379.1   16.69
  1410.5   19.24  1430.8   19.41  1435.4   20.16  1527.7   18.99  1549.2   19.69
#Mann= 3 ,0,0
       0     .12       0   797.4     .06       0  831.57     .12       0
#XS Ineff= 2 , 0
          782.33   14.31  846.63            14.5
Permanent Ineff=
       F       F
Bank Sta=797.4,831.57
XS Rating Curve= 0 ,0
Exp/Cntr(USF)=0,0
Exp/Cntr=0.5,0.3

Type RM Length L Ch R = 1 ,2482    ,582.7,582.7,582.7
XS GIS Cut Line= 3
2300230.09231702451494.2075663622299827.38999727451121.435824429
2299647.80653035450639.825617697
#Sta/Elev= 30
       0   14.27    42.9   14.31    57.4    13.6    80.1   10.53    96.6    10.2
   134.7    7.87   184.6    6.47   311.2     5.7     361    6.35   414.4    5.98
   440.9    6.35   453.5     5.4   463.2    6.15     499    5.76     512    6.26
   581.2    6.37     5935.749032  598.79     3.6  608.61     3.6   612.55.497998
   722.6    6.01   773.8     8.1   829.9   12.07   889.4   17.68   924.4   18.69
   945.4   18.42   975.1   20.01   998.4   19.69    1012   20.19  1062.8   20.48
#Mann= 3 ,0,0
       0     .12       0     593     .06       0   612.5     .12       0
Bank Sta=593,612.5
XS Rating Curve= 0 ,0
Exp/Cntr(USF)=0,0
Exp/Cntr=0.3,0.1

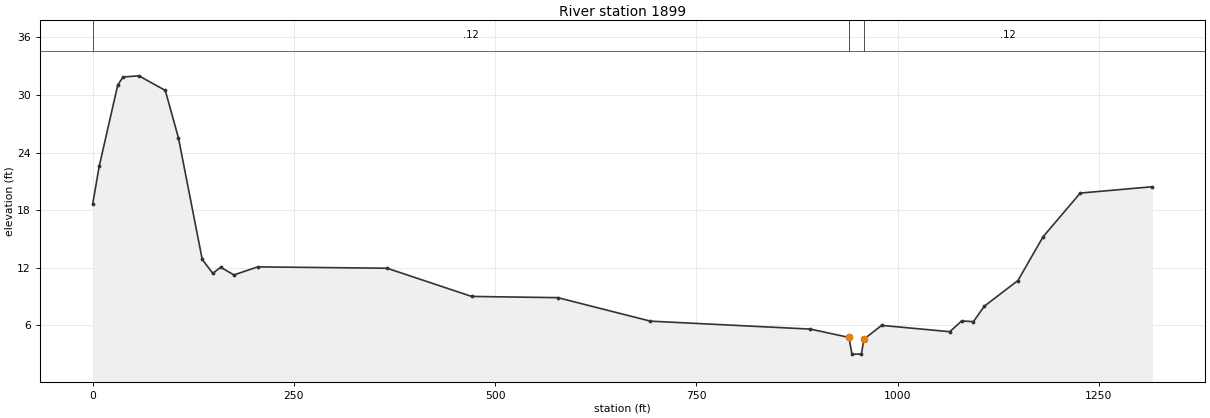
Type RM Length L Ch R = 1 ,1899    ,,,
BEGIN DESCRIPTION:
FEMA XS A
END DESCRIPTION:
XS GIS Cut Line= 3
2300627.08689487451407.4814674272300623.23695599450929.816759281
2299875.78805268450548.609998898
#Sta/Elev= 30
       0   18.67       8   22.57      31   31.03    37.6   31.88    57.3      32
    90.1   30.48   106.5   25.51     136   12.85   149.1    11.4     159   12.03
   175.4   11.23   204.9   12.07   365.7   11.93   470.7    8.99   577.9    8.86
   692.9    6.41   891.8    5.58   939.6    4.71  943.36    2.97  955.13    2.97
   958.1    4.52   980.2    5.97  1064.9    5.31  1079.6    6.43  1094.3    6.36
  1107.8    7.97  1149.6   10.65  1180.9   15.22    1227   19.77  1316.7   20.43
#Mann= 3 ,0,0
       0     .12       0   939.6     .06       0   958.1     .12       0
Bank Sta=939.6,958.1
XS Rating Curve= 0 ,0
Exp/Cntr(USF)=0,0
Exp/Cntr=0.3,0.1
LCMann Table=0

--- CanterhillSwamp.g02 (geometry) ---

Geom Title=Natural Conditions
Program Version=6.60

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
River Reach=Canterhill Swamp,Reach 1

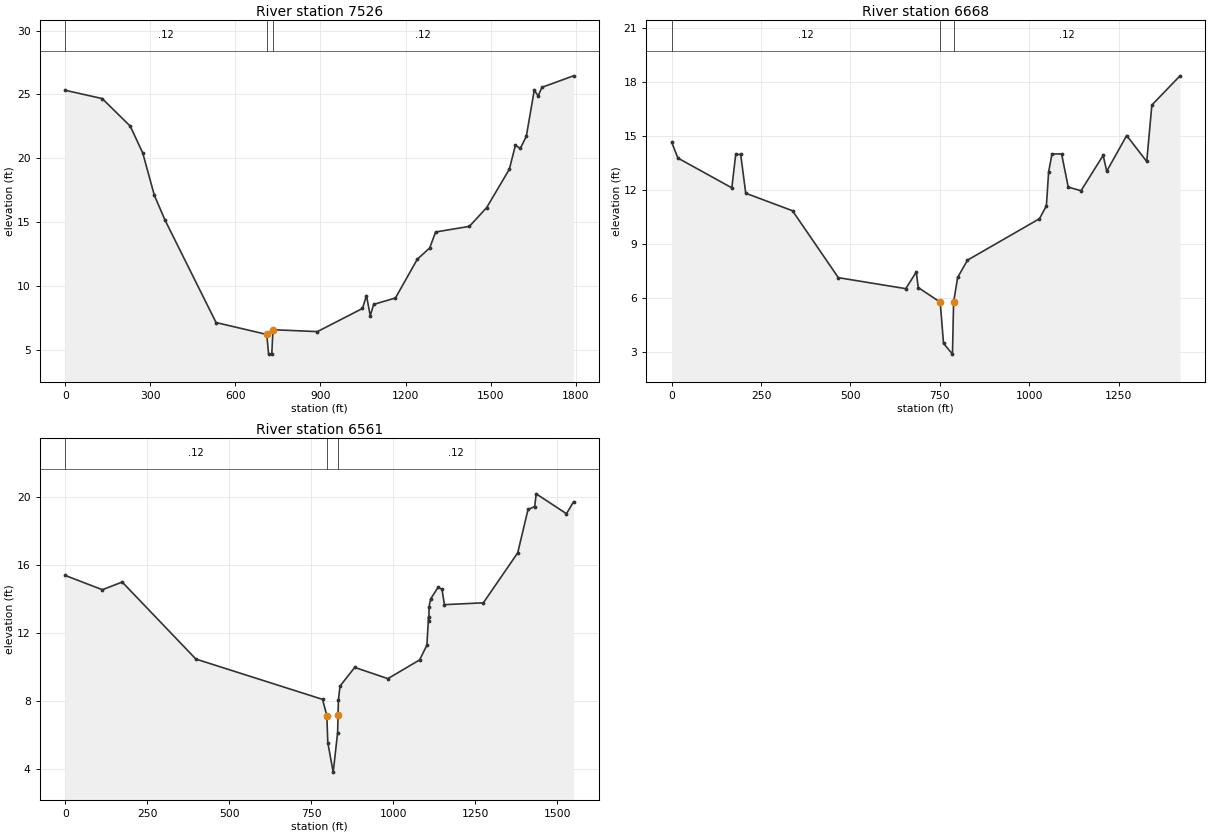
Type RM Length L Ch R = 1 ,7526    ,858.2,858.2,858.2
XS GIS Cut Line= 3
2299352.88104062452926.4830469252299124.50455339452090.392856366
2298493.56612255451413.004970496
#Sta/Elev= 30
       0   25.33   130.5   24.68   229.2   22.53   273.4   20.43   314.3   17.12
   351.7   15.19   531.9    7.17   710.86.237648  717.19     4.7  728.39     4.7
   732.56.610002   889.2    6.46  1048.1    8.27  1062.3    9.28  1075.6    7.71
  1087.8    8.59  1164.5    9.09  1241.5   12.12  1285.2      13  1306.1   14.25
  1425.3   14.69  1486.2   16.16  1566.1   19.16  1587.3   21.02  1604.7   20.79
  1625.8   21.72    1654   25.34  1667.5   24.89  1680.9   25.56  1792.4   26.46
#Mann= 3 ,0,0
       0     .12       0   710.8     .06       0   732.5     .12       0
Bank Sta=710.8,732.5
XS Rating Curve= 0 ,0
Exp/Cntr(USF)=0,0
Exp/Cntr=0.3,0.1

Type RM Length L Ch R = 1 ,6668    ,106.5,106.5,106.5
XS GIS Cut Line= 2
2299874.69414978452284.4255250752299120.54639226451079.427551152
#Sta/Elev= 30
       0   14.65    17.5   13.77   168.2   12.12   179.1   13.97     193   13.97
   207.1   11.82   337.9   10.85   466.1    7.14   654.6    6.53     684    7.45
   689.6    6.59  750.95    5.78  760.15     3.5   785.2     2.9   788.4    5.78
   799.7    7.15   827.2    8.11  1028.6   10.41  1047.9   11.12  1054.1      13
  1063.6      14  1090.4      14    1109   12.16  1144.7   11.96  1206.6   13.92
  1216.6   13.04  1272.4   15.02  1328.5   13.58  1342.8   16.71  1421.5   18.33
#Mann= 3 ,0,0
       0     .12       0  750.95     .06       0   788.4     .12       0
#XS Ineff= 2 , 0
Permanent Ineff=
       F       F
Bank Sta=750.95,788.4
XS Rating Curve= 0 ,0
Exp/Cntr(USF)=0,0
Exp/Cntr=0.3,0.1

Type RM Length L Ch R = 1 ,6561    ,674.1,674.1,674.1
XS GIS Cut Line= 2
2299940.02838755452249.1647155182299148.04964891450917.645446147
#Sta/Elev= 30
       0   15.36   113.2   14.52   173.7   14.97   398.3   10.44   784.2    8.07
   797.4    7.12   800.3    5.52  816.77    3.79   830.2    6.11  831.57    7.16
   832.6    8.01   837.5    8.85   882.3    9.95   983.4    9.29  1080.1   10.39
  1102.2   11.25  1107.4   12.93  1108.2   12.67  1108.9   13.53  1113.8   13.98
  1136.6   14.67  1148.3   14.54  1155.7   13.64  1274.4   13.75  1379.1   16.69
  1410.5   19.24  1430.8   19.41  1435.4   20.16  1527.7   18.99  1549.2   19.69
#Mann= 3 ,0,0
       0     .12       0   797.4     .06       0  831.57     .12       0
#XS Ineff= 2 , 0
Permanent Ineff=
       F       F
Bank Sta=797.4,831.57
XS Rating Curve= 0 ,0
Exp/Cntr(USF)=0,0
Exp/Cntr=0.3,0.1

--- CanterhillSwamp.g03 (geometry) ---

Geom Title=Post-Project
Program Version=6.60

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
River Reach=Canterhill Swamp,Reach 1
Reach XY= 30
2294975.43235676457587.0606746592295363.82500829457014.168117543
2295391.04394171456656.5053222132295607.11639787456568.771204108
2295342.77122931456162.1600840292295413.38899377455992.080679478
 2295104.0632931455672.8088147942295410.39484255454613.185182949
 2295554.0536902454711.7280288552295905.48072717454597.599528501
 2296005.2137076454758.0312937992296529.92626319454465.342023869
2297160.17147952454482.5268673822297338.91077012454121.554957831
2297620.83379465454050.0192748252297824.13666145452874.523975744
2298277.78548884452561.3285064832298458.88308153452685.554894123
2298642.69703345452318.089444298 2299148.2526098452235.825884526
2299504.02409782451971.7306998082299464.76434307451628.207845726
 2299696.5734818451343.4622647432299628.42976462451195.249679883
  2299947.249435451026.0339203052300301.17688297450528.942015534
2300523.62852616450463.7628543332300492.22934892450148.169243965
2300884.37778152449936.6959039272301381.88864233 449881.15266506

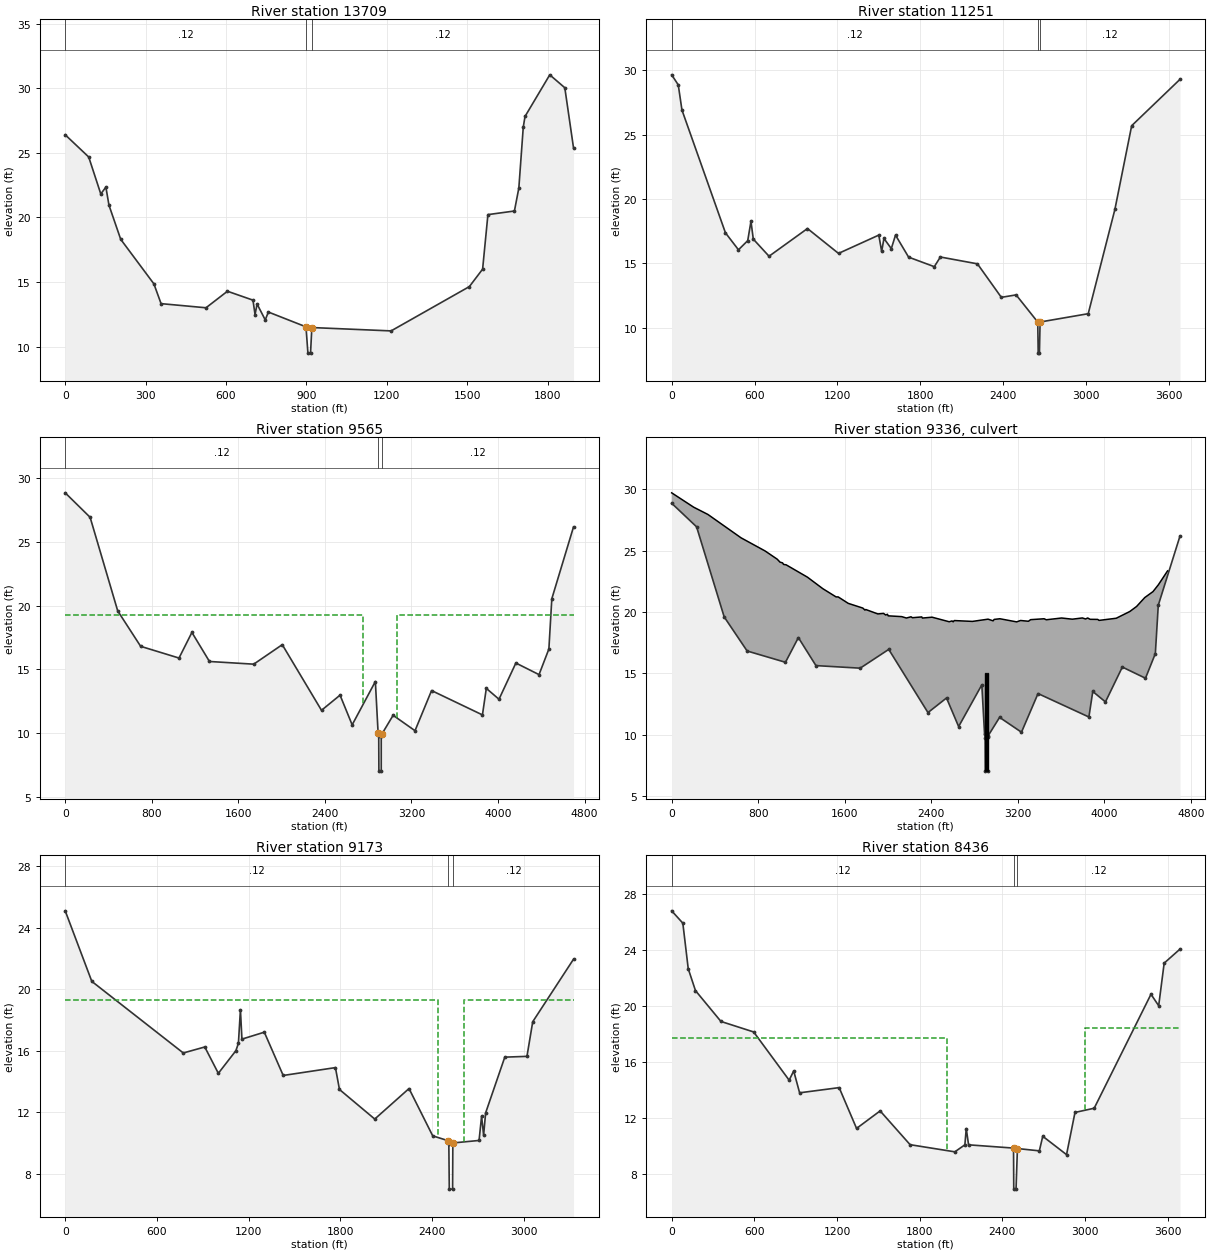
Type RM Length L Ch R = 1 ,13709   ,2458.1,2458.1,2458.1
BEGIN DESCRIPTION:
FEMA XS I
END DESCRIPTION:
XS GIS Cut Line= 6
2296070.14926226457612.932366237 2295962.5391733457549.340237404
2295390.55524108457211.2039894032295006.62139371456984.248906438
2294585.58933968456942.9699540732294348.34614693456919.672247669
#Sta/Elev= 30
       0   26.39    87.7   24.67   132.8   21.81   151.8   22.34   163.3   20.94
   207.1    18.3     331   14.85   357.7   13.32   525.4      13   605.4   14.28
   700.7   13.59   708.4   12.47     716   13.29   746.5   12.06   758.1   12.67
   898.5  11.525  905.69    9.49  915.48    9.49   920.4   11.47  1216.1   11.21
  1508.2   14.64  1557.6   15.99  1577.4   20.21  1676.3   20.49  1692.8   22.27
  1709.3   26.98  1715.9   27.81  1808.2   31.03  1864.3   30.031896.884   25.37
#Mann= 3 ,0,0
       0     .12       0   898.5     .06       0   920.4     .12       0
Bank Sta=898.5,920.4
XS Rating Curve= 0 ,0
Exp/Cntr(USF)=0,0
Exp/Cntr=0.3,0.1

Type RM Length L Ch R = 1 ,11251   ,1686.1,1686.1,1686.1
XS GIS Cut Line= 4
2296266.64587651457546.0673903532295931.60163964455972.816191142
  2295501.870988455492.1005469392294190.82832199454923.982058335
#Sta/Elev= 30
       0   29.64    47.7   28.86    74.4   26.91   389.4   17.38   483.8   16.06
   550.9   16.77   574.4   18.27   591.2   16.89   705.3   15.56   983.7   17.71
  1208.5   15.78  1500.4    17.2  1521.1   15.93  1537.7   16.94    1591   16.15
  1621.4    17.2  1716.3   15.49  1902.4   14.75  1946.4    15.5  2214.9   14.97
    2388   12.37  2495.1   12.56  2651.810.45053    2655    8.04    2664    8.04
  2668.710.45505  3017.4    11.1  3210.5   19.19  3332.1   25.69  3682.2   29.29
#Mann= 3 ,0,0
       0     .12       0  2651.8     .06       0  2668.7     .12       0
Bank Sta=2651.8,2668.7
XS Rating Curve= 0 ,0
Exp/Cntr(USF)=0,0
Exp/Cntr=0.5,0.3

Type RM Length L Ch R = 1 ,9565    ,392.8,392.8,392.8
BEGIN DESCRIPTION:
FEMA XS H
END DESCRIPTION:
XS GIS Cut Line= 6
2296370.13627964457615.8258457722296176.97528344456219.890883618
2296027.47433722454644.3133576872295688.06463631453820.018792113
2295065.71887251453564.5243306852294934.57509759453510.704667395
#Sta/Elev= 30
       0   28.85   230.2   26.93   485.2   19.59   697.2   16.81  1051.7   15.89
  1170.9    17.9  1333.2   15.62  1742.3   15.41    2006   16.94  2368.6   11.79
    2540   12.98    2652   10.65  2866.3   14.05  2891.7   10.02  2897.5    9.76
 2899.02    7.02 2920.69    7.02 2920.73    9.81  2924.8     9.9  3030.5    11.4
  3232.8   10.19  3385.8   13.34  3855.9   11.43  3891.8   13.51  4008.9   12.66
  4164.9    15.5  4378.9   14.59    4470    16.6  4497.1   20.54  4697.8   26.18
#Mann= 3 ,0,0
       0     .12       0  2891.7     .06       0  2924.8     .12       0
#XS Ineff= 2 , 0
         2749.02    19.3 3070.69            19.3
Permanent Ineff=
       F       F
Bank Sta=2891.7,2924.8
XS Rating Curve= 0 ,0
Exp/Cntr(USF)=0,0
Exp/Cntr=0.5,0.3

Type RM Length L Ch R = 2 ,9336    ,,,
Node Name=Culvert Asset ID
Bridge Culvert-0,0,0,0, 0
Deck Dist Width WeirC Skew NumUp NumDn MinLoCord MaxHiCord MaxSubmerge Is_Ogee
163.0878,120,2.6,0, 60, 60, , , 0.98, 0, 2,2,,
       0 203.125 335.062 641.214 862.809 974.9551001.3431024.6531034.3271057.416
1254.6731397.1531519.1951538.9851631.7251766.5761786.3671793.319 1905.111957.885
1977.6751994.1672000.7642126.1042168.9842211.8632225.0572311.0182317.413 2406.47
2564.7942591.1812601.0772611.8392779.1912924.132  2970.52980.395 3033.173187.815
3224.4783297.0443317.2553442.1723461.965 3603.773702.5213795.1053825.2133844.581
3867.1083936.9373950.1314108.4554233.7954296.4654372.3294448.1924497.6694582.904
  29.701  28.531  27.938  26.034  24.966  24.296  24.052  23.993  23.864  23.836
  22.828  21.887  21.219  21.218  20.693  20.309  20.145  20.193  19.833  19.875
  19.743  19.805  19.677  19.612  19.498  19.598  19.523  19.588  19.496  19.566
  19.194  19.262   19.19  19.292  19.222  19.405  19.269  19.385  19.439  19.184
  19.297  19.234  19.365  19.438  19.356    19.5  19.403  19.504   19.42  19.502
  19.393  19.385  19.305   19.48  20.029  20.439  21.167  21.651  22.205   23.34
                                                                                
                                                                                
                                                                                
                                                                                
                                                                                
                                                                                
       0 203.125 335.062 641.214 862.809 974.9551001.3431024.6531034.3271057.416
1254.6731397.1531519.1951538.9851631.7251766.5761786.3671793.319 1905.111957.885
1977.6751994.1672000.7642126.1042168.9842211.8632225.0572311.0182317.413 2406.47
2564.7942591.1812601.0772611.8392779.1912924.132  2970.52980.395 3033.173187.815
3224.4783297.0443317.2553442.1723461.965 3603.773702.5213795.1053825.2133844.581
3867.1083936.9373950.1314108.4554233.7954296.4654372.3294448.1924497.6694582.904
  29.701  28.531  27.938  26.034  24.966  24.296  24.052  23.993  23.864  23.836
  22.828  21.887  21.219  21.218  20.693  20.309  20.145  20.193  19.833  19.875
  19.743  19.805  19.677  19.612  19.498  19.598  19.523  19.588  19.496  19.566
  19.194  19.262   19.19  19.292  19.222  19.405  19.269  19.385  19.439  19.184
  19.297  19.234  19.365  19.438  19.356    19.5  19.403  19.504   19.42  19.502
  19.393  19.385  19.305   19.48  20.029  20.439  21.167  21.651  22.205   23.34
                                                                                
                                                                                
                                                                                
                                                                                
                                                                                
                                                                                
BR Coef=-1 , 0 , 0 ,, 0 ,,,0.8,0,,1,
WSPro=,,,, 1 ,,,, 0 ,,,, 0 ,,,,-1 ,-1 ,-1 , 0 , 0 , 0 , 0 , 0
Multiple Barrel Culv=2,8,10,144,0.012,0.4,1,8,1,7.02,7.02, 2,Culvert #1  , 0 ,152
2904.0222518.5522915.6882530.218
BC Culvert Barrel=1,1,0
BC Culvert Barrel=2,2,0
Culvert Bottom n=0.012
BC Design=,, 0 ,, 0 ,,,,,,
BC Use User HTab Curves=0
BC User HTab FreeFlow(D)= 0

Type RM Length L Ch R = 1 ,9173    ,736.8,736.8,736.8
BEGIN DESCRIPTION:
FEMA XS G
END DESCRIPTION:
XS GIS Cut Line= 5
2296654.87488918457046.4016854812296587.13255457455802.154313453
2296451.03627635 455606.300874372296295.13973395454073.328001448
2296389.69578971453787.425688628
#Sta/Elev= 30
       0   25.09     174   20.51   772.8   15.86   913.4   16.25  1002.1   14.54
  1117.1   16.01  1133.5   16.49  1146.7   18.67  1156.5   16.76    1303   17.21
  1426.6    14.4  1768.4   14.91  1794.8   13.49  2025.7   11.57    2250   13.55
    2405   10.48    2504   10.17  2510.6    9.92 2513.55    7.02 2535.22    7.02
 2536.69    9.95 2539.64   10.02  2708.4   10.18  2724.9   11.76  2738.1   10.52
  2751.3   11.97  2876.7   15.59  3021.8   15.64  3059.6   17.893326.599   21.95
#Mann= 3 ,0,0
       0     .12       0    2504     .06       0 2539.64     .12       0
#XS Ineff= 2 , 0
         2438.55    19.3 2610.22            19.3
Permanent Ineff=
       F       F
Bank Sta=2504,2539.64
XS Rating Curve= 0 ,0
Pilot Channel=0,0,0
Exp/Cntr(USF)=0,0
Minor Loss Coefficient=0
Exp/Cntr=0.5,0.3

Type RM Length L Ch R = 1 ,8436    ,804.3,804.3,804.3
XS GIS Cut Line= 4
2296897.98575589457014.876603508 2297092.6755918455221.370236408
2296945.18329187454206.6232129172296555.80362007453439.663253302
#Sta/Elev= 30
       0    26.8      81   25.92   120.2   22.67   172.7   21.11   357.6   18.91
   595.2   18.16   852.7   14.72   885.7   15.38   928.6   13.82  1215.7   14.19
    1342   11.28  1513.1   12.53  1730.6   10.12  2055.2    9.61  2128.2   10.11
  2138.1   11.27    2155   10.11  2481.39.877311    2483    6.95  2499.5    6.95
  2509.69.845121  2668.7    9.68  2693.4   10.72  2866.1    9.41  2927.4   12.42
  3066.8   12.72    3479   20.85  3534.9   20.03  3574.7   23.07  3689.6   24.07
#Mann= 3 ,0,0
       0     .12       0  2481.3     .06       0  2509.6     .12       0
#XS Ineff= 2 , 0
            2000   17.73    3000           18.42
Permanent Ineff=
       F       F
Bank Sta=2481.3,2509.6
XS Rating Curve= 0 ,0
Exp/Cntr(USF)=0,0
Exp/Cntr=0.5,0.3

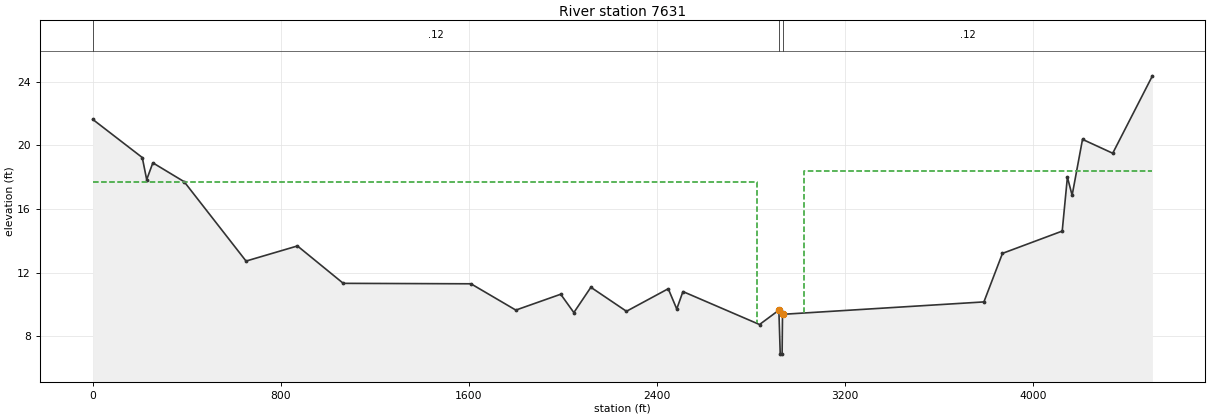
Type RM Length L Ch R = 1 ,7631    ,115.6,115.6,115.6
BEGIN DESCRIPTION:
FEMA XS F
END DESCRIPTION:
XS GIS Cut Line= 4
 2297201.9317566456880.9282523462297642.01754985456122.132376047
2297392.00228352452890.6296651932297074.01032327452666.181571252
#Sta/Elev= 30
       0  21.634  210.58  19.238 229.371   17.85 255.533  18.906 388.863  17.719
 652.028  12.735 870.606  13.6851065.653  11.3361608.688  11.3081799.573   9.656
1990.459  10.6522046.408     9.52118.812  11.0892270.204   9.5812447.925  10.997
2484.127   9.7252510.456   10.822836.277    8.75 2918.54    9.65 2924.33    6.89
 2932.29    6.89 2933.98    9.393790.702   10.17 3869.69  13.2194123.763  14.618
4145.873  18.0074165.954  16.8664210.134  20.3814338.658  19.5084507.565  24.371
#Mann= 3 ,0,0
       0     .12       0 2918.54     .06       0 2933.98     .12       0
#XS Ineff= 2 , 0
         2824.62   17.73 3024.45           18.42
Permanent Ineff=
       F       F
Bank Sta=2918.54,2933.98
XS Rating Curve= 0 ,0
Pilot Channel=0,0,0
Exp/Cntr(USF)=0,0
Minor Loss Coefficient=0
Exp/Cntr=0.5,0.3