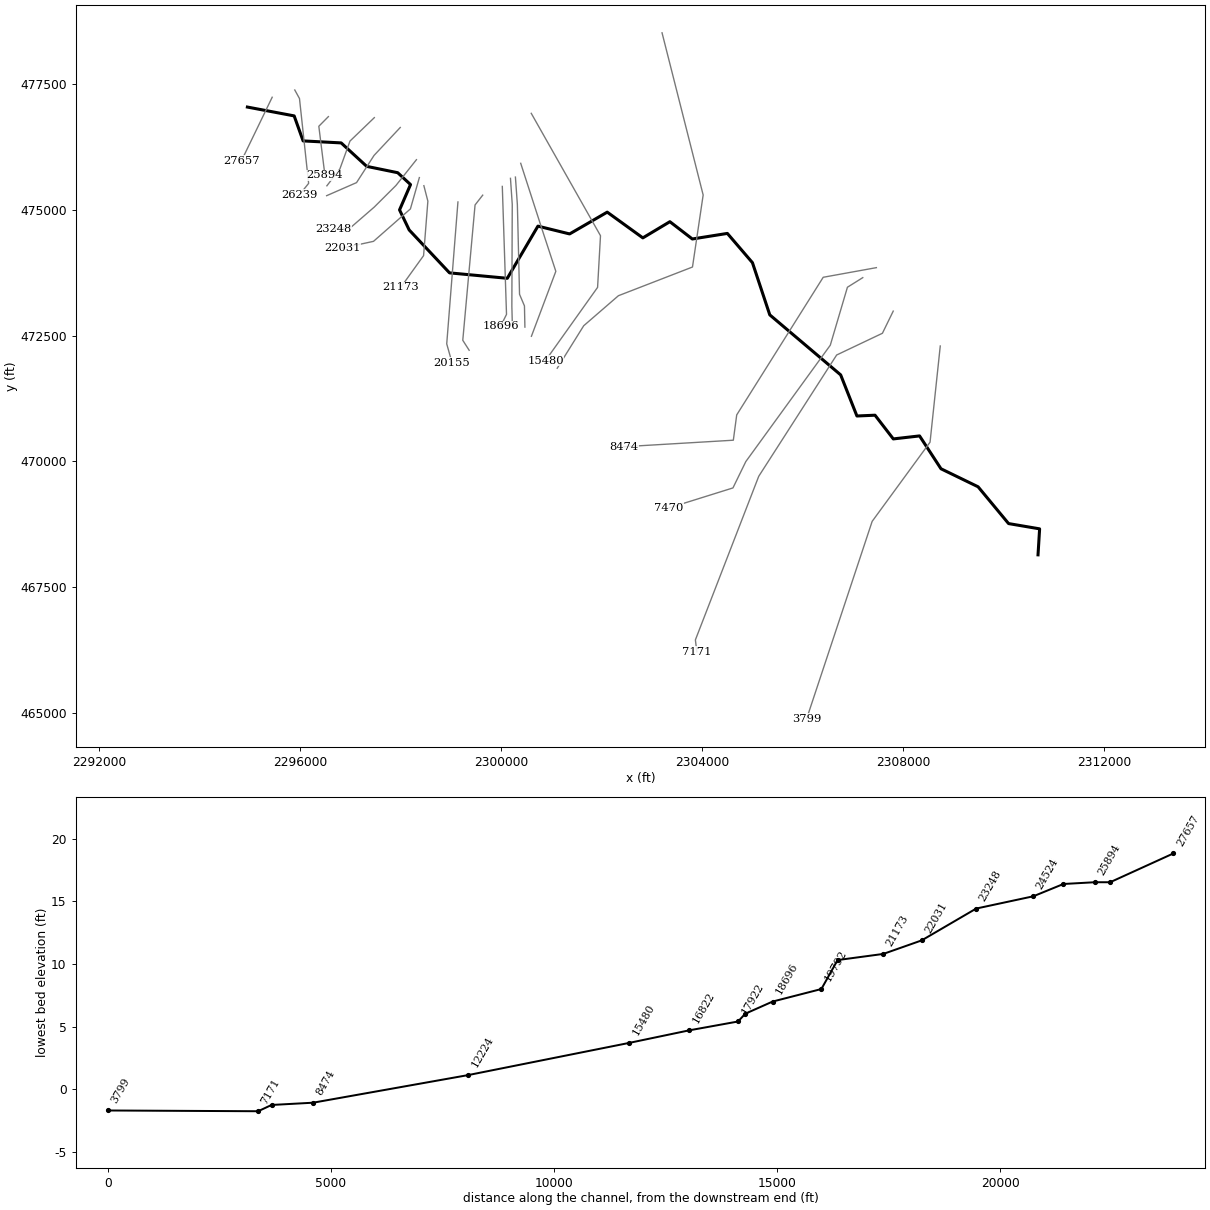
--- MollyBranch.prj (project) ---

Proj Title=S-8-791 over Molly Branch Creek
Current Plan=p07
Default Exp/Contr=0.3,0.1
English Units
Geom File=g02
Geom File=g03
Geom File=g01
Geom File=g05
Flow File=f01
Flow File=f02
Flow File=f03
Flow File=f04
Plan File=p02
Plan File=p03
Plan File=p01
Plan File=p04
Plan File=p07
Plan File=p08
Y Axis Title=Elevation
X Axis Title(PF)=Main Channel Distance
X Axis Title(XS)=Station
BEGIN DESCRIPTION:
END DESCRIPTION:
DSS Export Rating Curves= 0
DSS Export Rating Curve Sorted= 0
DSS Export Volume Flow Curves= 0
DXF OffsetX= 0
DXF OffsetY= 0
DXF ScaleX= 1
DXF ScaleY= 10

--- MollyBranch.p07 (plan) ---

Plan Title=Proposed
Program Version=6.60
Short Identifier=Proposed
Geom File=g05
Flow File=f02
Subcritical Flow
K Sum by GR= 0
Std Step Tol= 0.01
Critical Tol= 0.01
Num of Std Step Trials= 20
Max Error Tol= 0.3
Flow Tol Ratio= 0.001
Split Flow NTrial= 30
Split Flow Tol= 0.02
Split Flow Ratio= 0.02
Log Output Level= 0
Friction Slope Method= 1
Unsteady Friction Slope Method= 2
Unsteady Bridges Friction Slope Method= 1
Parabolic Critical Depth
Global Vel Dist= 0 , 0 , 0
Global Log Level= 0
CheckData=True
Encroach Param= 0 ,0,0, 2
Flow Ratio Tolerance=0.1
Flow Ratio Min Ratio=0.5
Flow Ratio Max Ratio=4
Flow Ratio Max Iterations= 10
Computation Interval=1MIN
Output Interval=1HOUR
Instantaneous Interval=1HOUR
Mapping Interval=1HOUR
Computation Time Step Use Courant=        0
Computation Time Step Use Time Series=    0
Computation Time Step Count To Double=0
Computation Time Step Max Doubling=0
Computation Time Step Max Halving=0
Computation Time Step Residence Courant=0
Run HTab= 0
Run UNet= 0
Run Sediment= 0
Run PostProcess= 0
Run WQNet= 0
Run RASMapper= 0
UNET Theta= 1
UNET Theta Warmup= 1
UNET ZTol= 0.02
UNET ZSATol= 0.02
UNET MxIter= 20
UNET Max Iter WO Improvement= 0
UNET MaxInSteps= 0
UNET DtIC= 0
UNET DtMin= 0
UNET MaxCRTS= 20
UNET WFStab= 2
UNET SFStab= 1
UNET WFX= 1
UNET SFX= 1
UNET Gravity=32.17405
UNET 1D Methodology=Finite Difference
UNET DSS MLevel= 4
UNET Pardiso=0
UNET DZMax Abort= 100
UNET Use Existing IB Tables=-1
UNET Froude Reduction=False
UNET Froude Limit= 0.8
UNET Froude Power= 4
UNET D1 Cores= 0
UNET WindReference=Eulerian
UNET WindDragFormulation=Hsu (1988)
UNET D2 Coriolis=0
UNET D2 Cores= 0
UNET D2 Theta= 1
UNET D2 Theta Warmup= 1
UNET D2 Z Tol= 0.01
UNET D2 Volume Tol= 0.01
UNET D2 Max Iterations= 20
UNET D2 Advanced Convergence=0
UNET D2 WS Max Tol=0.15
UNET D2 WS RMS Tol=0.002
UNET D2 WS Stall Tol=1
UNET D2 Equation= 0
UNET D2 RampUpFraction=0.1
UNET D2 TimeSlices= 1
UNET D2 Turbulence Formulation=None
UNET D2 Eddy Viscosity=0.3
UNET D2 Transverse Eddy Viscosity=0.1
UNET D2 Smagorinsky Mixing=0.05
UNET D2 BCVolumeCheck=0
UNET D2 Cores=0
UNET D2 SolverType=PARDISO (Direct)
UNET D2 Minimum Iterations= 3
UNET D2 Maximum Iterations= 30
UNET D2 Restart Number= 10
UNET D2 Relaxation Coeff=1.3
UNET D2 SOR Precondition Iterations= 10
UNET D2 ILUT Maximum Fill= 8
UNET D2 ILUT Tolerance=1E-08
UNET D2 Convergence Tolerance=0.00001
PS Theta= 1
PS WS Tol= 0.01
PS Volume Tol= 0.01
PS Max Iterations= 20
PS Equation= 0
PS Advance Time Step=-1
PS Target Courant=0.9
PS Time Slices= 1
PS Iterate With 2D=0
PS Project Initial WSE from DS=-1
PS Ramp Up Initial WSE from US=-1
PS Cores=0
UNET D1D2 MaxIter= 0
UNET D1D2 ZTol=0.01
UNET D1D2 QTol=0.1
UNET D1D2 MinQTol=1
Write IC File= 0
Write IC File at Fixed DateTime=0
Write IC File at Sim End=0
Echo Input=False
Echo Parameters=False
Echo Output=False
Write Detailed= 0
HDF Write Warmup=0
HDF Write Time Slices=0
HDF Flush=0
HDF Compression= 1
HDF Chunk Size= 1
HDF Spatial Parts= 1
HDF Use Max Rows=0
HDF Fixed Rows= 1
Calibration Method= 0
Calibration Iterations= 20
Calibration Max Change=0.05
Calibration Tolerance=0.2
Calibration Maximum=1.5
Calibration Minimum=0.5
Calibration Optimization Method= 1
WQ AD Non Conservative
WQ ULTIMATE=-1
WQ Max Comp Step=1HOUR
WQ Output Interval=15MIN
WQ Output Selected Increments= 0
WQ Create Restart=0
WQ Fixed Restart=0
WQ System Summary=0
WQ Write To DSS=0
Sorting and Armoring Iterations= 10
XS Update Threshold= 0.02
Bed Roughness Predictor= 0
Processes Affected by Predictor=Sediment Only
Hydraulics Update Threshold= 0.02
Energy Slope Method= 1
Volume Change Method= 1
Sediment Retention Method= 0
Sediment TS Multiplier= 1
Warm Up Method= 0
XS Weighting Method= 0
Number of US Weighted Cross Sections= 1
Number of DS Weighted Cross Sections= 1
Upstream XS Weight=0
Main XS Weight=1
Downstream XS Weight=0
Number of DS XS's Weighted with US Boundary= 1
Upstream Boundary Weight= 1
Weight of XSs Associated with US Boundary= 0
Number of US XS's Weighted with DS Boundary= 1
Downstream Boundary Weight= 0.5
Weight of XSs Associated with DS Boundary= 0.5
Percentile Method= 0
Sediment Output Level= 3
Mass or Volume Output= 0
Output Increment Type= 1
Profile and TS Output Increment= 1
Transport Output Increment 1
XS Output Flag= 0
XS Output Increment= 10
Read HDF5 Sediment Hotstart= 0
Sediment Hotstart Type= 0
Write Gradation File= 0
Read Gradation Hotstart= 0
Write HDF5 File= 1
Write Binary Output= 1
Write DSS Sediment File= 0
DSS Sediment Output Type= 1
SV Curve= 0
Specific Gage Flag= 0
Subcell Erosion Methods= 0
Subcell Deposition Methods= 0
Advection Scheme= 1
Matrix Solver= 0
Implicit Weighting Factor= 1
Maximum Outer Loop Convergence Iterations= 5
Convergence Maximum Absolute= 0.001
Convergence RMSE= 0.0001
Grain Fractions Max Abs Error= 0.001
Max Subgrid Regions= 1
Max Subgrid Length Scale= 3.402823E+38
Initial Layer Thickness= 3
Min Layer Thickness= 0.1
Max Layer Thickness= 6
Number of Layers= 5

--- MollyBranch.p01 (plan) ---

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Plan Title=Natural
Short Identifier=Natural
Geom File=g01
Flow File=f02

--- MollyBranch.p02 (plan) ---

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Plan Title=Corrected Effective - Floodway
Short Identifier=CE_FW
Geom File=g03
Flow File=f04
Encroach River=Molly Branch
Encroach Reach=Molly Branch
Encroach Node=27657
       1   180.3   363.5
Encroach Node=26239
       1   900.3  1298.9
Encroach Node=25894
       1   453.5   884.4
Encroach Node=25196
       1   747.4  1052.4
Encroach Node=24524
       1   950.2  1268.2
Encroach Node=23248
       1   489.1   789.1
Encroach Node=22031
       1   796.6  1023.6
Encroach Node=21173
       1  1010.9  1535.1
Encroach Node=20155
       1  1184.7  1544.8
Encroach Node=19792
       1  1414.6  1711.2
Encroach Node=18696
       1  1567.8  1904.3
Encroach Node=18083
       1  1453.8  1743.1
Encroach Node=17922
       1  1452.8  1690.4
Encroach Node=16822
       1  1130.3  1459.5
Encroach Node=15480
       1  2337.7  2591.6
Encroach Node=12224
       1  3715.7  4226.6
Encroach Node=8474
       1  2035.2  2446.3
Encroach Node=7470
       1  1776.2  2159.2
Encroach Node=7171
       1  1558.7  1888.5
Encroach Node=3799
       1  2000.1  2286.1
Encroach Node=1228
       1  2966.8    3311
Encroach Node=442
       1    3034  3603.1

--- MollyBranch.p03 (plan) ---

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Plan Title=Duplicate Effective - HEC-2
Short Identifier=DE - HEC-2
Geom File=g02
Flow File=f03
K Sum by GR=-1
Persistent XS Scale= 0 , 2500 , 45 , 10 , 500 , 5
Encroach Param=-1 ,0,0, 2

--- MollyBranch.p04 (plan) ---

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Plan Title=Existing
Short Identifier=Existing
Geom File=g03
Flow File=f02

--- MollyBranch.p08 (plan) ---

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Plan Title=Post Project - Floodway
Short Identifier=POST_FW
Geom File=g05
Flow File=f04
Encroach River=Molly Branch
Encroach Reach=Molly Branch
Encroach Node=27657
       1   180.3   363.5
Encroach Node=26239
       1   900.3  1298.9
Encroach Node=25894
       1   453.5   884.4
Encroach Node=25196
       1   747.4  1052.4
Encroach Node=24524
       1   950.2  1268.2
Encroach Node=23248
       1   489.1   789.1
Encroach Node=22031
       1   796.6  1023.6
Encroach Node=21173
       1  1010.9  1535.1
Encroach Node=20155
       1  1184.7  1544.8
Encroach Node=19792
       1  1414.6  1711.2
Encroach Node=18696
       1  1567.8  1904.3
Encroach Node=18083
       1  1453.8  1743.1
Encroach Node=17922
       1  1452.8  1690.4
Encroach Node=16822
       1  1130.3  1459.5
Encroach Node=15480
       1  2337.7  2591.6
Encroach Node=12224
       1  3715.7  4226.6
Encroach Node=8474
       1  2035.2  2446.3
Encroach Node=7470
       1  1776.2  2159.2
Encroach Node=7171
       1  1558.7  1888.5
Encroach Node=3799
       1  2000.1  2286.1
Encroach Node=1228
       1  2966.8    3311
Encroach Node=442
       1    3034  3603.1

--- MollyBranch.f02 (steady flow) ---

Flow Title=USGS Regression Flowrates
Program Version=6.60
Number of Profiles= 5
Profile Names=10 Year,25 Year,50 Year,100 Year,500 Year
River Rch & RM=Molly Branch,Molly Branch    ,27657
     497     710     907    1110    1620
Boundary for River Rch & Prof#=Molly Branch,Molly Branch    , 1
Up Type= 0
Dn Type= 1
Dn Known WS=6.2
Boundary for River Rch & Prof#=Molly Branch,Molly Branch    , 2
Up Type= 0
Dn Type= 1
Dn Known WS=7.3
Boundary for River Rch & Prof#=Molly Branch,Molly Branch    , 3
Up Type= 0
Dn Type= 1
Dn Known WS=7.3
Boundary for River Rch & Prof#=Molly Branch,Molly Branch    , 4
Up Type= 0
Dn Type= 1
Dn Known WS=9.2
Boundary for River Rch & Prof#=Molly Branch,Molly Branch    , 5
Up Type= 0
Dn Type= 1
Dn Known WS=12.8
DSS Import GetInterval= 0
DSS Import GetPeak= 0
DSS Import FillOption= 0

--- MollyBranch.f01 (steady flow) ---

Flow Title=FEMA Flowrate
Program Version=6.60
Number of Profiles= 1
Profile Names=100 Year
River Rch & RM=Molly Branch,Molly Branch    ,27657
    1208
River Rch & RM=Molly Branch,Molly Branch    ,18696
    1622
Boundary for River Rch & Prof#=Molly Branch,Molly Branch    , 1
Up Type= 0
Dn Type= 3
Dn Slope=0.0003
DSS Import GetInterval= 0
DSS Import GetPeak= 0
DSS Import FillOption= 0

--- MollyBranch.f03 (steady flow) ---

Flow Title=HEC-2 Flowrates
Program Version=6.60
Number of Profiles= 4
Profile Names=10-year,50-year,100-year,500-year
River Rch & RM=RIVER-1,Reach-1         ,2710
     426     761    1016    1680
River Rch & RM=RIVER-1,Reach-1         ,2709.1
     511     910    1208    1986
River Rch & RM=RIVER-1,Reach-1         ,2705.3
     697    1235    1622    2643
Boundary for River Rch & Prof#=RIVER-1,Reach-1         , 1
Up Type= 0
Dn Type= 3
Dn Slope=0.0003
Boundary for River Rch & Prof#=RIVER-1,Reach-1         , 2
Up Type= 0
Dn Type= 3
Dn Slope=0.0003
Boundary for River Rch & Prof#=RIVER-1,Reach-1         , 3
Up Type= 0
Dn Type= 3
Dn Slope=0.0003
Boundary for River Rch & Prof#=RIVER-1,Reach-1         , 4
Up Type= 0
Dn Type= 3
Dn Slope=0.0003
DSS Import GetInterval= 0
DSS Import GetPeak= 0
DSS Import FillOption= 0

--- MollyBranch.f04 (steady flow) ---

Flow Title=FEMA Flowrates - Floodway
Program Version=6.60
Number of Profiles= 2
Profile Names=100 Year,100 Year-Floodway
River Rch & RM=Molly Branch,Molly Branch    ,27657
    1208    1208
River Rch & RM=Molly Branch,Molly Branch    ,18696
    1622    1622
Boundary for River Rch & Prof#=Molly Branch,Molly Branch    , 1
Up Type= 0
Dn Type= 1
Dn Known WS=4
Boundary for River Rch & Prof#=Molly Branch,Molly Branch    , 2
Up Type= 0
Dn Type= 1
Dn Known WS=5
DSS Import GetInterval= 0
DSS Import GetPeak= 0
DSS Import FillOption= 0

--- MollyBranch.g05 (geometry) ---

Geom Title=Proposed
Program Version=6.60

River Reach=Molly Branch    ,Molly Branch
Reach XY= 30
2294953.77987694477046.6166390072295884.49846785476870.768402205
2296062.35359774476373.1748220242296819.31850199476333.469830308
 2297327.3984406475866.8151062372297943.88717011475740.698396977
2298199.11557293475504.7309378112297980.57171523475000.892233124
2298172.15102655474601.9493822462298974.68801215473748.354684894
2300124.08085845473640.3934986632300733.09123276474677.997137113
2301363.27174225474522.7958097952302111.42054284474956.439128378
 2302820.0232945474444.3035973142303357.87019091474766.436440512
2303804.20021727474422.3447741052304501.28893587474533.145592382
2305000.30107571473950.7878161532305344.99636873472912.966420329
2306754.86700228471719.211514908 2307078.3196287470901.512272864
2307438.28385438470917.1320223022307801.84544304  470445.5671894
2308324.25681593470505.1711715432308750.54318799 469851.58575618
2309488.58073158469493.0853341782310094.81671546468761.516664548
2310712.24418215468656.6268224282310680.50602934468139.663384071

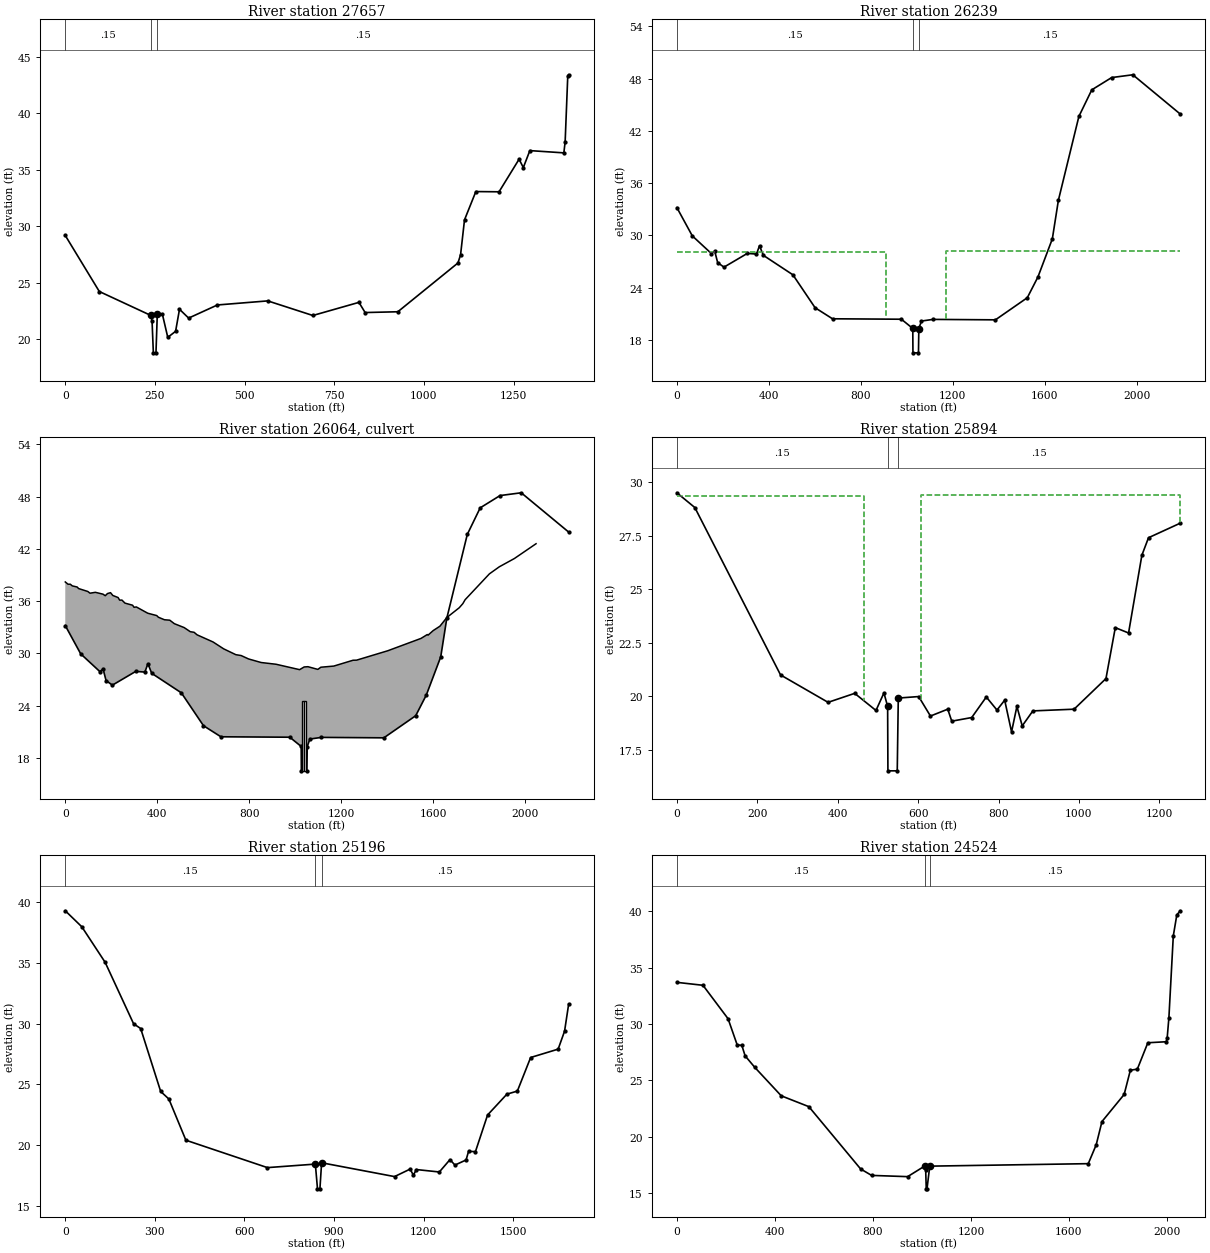
Type RM Length L Ch R = 1 ,27657   ,1418.2,1418.2,1418.2
XS GIS Cut Line= 2
2295447.39724667477241.829840252 2294836.2297664475978.331387144
#Sta/Elev= 30
       0   29.19    94.9   24.24   238.3   22.13     242   21.62   245.6   18.82
   252.9   18.82   256.6   22.26   270.7   22.24   285.8   20.19   307.6   20.72
   318.5   22.67     344   21.89   424.2   23.05   564.6   23.41   690.3   22.12
   818.8   23.28   836.1   22.38   927.3   22.45  1094.9   26.76  1102.2   27.48
  1113.2   30.57  1144.8   33.07  1209.5   33.05  1265.4   35.93  1277.2   35.19
  1295.4   36.69  1390.2   36.49  1393.8   37.46  1401.1   43.27  1403.6   43.39
#Mann= 3 ,0,0
       0     .15       0   238.3     .05       0   256.6     .15       0
Bank Sta=238.3,256.6
XS Rating Curve= 0 ,0
Exp/Cntr(USF)=0,0
Exp/Cntr=0.5,0.3

Type RM Length L Ch R = 1 ,26239   ,345.5,345.5,345.5
XS GIS Cut Line= 4
2295896.65543687477385.9271529422295990.34686615477215.769806444
2296172.09843101475528.3952014922295984.58745675475296.217222474
#Sta/Elev= 30
       0    33.2    67.2   29.95   150.3   27.92   164.6    28.2   177.5   26.88
     205   26.36   306.7   27.94   346.3   27.86   359.5   28.82     376   27.72
   504.8   25.48   601.3    21.7   677.1   20.43   976.7   20.38 1026.28   19.32
 1027.02   16.52 1051.04   16.52 1052.57   19.31 1064.14   20.17 1114.09   20.36
  1385.9   20.31  1524.5   22.85  1570.7   25.23  1633.4   29.61  1659.8   34.05
  1748.9   43.67    1805   46.72  1891.4   48.13  1983.5   48.452189.822   43.94
#Mann= 3 ,0,0
       0     .15       0 1026.28     .05       0 1052.57     .15       0
#XS Ineff= 2 , 0
             908   28.14    1169           28.17
Permanent Ineff=
       F       F
Bank Sta=1026.28,1052.57
XS Rating Curve= 0 ,0
Exp/Cntr(USF)=0,0
Exp/Cntr=0.5,0.3

Type RM Length L Ch R = 2 ,26064   ,,,
Node Name=US HWY 52 (Culve
Bridge Culvert-0,0,0,0, 0
Deck Dist Width WeirC Skew NumUp NumDn MinLoCord MaxHiCord MaxSubmerge Is_Ogee
125.6062,100,2.6,0, 60, 35, , , 0.98, 0, 2,2,,
       0      12    21.9    30.4    51.6    58.2    97.8   107.7   130.9   163.9
   173.8   183.7   196.9   206.8   229.8   236.6   246.5   259.7   292.7   299.3
   309.2   358.8   397.8     405   431.4   454.6   474.4   517.3   543.7   560.3
   573.3   642.8     689   741.9     765   797.3     852     917  1019.4  1039.2
  1055.7  1098.6  1111.9    1168  1251.8  1267.1  1402.9  1547.7  1574.7    1578
  1600.7  1629.8  1660.1  1713.9  1729.5  1739.4  1845.1  1888.1  1953.7    2048
   38.21   37.95   37.95   37.76   37.63   37.45   37.12   36.92   37.02   36.81
   36.63   36.88   36.98   36.66   36.42   36.12   36.13   35.78   35.54    35.3
   35.34   34.62   34.35   34.16   33.87   33.82   33.42   32.97    32.5   32.43
   32.14   31.32   30.53   29.86   29.76   29.37   28.96   28.76   28.14   28.45
   28.48   28.17   28.42   28.55   29.22   29.23   30.31   31.73   32.17    32.1
   32.63   33.13   34.13   35.25   35.72   36.17   39.14   39.95    40.9    42.6
                                                                                
                                                                                
                                                                                
                                                                                
                                                                                
                                                                                
       0    19.3  25.927  52.433  63.119  75.626  92.193  101.65 141.892 191.592
 211.471 221.411 268.149  310.87  320.81 377.136 479.849 483.162 519.608 552.741
 575.934 605.754 628.947 698.264 741.599 787.986 794.612 855.198 864.192 917.204
1069.6161165.7021185.5821195.919 1251.95
  33.974  33.531   33.51  33.166  32.934  32.836  32.531  32.471  31.844  31.271
  30.938   30.94  30.368  30.125  29.965  29.703   29.38  29.438  29.342   29.44
  29.409  29.646  29.714  30.121  30.443  30.883  31.022   31.54   31.71  32.354
  34.701  36.438  36.678  36.971   37.97
                                                                                
                                                                                
                                                                                
                                        
BR Coef=-1 , 0 , 0 ,, 0 ,,,0.8,0,,0,
WSPro=,,,, 1 ,,,, 0 ,,,, 0 ,,,,-1 ,-1 ,-1 , 0 , 0 , 0 , 0 , 0
Multiple Barrel Culv=2,8,10,144,0.012,0.4,1,8,1,16.52,16.52, 2,Culvert #1  , 0 ,110
    1033     531    1044     542
BC Culvert Barrel=1,Barrel #1,0
BC Culvert Barrel=2,Barrel #2,0
Culvert Bottom n=0.012
BC Design=,, 0 ,, 0 ,,,,,,
BC Use User HTab Curves=0
BC User HTab FreeFlow(D)= 0

Type RM Length L Ch R = 1 ,25894   ,700.8,700.8,700.8
XS GIS Cut Line= 3
2296564.99415666476856.3683319612296374.88456493476664.346043196
2296496.23805733475690.137129903
#Sta/Elev= 30
       0   29.51    44.7   28.82   257.9      21   376.1   19.72   442.3   20.14
   495.2   19.34     515   20.16   524.2   19.53   524.9   16.52   548.1   16.52
   550.7   19.92   601.4   19.99   630.7   19.08   673.7    19.4   683.7   18.84
   733.3   19.01   769.6   19.97   796.1   19.36   815.3   19.82   832.4   18.34
   845.7   19.53   858.9   18.62   885.4   19.32   987.9    19.4  1067.2   20.83
  1090.4   23.21  1123.4   22.96  1156.5   26.59    1173   27.411251.949   28.09
#Mann= 3 ,0,0
       0     .15       0   524.2     .05       0   550.7     .15       0
#XS Ineff= 2 , 0
             466   29.35     607           29.41
Permanent Ineff=
       F       F
Bank Sta=524.2,550.7
XS Rating Curve= 0 ,0
Exp/Cntr(USF)=0,0
Exp/Cntr=0.5,0.3

Type RM Length L Ch R = 1 ,25196   ,673.9,673.9,673.9
XS GIS Cut Line= 4
2297479.04840794476836.0231643572296994.28022156476369.479345889
2296793.81217456475815.4585614572296535.02615026475480.130191933
#Sta/Elev= 30
       0   39.31    55.4   37.99   133.5   35.06   228.8   29.99   252.5    29.6
   319.5   24.41   346.8   23.79   403.9   20.39   676.9   18.13   837.4   18.42
  844.57   16.38  852.76   16.39   858.3   18.53  1102.6   17.39  1154.9   18.01
  1165.4   17.51  1175.9   17.97  1252.6   17.77  1288.2   18.79  1304.8   18.34
  1342.1   18.76  1350.4   19.47  1373.5   19.45  1414.1   22.47  1478.9   24.19
  1513.8   24.44  1558.3   27.21  1650.4    27.9  1671.9   29.38  1685.6   31.61
#Mann= 3 ,0,0
       0     .15       0   837.4     .05       0   858.3     .15       0
Bank Sta=837.4,858.3
XS Rating Curve= 0 ,0
Exp/Cntr(USF)=0,0
Exp/Cntr=0.3,0.1

Type RM Length L Ch R = 1 ,24524   ,1280.3,1280.3,1280.3
XS GIS Cut Line= 4
2297994.68892365476640.2097420222297473.23738333476084.443016171
 2297125.3413115475543.7609698412296530.48881124475283.598300718
#Sta/Elev= 30
       0   33.69  106.54   33.43   208.9   30.47  246.02   28.16  265.24    28.1
  278.54   27.18  318.01   26.16     426   23.64  538.59   22.68  749.96   17.16
  794.79   16.59  941.73   16.48 1012.99   17.44 1015.41   17.06 1017.78    15.4
 1020.79    15.4 1032.03   17.41 1678.93   17.63  1711.3    19.3 1734.84   21.36
 1825.37   23.76 1850.76   25.91 1879.09      26 1922.06   28.34 1997.27   28.43
 2000.85   28.74 2008.01   30.57 2025.92    37.8 2040.25   39.66 2054.29   40.03
#Mann= 3 ,0,0
       0     .15       0 1012.99     .05       0 1032.03     .15       0
Bank Sta=1012.99,1032.03
XS Rating Curve= 0 ,0
Exp/Cntr(USF)=0,0
Exp/Cntr=0.3,0.1

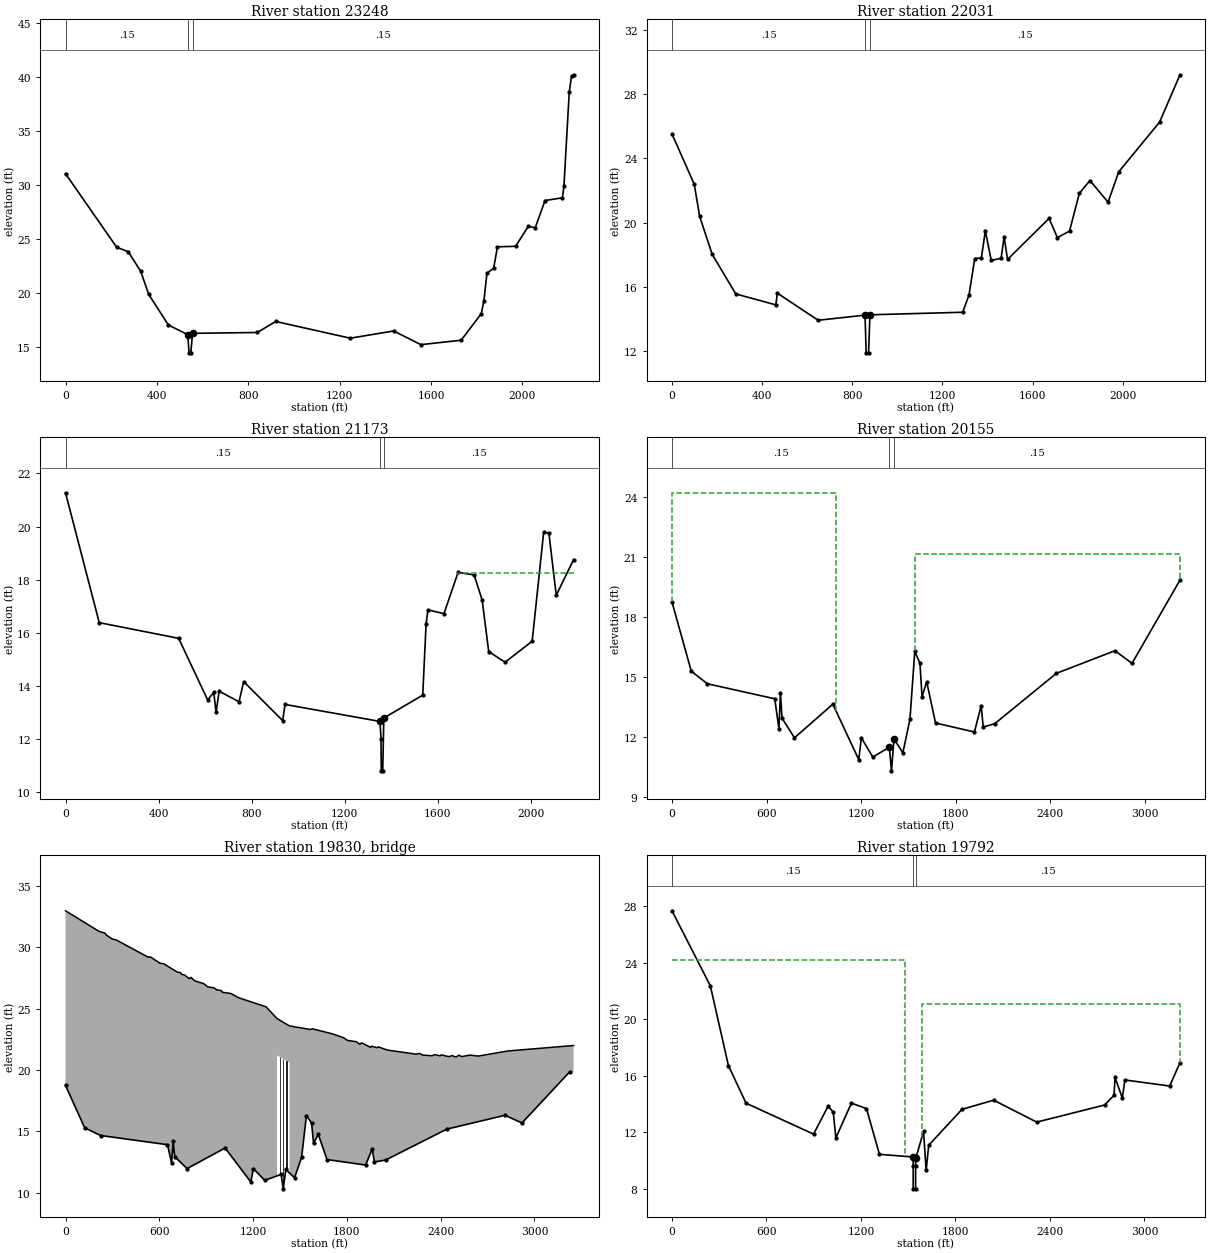
Type RM Length L Ch R = 1 ,23248   ,1221.2,1221.2,1221.2
XS GIS Cut Line= 5
2298316.59138258475999.8499942472297908.36554142475485.922819215
 2297478.1643565 475057.695296892297018.98440928474659.386452278
2296669.04131215474613.641478332
#Sta/Elev= 30
       0   31.05  224.05   24.22  274.57   23.81  329.04      22  364.17   19.85
  450.56      17     535  16.111  541.06   14.42  548.61   14.43   556.1  16.229
  839.39   16.31  920.24   17.33 1246.54   15.78 1436.62   16.45 1555.72   15.18
 1731.99   15.59 1819.92   18.04  1831.9   19.25 1844.93   21.82 1874.35   22.26
  1890.9   24.26 1970.32   24.31 2026.17   26.16 2056.35   26.03 2099.37   28.56
 2175.49   28.81  2182.1   29.92 2205.27   38.62  2215.2   40.09 2224.11   40.23
#Mann= 3 ,0,0
       0     .15       0     535     .05       0   556.1     .15       0
Bank Sta=535,556.1
XS Rating Curve= 0 ,0
Exp/Cntr(USF)=0,0
Exp/Cntr=0.3,0.1

Type RM Length L Ch R = 1 ,22031   ,860.4,860.4,860.4
XS GIS Cut Line= 4
 2298374.7749786475643.6365210732298196.78501568475020.671650853
2297462.57641864474375.4580352672296848.51104656474241.965563077
#Sta/Elev= 30
       0   25.52    98.8   22.39   122.7   20.39   178.1   18.03   283.1   15.55
   460.6   14.87   467.6    15.6   648.4   13.91   856.4   14.23   861.5   11.88
   872.1   11.88   878.1   14.25  1289.6   14.41  1317.5   15.48  1343.1   17.75
  1372.6    17.8  1390.1   19.48  1416.3   17.64    1460   17.77  1473.6   19.11
  1488.5    17.7  1672.8   20.26  1709.7   19.06  1763.5   19.47  1807.1   21.82
  1854.1   22.62  1934.7   21.27  1981.7   23.16  2163.1   26.26  2253.7   29.21
#Mann= 3 ,0,0
       0     .15       0   856.4     .05       0   878.1     .15       0
Bank Sta=856.4,878.1
XS Rating Curve= 0 ,0
Exp/Cntr(USF)=0,0
Exp/Cntr=0.3,0.1

Type RM Length L Ch R = 1 ,21173   ,1023.7,1023.7,1023.7
XS GIS Cut Line= 4
2298464.63348067475482.3068462552298543.91130464475175.062565514
 2298458.7141105474091.6341057772298004.00743594473459.176653515
#Sta/Elev= 30
       0   21.27     145   16.38  486.11   15.79   610.8   13.47   637.1   13.75
     647      13   660.1    13.8   745.7    13.4   765.5   14.16   933.3   12.69
   943.2    13.3  1351.3   12.66 1355.78      12 1356.86    10.8 1363.11    10.8
  1367.8   12.79    1535   13.65  1549.5   16.34  1557.5   16.86  1626.2   16.72
  1686.9   18.27  1755.6   18.18  1790.4   17.23  1818.5   15.29  1888.9   14.89
  2005.2   15.68  2054.6   19.78  2077.1   19.75  2108.7   17.412183.029   18.75
#Mann= 3 ,0,0
       0     .15       0  1351.3     .05       0  1367.8     .15       0
#XS Ineff= 2 , 0
                          1682.8           18.24
Permanent Ineff=
       F       T
Bank Sta=1351.3,1367.8
XS Rating Curve= 0 ,0
Exp/Cntr(USF)=0,0
Exp/Cntr=0.5,0.3

Type RM Length L Ch R = 1 ,20155   ,363.3,363.3,363.3
XS GIS Cut Line= 3
2299142.12844069475158.7680250082298919.08597953472336.184381327
2299025.60508151471957.733222669
#Sta/Elev= 30
       0   18.75  122.42   15.29  224.46   14.66  652.35   13.91  678.68   12.42
  688.56   14.21  698.43   12.94  777.43   11.96    1021   13.64 1185.57   10.87
 1202.03   11.96 1274.44      11  1379.8  11.489 1392.93   10.31  1409.4  11.899
 1465.35   11.21 1510.57   12.89 1541.05   16.28 1573.97   15.69 1587.13   14.01
 1616.76   14.76 1672.71    12.7 1919.57   12.25 1962.36   13.56 1975.53    12.5
 2047.94   12.66 2439.63   15.18 2811.57   16.31 2919.94   15.68 3224.54   19.84
#Mann= 3 ,0,0
       0     .15       0  1379.8     .05       0  1409.4     .15       0
#XS Ineff= 2 , 0
            1042    24.2 1541.05           21.12
Permanent Ineff=
       F       F
Bank Sta=1379.8,1409.4
XS Rating Curve= 0 ,0
Exp/Cntr(USF)=0,0
Exp/Cntr=0.5,0.3

Type RM Length L Ch R = 3 ,19830   ,,,
Node Name=Rail Bridge
Bridge Culvert-0,0,0,0, 0
Deck Dist Width WeirC Skew NumUp NumDn MinLoCord MaxHiCord MaxSubmerge Is_Ogee
326.1011,14,2.6,0, 60, 60, , , 0.98, 0, 2,2,,
       0 212.567 254.646 260.909 300.187 327.249 524.928 544.696     604 627.741
 716.018 735.786 742.375 761.765 791.795 801.679 828.036 884.045 910.506 950.123
 966.412 996.0641002.6531058.7921104.7871282.698    1353    1353    1433    1433
1566.1461579.2171707.7091779.6251803.2541862.2411882.3261895.5381951.5131958.103
1991.0492000.9332060.2372241.4432264.5052284.2732343.5772363.3452396.2922402.881
2452.3012477.9862485.2472505.0152514.9482534.6672587.2652640.096 2831.38    3250
   32.99  31.325  31.154  31.008  30.689  30.594  29.233  29.214  28.715  28.671
  27.984  27.952  27.809   27.75  27.452  27.561  27.269  27.048  26.782  26.705
  26.547  26.482  26.344   26.24  25.909  25.158    24.2    24.2    23.6    23.6
  23.308  23.365  22.951  22.632   22.42  22.305  22.101  22.218  21.847  21.949
  21.821  21.888  21.627  21.297  21.358   21.22  21.166  21.258  21.157  21.238
  21.094  21.188  21.088  21.093  21.216  21.097  21.219  21.139  21.557      22
                                                                                
                                                                                
                                                            21.2    20.6
                                                                                
                                                                                
                                                                                
       0 212.567 254.646 260.909 300.187 327.249 524.928 544.696     604 627.741
 716.018 735.786 742.375 761.765 791.795 801.679 828.036 884.045 910.506 950.123
 996.0641002.6531058.7921104.7871282.6981332.1181338.7081391.4221401.306    1495
    1495    1575    15751582.5121749.4581803.2541862.2411882.3261895.5381951.513
1958.1031991.0492000.9332060.2372241.4432264.5052284.2732343.5772363.3452396.292
2402.8812452.3012477.9862485.2472505.0152514.9482534.6672745.5253074.991 3225.55
   32.99  31.325  31.154  31.008  30.689  30.594  29.233  29.214  28.715  28.671
  27.984  27.952  27.809   27.75  27.452  27.561  27.269  27.048  26.782  26.705
  26.482  26.344   26.24  25.909  25.158  24.861  24.724  24.484   24.33    24.2
    24.2    23.6    23.6  23.307  22.792   22.42  22.305  22.101  22.218  21.847
  21.949  21.821  21.888  21.627  21.297  21.358   21.22  21.166  21.258  21.157
  21.238  21.094  21.188  21.088  21.093  21.216  21.097  21.292  22.287  22.288
                                                                                
                                                                                
                                                                                
    21.2    20.6
                                                                                
                                                                                
Pier Skew, UpSta & Num, DnSta & Num=  ,1373, 2 ,1515, 2 , 0 , 0 , 0 ,,
       3       3
       0    21.2
       3       3
       0    21.2
Pier Skew, UpSta & Num, DnSta & Num=  ,1393, 2 ,1535, 2 , 0 , 0 , 0 ,,
       3       3
       0    21.2
       3       3
       0    21.2
Pier Skew, UpSta & Num, DnSta & Num=  ,1413, 2 ,1555, 2 , 0 , 0 , 0 ,,
       3       3
       0    21.2
       3       3
       0    21.2
BR Coef=-1 ,-1 , 0 ,, 0 ,,,0.8,0,1.2,0,
WSPro=,,,, 1 ,,,, 0 ,,,, 0 ,,,,-1 ,-1 ,-1 , 0 , 0 , 0 , 0 , 0
BC Design=,, 0 ,, 0 ,,,,,,
BC Use User HTab Curves=0
BC User HTab FreeFlow(D)= 0

Type RM Length L Ch R = 1 ,19792   ,1092.6,1092.6,1092.6
XS GIS Cut Line= 5
 2299634.6870197475294.091727076 2299616.2227578475270.447044112
2299482.54225944475099.2605098662299238.24275974472407.352372922
2299365.07760381472209.062304277
#Sta/Elev= 30
       0  27.695 243.662  22.377 358.508  16.718 470.529  14.065 898.846  11.875
 991.099  13.8531024.046  13.426 1040.52  11.6081139.362  14.072 1234.91  13.683
1317.278  10.443 1530.97   10.26 1531.57    9.62 1531.57       8  1546.7       8
    1547    9.64 1547.89   10.161597.332  12.0671613.805     9.31630.161   11.09
1841.143   13.632042.122  14.281 2315.84  12.7262747.198  13.9382806.503  14.629
2813.093  15.8882859.219  14.4342875.693  15.7123160.222  15.2813225.554  16.948
#Mann= 3 ,0,0
       0     .15       0 1530.97     .05       0 1547.89     .15       0
#XS Ineff= 2 , 0
            1482    24.2    1588           21.12
Permanent Ineff=
       F       F
Bank Sta=1530.97,1547.89
XS Rating Curve= 0 ,0
Exp/Cntr(USF)=0,0
Exp/Cntr=0.5,0.3

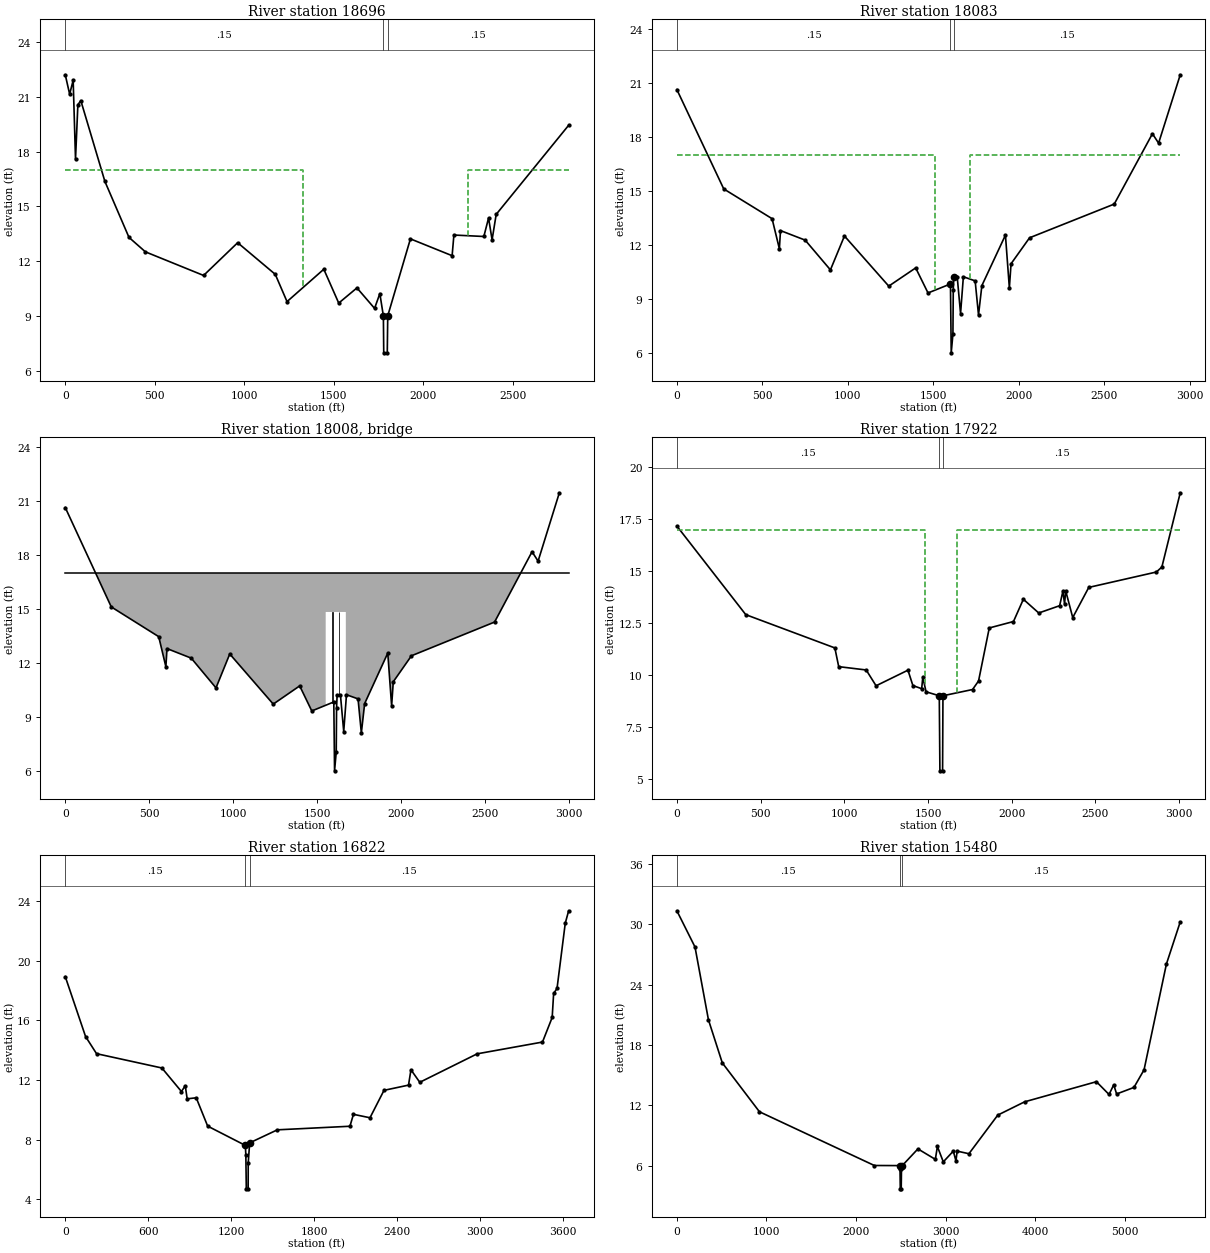
Type RM Length L Ch R = 1 ,18696   ,612.4,612.4,612.4
XS GIS Cut Line= 3
2300024.55007655475467.9829793192300108.29334628472922.503459534
2299989.45341796472684.645367073
#Sta/Elev= 30
       0    22.2    24.4   21.14    44.1    21.9    57.2   17.59    70.4   20.56
    86.8   20.79   221.4   16.37     356   13.31   447.9   12.52   772.9   11.23
   963.3   13.02  1173.5   11.29  1239.1     9.8  1444.6   11.57    1528    9.72
  1629.8   10.55  1728.3    9.43  1757.8   10.24 1777.53    9.01 1779.49       7
 1799.22       7 1801.83    9.02  1928.6   13.23  2161.6   12.31  2171.5   13.44
  2338.9   13.36  2365.2   14.37  2384.9   13.18  2407.9   14.57 2812.75   19.44
#Mann= 3 ,0,0
       0     .15       0 1777.53     .05       0 1801.83     .15       0
#XS Ineff= 2 , 0
        1328.225      172247.775              17
Permanent Ineff=
       F       F
Bank Sta=1777.53,1801.83
XS Rating Curve= 0 ,0
Exp/Cntr(USF)=0,0
Exp/Cntr=0.5,0.3

Type RM Length L Ch R = 1 ,18083   ,161.3,161.3,161.3
XS GIS Cut Line= 4
2300186.99074373475628.5958880842300222.43609811475109.814625074
2300214.47431246473089.2015948242300225.02926711472685.421104403
#Sta/Elev= 30
       0   20.63  274.22   15.12  556.98   13.47  599.64    11.8   606.2   12.81
  750.58   12.28  898.24   10.63  980.27   12.51 1239.49    9.73 1396.99   10.74
 1469.18    9.351600.391   9.851 1604.85    6.03 1614.85    7.07 1616.84    9.54
1620.091  10.211 1639.81   10.25 1659.49    8.21  1675.9   10.25 1744.81   10.02
  1764.5    8.13 1784.18    9.76    1922   12.56 1944.97    9.63 1954.81   10.97
 2063.09   12.41 2558.43   14.28 2781.77   18.18 2817.88   17.66 2944.54   21.45
#Mann= 3 ,0,0
       0     .15       01600.391     .05       01620.091     .15       0
#XS Ineff= 2 , 0
        1507.225      171716.775              17
Permanent Ineff=
       F       F
Bank Sta=1600.391,1620.091
XS Rating Curve= 0 ,0
Exp/Cntr(USF)=0,0
Exp/Cntr=0.5,0.3

Type RM Length L Ch R = 3 ,18008   ,,,
Node Name=S-791 over Molly
Bridge Culvert-0,0,0,0, 0
Deck Dist Width WeirC Skew NumUp NumDn MinLoCord MaxHiCord MaxSubmerge Is_Ogee
31.35134,42.25,2.6,0, 6, 6, , , 0.98, 0, 2,2,,
       0 1551.99    1552    1672 1672.01    3000
      17      17      17      17      17      17
                   14.84   14.84
       0 1517.99    1518    1638 1638.01    3000
      17      17      17      17      17      17
                   14.84   14.84
Pier Skew, UpSta & Num, DnSta & Num=  ,1592, 2 ,1558, 2 , 0 , 0 , 0 ,,
       2       2
       0      17
       2       2
       0      17
Pier Skew, UpSta & Num, DnSta & Num=  ,1632, 2 ,1598, 2 , 0 , 0 , 0 ,,
       2       2
       0      17
       2       2
       0      17
Abutment Skew #Up #Dn= , 3 , 3
 1551.99    1554    1574
      13      13       3
 1517.99    1520    1540
      13      13       3
Abutment Skew #Up #Dn= , 3 , 3
    1650    1670 1672.01
       3      13      13
    1616    1636 1638.01
       3      13      13
BR Coef=-1 ,-1 , 0 ,, 0 ,,,0.8,0,2,0,
WSPro=,,,, 1 ,,,, 0 ,,,, 0 ,,,,-1 ,-1 ,-1 , 0 , 0 , 0 , 0 , 0
BC Design=,, 0 ,, 0 ,,,,,,
BC Use User HTab Curves=0
BC User HTab FreeFlow(D)= 0

Type RM Length L Ch R = 1 ,17922   ,1100.1,1100.1,1100.1
XS GIS Cut Line= 6
2300285.47475126475653.991477348  2300324.165683475107.507806008
2300334.00372776474708.9008433122300367.36918183473321.682391052
  2300465.122102473091.7592232922300474.04149011472669.476386347
#Sta/Elev= 30
       0   17.18  411.57   12.92   943.6   11.32  966.57   10.42 1130.68   10.26
 1189.76     9.5 1380.13   10.25 1409.67    9.51 1462.18    9.36 1468.75    9.91
 1488.44    9.21 1567.27    9.02    1571    5.41    1587    5.41 1589.22    9.02
 1765.93    9.32 1801.76    9.73 1865.82   12.28 2010.44   12.59 2069.39   13.66
  2161.3      13 2286.02   13.35 2305.71   14.05 2315.56   13.43 2322.12   14.07
  2364.3   12.78 2460.14   14.23 2863.83   14.97 2896.65   15.21 3006.42   18.78
#Mann= 3 ,0,0
       0     .15       0 1567.27     .05       0 1589.22     .15       0
#XS Ineff= 2 , 0
        1479.225      171674.775              17
Permanent Ineff=
       F       F
Bank Sta=1567.27,1589.22
XS Rating Curve= 0 ,0
Exp/Cntr(USF)=0,0
Exp/Cntr=0.5,0.3

Type RM Length L Ch R = 1 ,16822   ,1341.8,1341.8,1341.8
XS GIS Cut Line= 4
  2300390.706536475927.7878954462300805.16248982474646.010543839
2301089.14653618473778.8309656652300603.66074603472487.241709627
#Sta/Elev= 30
       0   18.94  146.77   14.92  226.09   13.77  698.53   12.81  839.92   11.23
  867.51   11.62  881.31   10.74  946.83   10.81 1029.43    8.91    1302   7.614
  1305.5    6.96  1308.9     4.7  1322.2     4.7 1322.72    6.43  1333.1   7.785
  1533.3    8.66  2058.1     8.9  2083.4     9.7  2203.1    9.47  2304.4   11.31
  2481.6   11.66  2499.3   12.69  2563.1   11.85  2977.8   13.76  3450.2   14.55
  3520.3    16.2 3530.82   17.81 3555.36   18.15 3614.95   22.53 3639.43   23.36
#Mann= 3 ,0,0
       0     .15       0    1302     .05       0  1333.1     .15       0
Bank Sta=1302,1333.1
XS Rating Curve= 0 ,0
Exp/Cntr(USF)=0,0
Exp/Cntr=0.3,0.1

Type RM Length L Ch R = 1 ,15480   ,3610.7,3610.7,3610.7
XS GIS Cut Line= 4
2300600.45025837476921.7862058792301977.62214693474487.534857548
2301919.76998267 473459.716659132300881.39247724472000.584476785
#Sta/Elev= 30
       0   31.34  202.37   27.74  352.46    20.5  507.03   16.22  921.73   11.36
 2203.52    6.02  2486.3    6.01 2489.87    5.72 2493.09     3.7 2503.43     3.7
 2506.48    5.69 2509.87    5.96  2689.9    7.67  2884.3    6.63  2907.3    7.91
  2973.1    6.38  3084.8    7.45  3114.4    6.47  3127.5    7.45    3259    7.19
  3581.1   11.03 3880.55   12.35  4681.6   14.35 4822.57   13.08 4874.93   14.04
 4907.15   13.13 5100.46   13.78 5213.22   15.53 5462.91   26.05 5617.15   30.24
#Mann= 3 ,0,0
       0     .15       0  2486.3     .05       0 2509.87     .15       0
Bank Sta=2486.3,2509.87
XS Rating Curve= 0 ,0
Exp/Cntr(USF)=0,0
Exp/Cntr=0.3,0.1

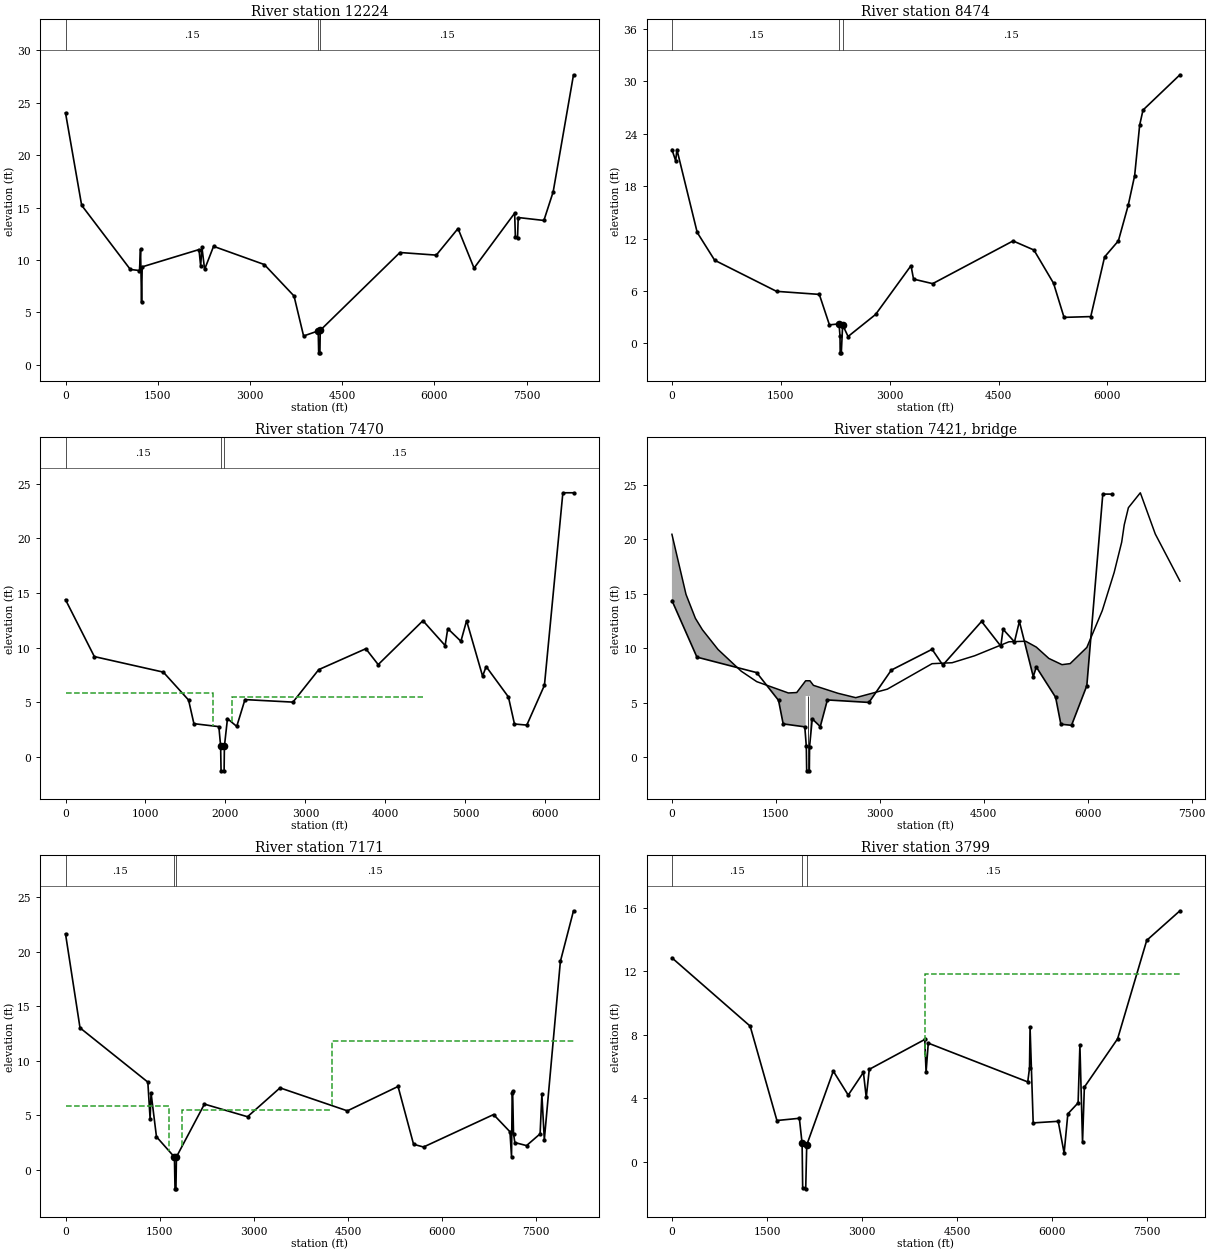
Type RM Length L Ch R = 1 ,12224   ,3470.5,3470.5,3470.5
XS GIS Cut Line= 6
2303201.92278718478523.3426437152304019.79159645475297.053528691
2303807.41682277473864.653459416    2302334.2608473294.012391712
2301643.44404563472696.2489755222301117.25383149471851.894799924
#Sta/Elev= 30
       0   24.05  262.62   15.22 1054.73    9.09 1203.67    8.99 1220.59      11
 1237.52    5.94 1247.67    9.34 2171.79   10.99 2198.87    9.42 2219.18   11.22
 2263.19     9.1 2408.75    11.3  3234.7    9.56 3717.56    6.56 3873.47    2.74
  4111.3   3.225  4118.9    1.13  4138.8    1.13  4144.1   3.279 5440.76   10.71
 6031.93   10.46 6385.83      13  6646.5    9.22 7307.31   14.47  7318.9   12.18
  7353.7   12.08  7365.3   14.05 7782.86   13.77 7933.64    16.5 8264.64   27.68
#Mann= 3 ,0,0
       0     .15       0  4111.3     .05       0  4144.1     .15       0
Bank Sta=4111.3,4144.1
XS Rating Curve= 0 ,0
Exp/Cntr(USF)=0,0
Exp/Cntr=0.3,0.1

Type RM Length L Ch R = 1 ,8474    ,928.6,928.6,928.6
XS GIS Cut Line= 5
2307465.23007496473852.2632992632306407.73022779473660.687239993
2304687.28346452470923.3671201992304619.95334907470419.752501845
2302440.50010891 470290.32054558
#Sta/Elev= 30
       0    22.2   51.89   20.91   68.57    22.2  348.36   12.71  588.77    9.53
 1440.99    5.97 2030.56    5.62 2170.08    2.13  2302.5   2.248  2315.8     .83
 2318.23   -1.07  2333.7   -1.07  2352.2   2.129 2426.81      .8 2805.67    3.32
 3293.99    8.91 3328.87    7.37 3592.34    6.85 4700.14   11.74 4987.66    10.7
 5257.78     6.9 5402.41    2.99 5770.56    3.08 5961.21    9.91  6151.2   11.75
 6286.62   15.82 6375.37   19.22  6444.4      25 6490.42   26.72 6999.19   30.76
#Mann= 3 ,0,0
       0     .15       0  2302.5     .05       0  2352.2     .15       0
#XS Ineff= 1 ,-1
 4700.14 6999.19   11.74
Permanent Ineff=
       T
Bank Sta=2302.5,2352.2
XS Rating Curve= 0 ,0
Exp/Cntr(USF)=0,0
Exp/Cntr=0.5,0.3

Type RM Length L Ch R = 1 ,7470    ,299.5,299.5,299.5
XS GIS Cut Line= 6
2307194.56397596473653.2851631152306889.41877251473462.565349058
2306548.61745281472309.7381026542304868.58233154469995.442911407
2304612.21818741469470.5068067732303343.12746493469073.797623002
#Sta/Elev= 30
       0   14.39  360.72    9.19 1222.97    7.77 1538.57    5.22 1605.31    3.06
 1917.29    2.79 1939.29    1.01 1944.74   -1.25 1982.87   -1.25  1986.4     .98
 2024.86    3.52 2140.77    2.81 2243.54    5.26 2843.42    5.03 3166.02       8
 3754.53    9.91 3909.25    8.46  4468.6   12.47 4746.13    10.2    4779   11.75
 4943.32   10.59 5014.43   12.47  5214.4     7.4 5258.82    8.28 5537.28     5.5
 5612.91    3.03 5767.03    2.93 5987.64    6.57 6217.97   24.16    6351   24.16
#Mann= 3 ,0,0
       0     .15       0 1939.29     .05       0  1986.4     .15       0
#XS Ineff= 3 ,-1
       0    1840     5.9    2082    4467    5.47    4467    6351   12.33
Permanent Ineff=
       F       F       T
Bank Sta=1939.29,1986.4
XS Rating Curve= 0 ,0
Exp/Cntr(USF)=0,0
Exp/Cntr=0.5,0.3

Type RM Length L Ch R = 3 ,7421    ,,,
Node Name=S Mulberry Dr Br
Bridge Culvert-0,0,0,0, 0
Deck Dist Width WeirC Skew NumUp NumDn MinLoCord MaxHiCord MaxSubmerge Is_Ogee
81.45168,20,2.6,0, 35, 36, , , 0.98, 0, 2,2,,
       0 203.316 338.375 440.207 665.4921000.1421224.3061680.0731801.013    1930
    1930    1992    19922041.9822395.3312652.1583108.5243753.885 4043.844369.271
4863.0515105.1075258.735 5439.625628.8445747.1735987.7916210.4266382.1586490.783
6527.3946587.3036759.623 6975.587331.213
   20.47  14.949  12.758  11.701   9.892   7.899   6.938     5.9    5.94    7.02
    7.02    7.02    7.02     6.6   5.873   5.469    6.25   8.588   8.677   9.317
  10.598   10.65  10.111   9.071     8.5   8.596  10.082  13.461  16.969   19.75
  21.331   22.91  24.281  20.493  16.174
                                                                                
    5.62    5.62
                                                                                
                                        
    -210  -6.684 128.375 230.207 455.492 790.1421014.3061470.0731591.013    1720
    1720    1782    17821831.9822185.3312442.1582898.5243543.885 3833.844159.271
4653.0514895.1075048.735 5229.625418.8445537.1735777.7916000.4266172.1586280.783
6317.3946377.3036549.623 6765.587121.213    9000
   20.47  14.949  12.758  11.701   9.892   7.899   6.938     5.9    5.94    7.02
    7.02    7.02    7.02     6.6   5.873   5.469    6.25   8.588   8.677   9.317
  10.598   10.65  10.111   9.071     8.5   8.596  10.082  13.461  16.969   19.75
  21.331   22.91  24.281  20.493  16.174   16.17
                                                                                
    5.62    5.62
                                                                                
                                                
Pier Skew, UpSta & Num, DnSta & Num=  ,1961, 2 ,1751, 2 , 0 , 0 , 0 ,,
       2       2
   -1.25    5.62
       2       2
   -1.75    5.62
BR Coef=-1 ,-1 , 0 ,, 0 ,,,0.8,0,1.2,0,
WSPro=,,,, 1 ,,,, 0 ,,,, 0 ,,,,-1 ,-1 ,-1 , 0 , 0 , 0 , 0 , 0
BC Design=,, 0 ,, 0 ,,,,,,
BC Use User HTab Curves=0
BC User HTab FreeFlow(D)= 0

Type RM Length L Ch R = 1 ,7171    ,3371.9,3371.9,3371.9
XS GIS Cut Line= 6
2307800.45642528472987.6749705862307585.52816116472547.116624796
2306675.06484271472114.6726676152305125.31538718 469702.24004745
2303865.22877578466447.7692515242303893.69220764466212.424987343
#Sta/Elev= 30
       0   21.67  231.28   13.03 1311.96    8.05 1348.29    4.67 1363.22    7.05
 1449.42    3.03 1735.54    1.17 1745.05   -1.75 1759.83   -1.75 1767.58    1.18
 2213.61    6.03 2900.24    4.87 3418.11    7.52 4491.43    5.41 5298.88    7.65
 5546.08    2.34 5704.99    2.09 6820.89    5.07  7082.2    3.49 7106.92    1.19
 7117.52    7.03 7124.58    7.22 7138.71    3.32 7159.89     2.5 7346.45    2.22
 7562.46     3.3 7590.72    6.92 7629.56    2.76 7885.44   19.13 8094.67   23.78
#Mann= 3 ,0,0
       0     .15       0 1735.54     .05       0 1767.58     .15       0
#XS Ineff= 3 ,-1
       0    1645     5.9    1857    4240    5.47    4240 8094.67    11.8
Permanent Ineff=
       F       F       T
Bank Sta=1735.54,1767.58
XS Rating Curve= 0 ,0
Exp/Cntr(USF)=0,0
Exp/Cntr=0.5,0.3

Type RM Length L Ch R = 1 ,3799    ,2571.5,2571.5,2571.5
XS GIS Cut Line= 4
2308735.98360581472293.6895255462308532.76960032470380.090973861
2307381.22356922468805.182431324  2306077.267034 464876.37832521
#Sta/Elev= 30
       0   12.85  1234.2    8.55  1656.5    2.61  2010.6    2.75  2053.8    1.17
  2062.8   -1.61  2110.7   -1.69  2126.9    1.07  2545.6    5.72  2781.4    4.21
  3021.2    5.64  3065.9    4.06  3113.5    5.83  3989.1    7.71  4009.7    5.65
  4044.3    7.48  5613.9    5.04  5641.6    5.91  5650.4    8.47  5699.7    2.46
  6094.5    2.56  6187.8     .56  6246.6    3.03  6408.4    3.72  6436.7    7.35
  6478.2    1.23    6507    4.71  7031.4    7.75  7491.2   13.95  8014.9   15.81
#Mann= 3 ,0,0
       0     .15       0  2053.8     .05       0  2126.9     .15       0
#XS Ineff= 2 , 0
       0                    4000       0    11.8
Permanent Ineff=
       F       T
Bank Sta=2053.8,2126.9
XS Rating Curve= 0 ,0
Exp/Cntr(USF)=0,0
Exp/Cntr=0.5,0.3