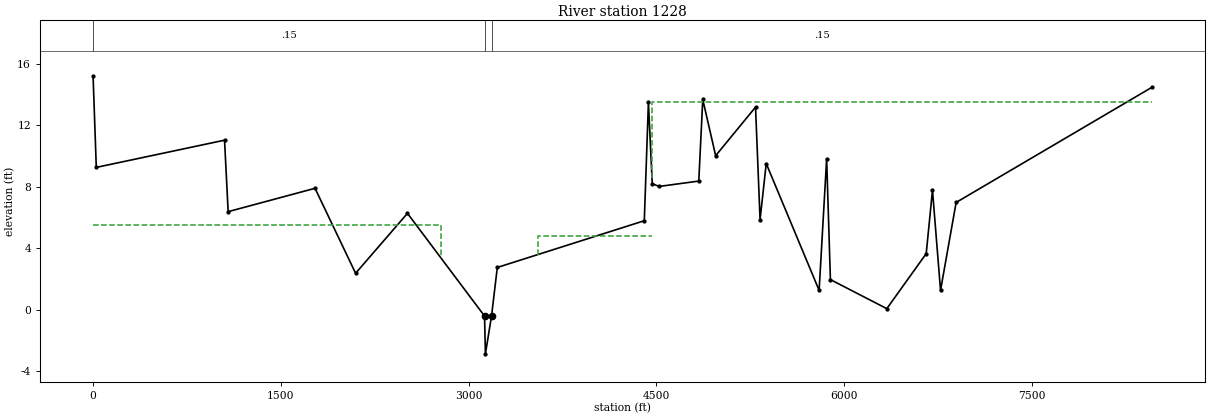
HEC-RAS study MollyBranch.prj: S-8-791 over Molly Branch Creek

--- MollyBranch.g05 (geometry) --- (continued)

Type RM Length L Ch R = 1 ,1228    ,786.4,786.4,786.4
XS GIS Cut Line= 6
2311456.57716773471565.5632632242310970.33072075470502.737107134
2310649.61274829469380.3988006822308309.72466516466927.269298735
2307012.55970556465389.2456440442306791.33681634464697.032939112
#Sta/Elev= 30
       0   15.23   25.71    9.27 1050.48   11.04 1079.35    6.39 1773.54    7.91
 2097.72    2.38 2512.11    6.28 3127.93     -.4 3134.96   -2.86 3184.05    -.39
 3229.97    2.76 4404.58     5.8 4437.49    13.5 4468.06    8.21 4523.06    8.03
 4839.89    8.38 4871.64   13.69 4974.69   10.03 5293.35   13.19 5329.63    5.87
 5378.78    9.52 5801.51    1.27  5861.6    9.83 5891.65    1.97 6342.36     .08
 6657.18    3.66 6707.22    7.78  6771.6    1.27 6896.22    6.99 8464.87    14.5
#Mann= 3 ,0,0
       0     .15       0 3127.93     .05       0 3184.05     .15       0
#XS Ineff= 3 ,-1
       0    2780   5.498    3552  4466.1     4.8  4466.1 8464.87   13.52
Permanent Ineff=
       F       F       T
Bank Sta=3127.93,3184.05
XS Rating Curve= 0 ,0
Exp/Cntr(USF)=0,0
Exp/Cntr=0.5,0.3