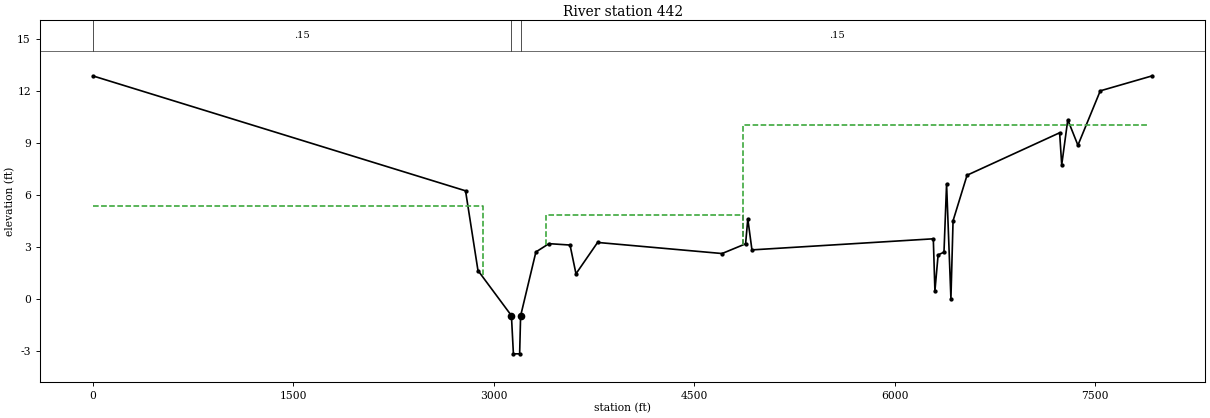
HEC-RAS study MollyBranch.prj: S-8-791 over Molly Branch Creek

--- MollyBranch.g05 (geometry) --- (continued)

Type RM Length L Ch R = 3 ,1077    ,,,
Node Name=Bridge
Bridge Culvert-0,0,0,0, 0
Deck Dist Width WeirC Skew NumUp NumDn MinLoCord MaxHiCord MaxSubmerge Is_Ogee
291.0775,20,2.6,0, 23, 23, 4.8, , 0.98, 0, 2,2,,
       0    1194    2358    2582    3100    3100    3232    3232    3923    4093
    4188    5067    5253    5453    5715    5972    6281    6657    7051    7423
    7961    8401    9000
    10.3    10.3   7.328   5.498     5.5     5.5     5.5     5.5     5.5     4.8
     4.8     9.2   8.764   7.344   7.334   7.923   6.777   7.658   7.654  10.902
  13.038  14.121    14.2
                                             4.5     4.5
                                                                                
                        
       0     636    1800    2024    2636    2768    3090    3090    3222    3222
    3365    3535    3630    4865    5157    5414    5723    6099    6493    6865
    7403    7843    8000
    10.3    10.3   7.328   5.498     5.5     5.5     5.5     5.5     5.5     5.5
     5.5     4.8     4.8      10   7.334   7.923   6.777   7.658   7.654  10.902
  13.038  14.121    14.2
                                                             4.5     4.5
                                                                                
                        
Pier Skew, UpSta & Num, DnSta & Num=  ,3113.2, 2 ,3103.2, 2 , 0 , 0 , 0 ,,
       1       1
   -2.86    4.42
       1       1
   -3.19    4.42
Pier Skew, UpSta & Num, DnSta & Num=  ,3126.4, 2 ,3116.4, 2 , 0 , 0 , 0 ,,
       1       1
   -2.86    4.42
       1       1
   -3.19    4.42
Pier Skew, UpSta & Num, DnSta & Num=  ,3139.6, 2 ,3129.6, 2 , 0 , 0 , 0 ,,
       1       1
   -2.86    4.42
       1       1
   -3.19    4.42
Pier Skew, UpSta & Num, DnSta & Num=  ,3152.8, 2 ,3142.8, 2 , 0 , 0 , 0 ,,
       1       1
   -2.86    4.42
       1       1
   -3.19    4.42
Pier Skew, UpSta & Num, DnSta & Num=  ,3166, 2 ,3156, 2 , 0 , 0 , 0 ,,
       1       1
   -2.86    4.42
       1       1
   -3.19    4.42
Pier Skew, UpSta & Num, DnSta & Num=  ,3179.2, 2 ,3169.2, 2 , 0 , 0 , 0 ,,
       1       1
   -2.86    4.42
       1       1
   -3.19    4.42
Pier Skew, UpSta & Num, DnSta & Num=  ,3192.4, 2 ,3182.4, 2 , 0 , 0 , 0 ,,
       1       1
   -2.86    4.42
       1       1
   -3.19    4.42
Pier Skew, UpSta & Num, DnSta & Num=  ,3205.6, 2 ,3195.6, 2 , 0 , 0 , 0 ,,
       1       1
   -2.86    4.42
       1       1
   -3.19    4.42
Pier Skew, UpSta & Num, DnSta & Num=  ,3218.8, 2 ,3208.8, 2 , 0 , 0 , 0 ,,
       1       1
   -2.86    4.42
       1       1
   -3.19    4.42
BR Coef=-1 ,-1 , 0 ,, 0 ,,,0.8,0,1.2,0,
WSPro=,,,, 1 ,,,, 0 ,,,, 0 ,,,,-1 ,-1 ,-1 , 0 , 0 , 0 , 0 , 0
BC Design=,, 0 ,, 0 ,,,,,,
BC Use User HTab Curves=0
BC User HTab FreeFlow(D)= 0

Type RM Length L Ch R = 1 ,442     ,,,
XS GIS Cut Line= 5
2311882.01498622 471444.096182532311913.89377766470772.615698168
2311533.81856662469672.628922891 2309148.2878615466529.141542911
2307922.45588126 464764.26409001
#Sta/Elev= 30
       0   12.85 2788.51    6.22 2881.55    1.623132.007   -.984 3146.79   -3.19
  3193.5   -3.193200.737  -1.002 3315.18    2.69 3412.88    3.17 3570.78    3.09
 3615.27    1.43  3777.1    3.24 4708.94     2.6 4885.14    3.16 4901.62     4.6
  4932.7    2.81 6290.46    3.45 6302.45     .44 6326.42    2.52 6370.36    2.68
 6389.78    6.62  6422.3    -.01 6438.28    4.49 6543.03    7.12 7236.16    9.57
 7251.77    7.72 7297.23   10.32 7373.13    8.85 7540.29   11.99 7931.03   12.86
#Mann= 3 ,0,0
       0     .15       03132.007     .05       03200.737     .15       0
#XS Ineff= 3 ,-1
       0    2920    5.33    3392  4865.4     4.8  4865.4  7894.8      10
Permanent Ineff=
       F       F       T
Bank Sta=3132.007,3200.737
XS Rating Curve= 0 ,0
Exp/Cntr(USF)=0,0
Exp/Cntr=0.5,0.3
LCMann Table=0

Chan Stop Cuts=-1
Use User Specified Reach Order=0
Composite Channel Slope=5

--- MollyBranch.g01 (geometry) ---

Geom Title=Natural
Program Version=6.60

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
River Reach=Molly Branch    ,Molly Branch

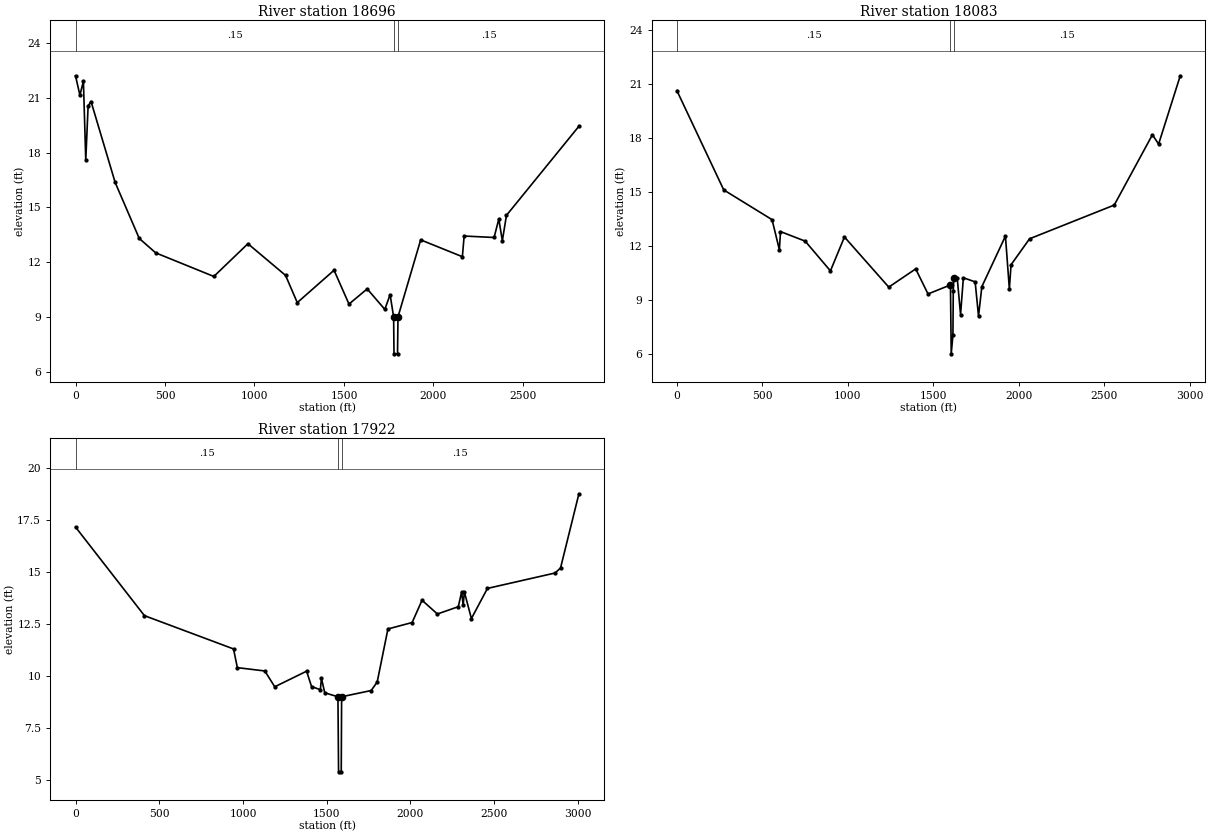
Type RM Length L Ch R = 1 ,18696   ,612.4,612.4,612.4
XS GIS Cut Line= 3
2300024.55007655475467.9829793192300108.29334628472922.503459534
2299989.45341796472684.645367073
#Sta/Elev= 30
       0    22.2    24.4   21.14    44.1    21.9    57.2   17.59    70.4   20.56
    86.8   20.79   221.4   16.37     356   13.31   447.9   12.52   772.9   11.23
   963.3   13.02  1173.5   11.29  1239.1     9.8  1444.6   11.57    1528    9.72
  1629.8   10.55  1728.3    9.43  1757.8   10.24 1777.53    9.01 1779.49       7
 1799.22       7 1801.83    9.02  1928.6   13.23  2161.6   12.31  2171.5   13.44
  2338.9   13.36  2365.2   14.37  2384.9   13.18  2407.9   14.57 2812.75   19.44
#Mann= 3 ,0,0
       0     .15       0 1777.53     .05       0 1801.83     .15       0
Bank Sta=1777.53,1801.83
XS Rating Curve= 0 ,0
Exp/Cntr(USF)=0,0
Exp/Cntr=0.3,0.1

Type RM Length L Ch R = 1 ,18083   ,161.3,161.3,161.3
XS GIS Cut Line= 4
2300186.99074373475628.5958880842300222.43609811475109.814625074
2300214.47431246473089.2015948242300225.02926711472685.421104403
#Sta/Elev= 30
       0   20.63  274.22   15.12  556.98   13.47  599.64    11.8   606.2   12.81
  750.58   12.28  898.24   10.63  980.27   12.51 1239.49    9.73 1396.99   10.74
 1469.18    9.351600.391   9.851 1604.85    6.03 1614.85    7.07 1616.84    9.54
1620.091  10.211 1639.81   10.25 1659.49    8.21  1675.9   10.25 1744.81   10.02
  1764.5    8.13 1784.18    9.76    1922   12.56 1944.97    9.63 1954.81   10.97
 2063.09   12.41 2558.43   14.28 2781.77   18.18 2817.88   17.66 2944.54   21.45
#Mann= 3 ,0,0
       0     .15       01600.391     .05       01620.091     .15       0
Bank Sta=1600.391,1620.091
XS Rating Curve= 0 ,0
Exp/Cntr(USF)=0,0
Exp/Cntr=0.3,0.1

Type RM Length L Ch R = 1 ,17922   ,1100.1,1100.1,1100.1
XS GIS Cut Line= 6
2300285.47475126475653.991477348  2300324.165683475107.507806008
2300334.00372776474708.9008433122300367.36918183473321.682391052
  2300465.122102473091.7592232922300474.04149011472669.476386347
#Sta/Elev= 30
       0   17.18  411.57   12.92   943.6   11.32  966.57   10.42 1130.68   10.26
 1189.76     9.5 1380.13   10.25 1409.67    9.51 1462.18    9.36 1468.75    9.91
 1488.44    9.21 1567.27    9.02    1571    5.41    1587    5.41 1589.22    9.02
 1765.93    9.32 1801.76    9.73 1865.82   12.28 2010.44   12.59 2069.39   13.66
  2161.3      13 2286.02   13.35 2305.71   14.05 2315.56   13.43 2322.12   14.07
  2364.3   12.78 2460.14   14.23 2863.83   14.97 2896.65   15.21 3006.42   18.78
#Mann= 3 ,0,0
       0     .15       0 1567.27     .05       0 1589.22     .15       0
Bank Sta=1567.27,1589.22
XS Rating Curve= 0 ,0
Exp/Cntr(USF)=0,0
Exp/Cntr=0.3,0.1

--- MollyBranch.g02 (geometry) ---

Geom Title=Duplicate Effective - HEC-2
Program Version=6.60
BEGIN GEOM DESCRIPTION:
All elevations from HEC-2 model were converted from NGVD29 to NAVD88 by subtracting 0.98 ft
END GEOM DESCRIPTION:

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
River Reach=RIVER-1         ,Reach-1
Reach XY= 2
             0.5            0.95             0.5            0.05

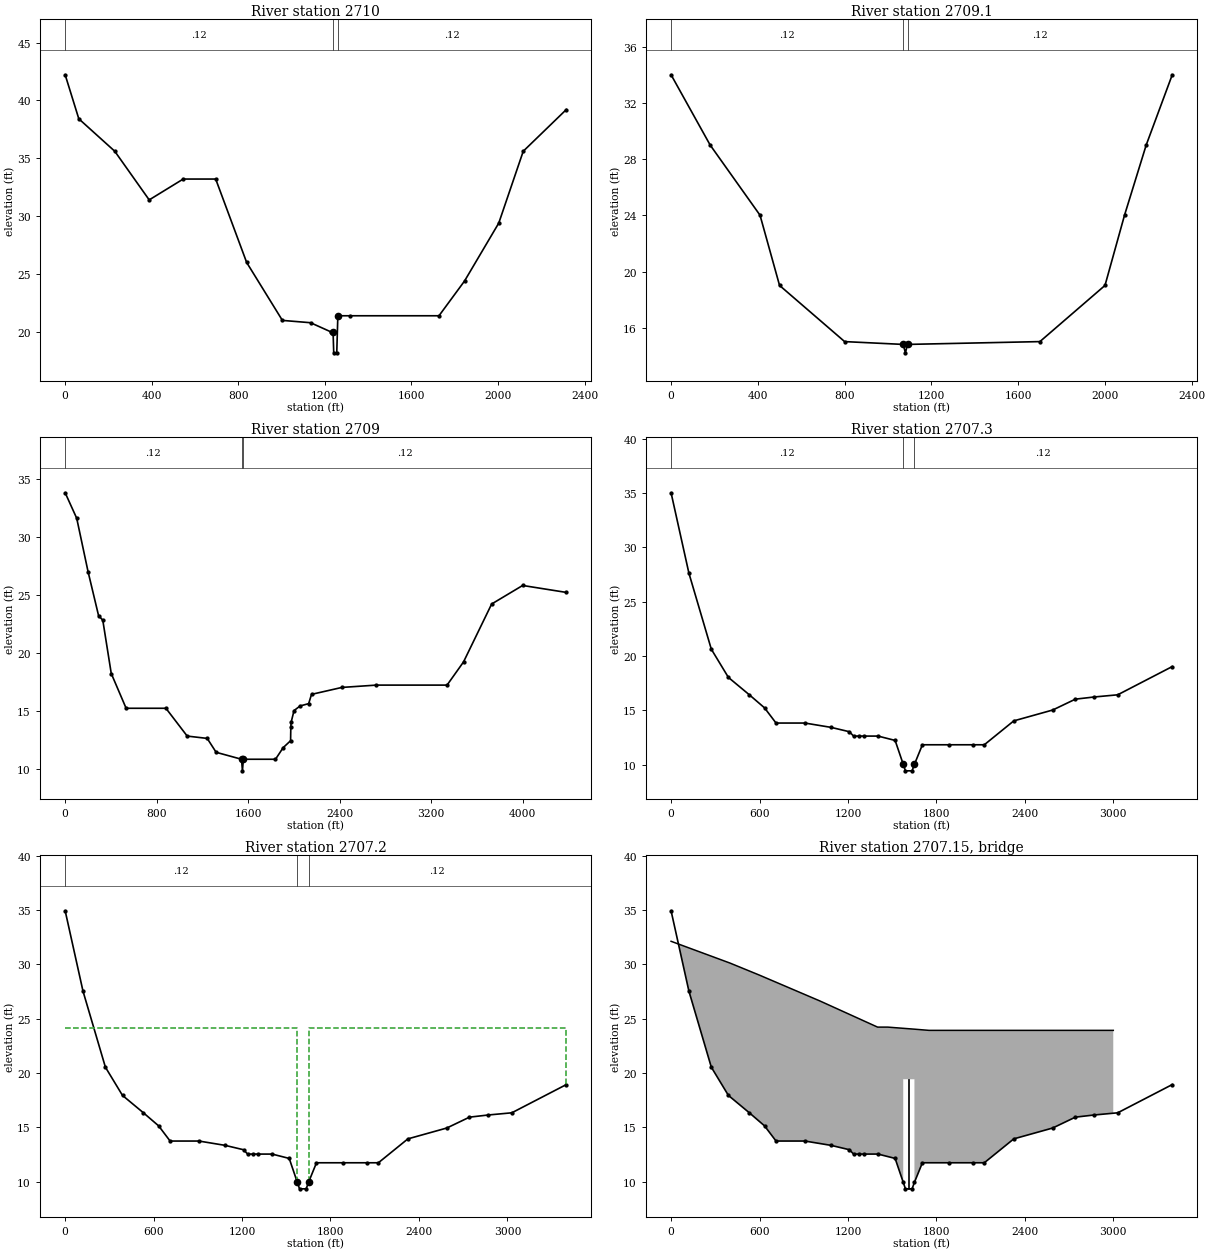
Type RM Length L Ch R = 1 ,2710    ,1240,1870,2140
#Sta/Elev= 20
       1   42.22      64   38.42     230   35.62     389   31.42     546   33.22
     696   33.22     839   26.02    1004   21.02    1134   20.82    1229   20.02
    1238   20.02    1241   18.22    1255   18.22    1260   21.42    1316   21.42
    1727   21.42    1845   24.42    2003   29.42    2116   35.62    2315   39.22
#Mann= 3 ,0,0
       1     .12       0    1238     .06       0    1260     .12       0
Bank Sta=1238,1260
XS Rating Curve= 0 ,0
Sediment Elevation=-0.98
Exp/Cntr=0.5,0.3

Type RM Length L Ch R = 1 ,2709.1  ,1550,1500,780
#Sta/Elev= 13
       0   34.02     180   29.02     410   24.02     500   19.02     800   15.02
    1070   14.82    1080   14.22    1090   14.82    1700   15.02    2000   19.02
    2090   24.02    2190   29.02    2310   34.02
#Mann= 3 ,0,0
       0     .12       0    1070     .06       0    1090     .12       0
Bank Sta=1070,1090
XS Rating Curve= 0 ,0
Sediment Elevation=-0.98
Exp/Cntr=0.5,0.3

Type RM Length L Ch R = 1 ,2709    ,780,770,900
#Sta/Elev= 30
       0   33.82     101   31.62     200   27.02     292   23.22     329   22.82
     403   18.22     533   15.22     881   15.22    1067   12.82    1242   12.62
    1320   11.42    1542   10.82    1550    9.82    1558   10.82    1839   10.82
    1906   11.82    1971   12.42    1973   13.62    1976   14.02    2001   15.02
    2054   15.42    2129   15.62    2154   16.42    2420   17.02    2721   17.22
    3339   17.22    3483   19.22    3729   24.22    4000   25.82    4382   25.22
#Mann= 3 ,0,0
       0     .12       0    1542     .06       0    1558     .12       0
Bank Sta=1542,1558
XS Rating Curve= 0 ,0
Sediment Elevation=-0.98
Exp/Cntr=0.5,0.3

Type RM Length L Ch R = 1 ,2707.3  ,120,120,120
#Sta/Elev= 29
       0   35.02     121   27.62     273   20.62     389   18.02     531   16.42
     634   15.22     712   13.82     908   13.82    1086   13.42    1210   13.02
    1238   12.62    1272   12.62    1308   12.62    1404   12.62    1520   12.22
    1575   10.02    1590    9.42    1635    9.42    1651   10.02    1705   11.82
    1885   11.82    2051   11.82    2125   11.82    2325   14.02    2589   15.02
    2743   16.02    2871   16.22    3030   16.42    3400   19.02
#Mann= 3 ,0,0
       0     .12       0    1575     .06       0    1651     .12       0
Bank Sta=1575,1651
XS Rating Curve= 0 ,0
Sediment Elevation=-0.98
Exp/Cntr=0.5,0.3

Type RM Length L Ch R = 1 ,2707.2  ,20,20,20
BEGIN DESCRIPTION:
This is a REPEATED section.
END DESCRIPTION:
#Sta/Elev= 29
       0   34.93     121   27.53     273   20.53     389   17.93     531   16.33
     634   15.13     712   13.73     908   13.73    1086   13.33    1210   12.93
    1238   12.53    1272   12.53    1308   12.53    1404   12.53    1520   12.13
    1575    9.93    1590    9.33    1635    9.33    1651    9.93    1705   11.73
    1885   11.73    2051   11.73    2125   11.73    2325   13.93    2589   14.93
    2743   15.93    2871   16.13    3030   16.33    3400   18.93
#Mann= 3 ,0,0
       0     .12       0    1575     .06       0    1651     .12       0
#XS Ineff= 2 , 0
            1575   24.12    1651           24.12
Permanent Ineff=
       F       F
Bank Sta=1575,1651
XS Rating Curve= 0 ,0
Sediment Elevation=-0.98
Exp/Cntr=0.5,0.3

Type RM Length L Ch R = 3 ,2707.15 ,,,
BEGIN DESCRIPTION:
Bridge #4
END DESCRIPTION:
Bridge Culvert--1,0,-1,-1, 0
Deck Dist Width WeirC Skew NumUp NumDn MinLoCord MaxHiCord MaxSubmerge Is_Ogee
0.001,19.99,2.5,0, 13, 13, 24.12, , 0.98, 0, 0,0,,
       0     399     597    1011    1401    1470    1575    1575    1651    1651
    1750    2245    3000
   32.12   30.12   29.02   26.62   24.22   24.22   24.11   24.11   24.03   24.03
   23.92   23.92   23.92
    9.33    9.33    9.33    9.33    9.33    9.33    9.33   19.42   19.42    9.33
    9.33    9.33    9.33
       0     399     597    1011    1401    1470    1575    1575    1651    1651
    1750    2245    3000
   32.12   30.12   29.02   26.62   24.22   24.22   24.11   24.11   24.03   24.03
   23.92   23.92   23.92
    9.33    9.33    9.33    9.33    9.33    9.33    9.33   19.42   19.42    9.33
    9.33    9.33    9.33
Pier Skew, UpSta & Num, DnSta & Num=  ,1613, 2 ,1613, 2 , 0 , 0 , 0 ,,
       8       8
    9.33   19.42
       8       8
    9.33   19.42
BR Coef= 0 , 0 ,-1 ,1.25, 0 ,,,0.8006408,0,,2,19.42
WSPro=,,,, 1 ,,,, 0 ,,,, 0 ,,,,-1 ,-1 ,-1 , 0 , 0 , 0 , 0 , 0
BC Design=,, 0 ,, 0 ,,,,,,
BC Use User HTab Curves=0
BC User HTab FreeFlow(D)= 0

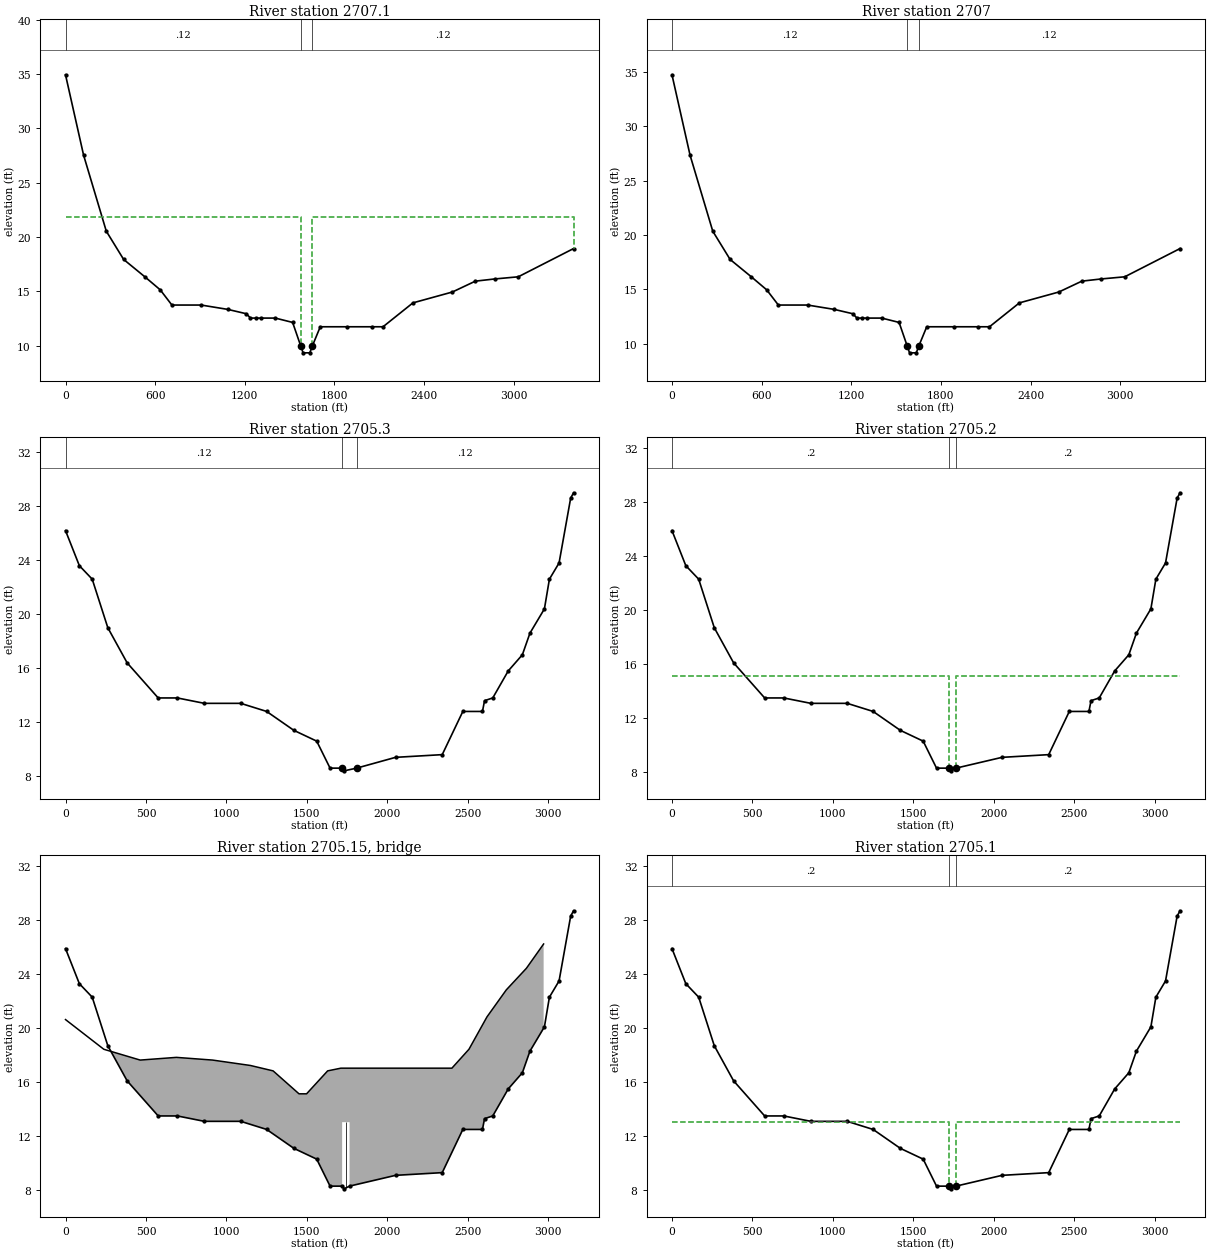
Type RM Length L Ch R = 1 ,2707.1  ,250,250,250
BEGIN DESCRIPTION:
This is a REPEATED section.
END DESCRIPTION:
#Sta/Elev= 29
       0   34.93     121   27.53     273   20.53     389   17.93     531   16.33
     634   15.13     712   13.73     908   13.73    1086   13.33    1210   12.93
    1238   12.53    1272   12.53    1308   12.53    1404   12.53    1520   12.13
    1575    9.93    1590    9.33    1635    9.33    1651    9.93    1705   11.73
    1885   11.73    2051   11.73    2125   11.73    2325   13.93    2589   14.93
    2743   15.93    2871   16.13    3030   16.33    3400   18.93
#Mann= 3 ,0,0
       0     .12       0    1575     .06       0    1651     .12       0
#XS Ineff= 2 , 0
            1575   21.82    1651           21.82
Permanent Ineff=
       F       F
Bank Sta=1575,1651
XS Rating Curve= 0 ,0
Sediment Elevation=-0.98
Exp/Cntr=0.5,0.3

Type RM Length L Ch R = 1 ,2707    ,780,1120,1050
#Sta/Elev= 29
       0   34.75     121   27.35     273   20.35     389   17.75     531   16.15
     634   14.95     712   13.55     908   13.55    1086   13.15    1210   12.75
    1238   12.35    1272   12.35    1308   12.35    1404   12.35    1520   11.95
    1575    9.75    1590    9.15    1635    9.15    1651    9.75    1705   11.55
    1885   11.55    2051   11.55    2125   11.55    2325   13.75    2589   14.75
    2743   15.75    2871   15.95    3030   16.15    3400   18.75
#Mann= 3 ,0,0
       0     .12       0    1575     .06       0    1651     .12       0
Bank Sta=1575,1651
XS Rating Curve= 0 ,0
Sediment Elevation=-0.98
Exp/Cntr=0.5,0.3

Type RM Length L Ch R = 1 ,2705.3  ,100,100,100
#Sta/Elev= 30
       0   26.16      86   23.56     166   22.56     263   18.96     383   16.36
     576   13.76     695   13.76     863   13.36    1089   13.36    1250   12.76
    1419   11.36    1561   10.56    1644    8.56    1719    8.56    1731    8.36
    1809    8.56    2051    9.36    2341    9.56    2469   12.76    2591   12.76
    2604   13.56    2655   13.76    2751   15.76    2839   16.96    2886   18.56
    2976   20.36    3007   22.56    3067   23.76    3139   28.56    3157   28.96
#Mann= 3 ,0,0
       0     .12       0    1719     .06       0    1809     .12       0
Bank Sta=1719,1809
XS Rating Curve= 0 ,0
Sediment Elevation=-0.98
Exp/Cntr=0.5,0.3

Type RM Length L Ch R = 1 ,2705.2  ,42,42,42
BEGIN DESCRIPTION:
This is a REPEATED section.
END DESCRIPTION:
#Sta/Elev= 30
       0   25.88      86   23.28     166   22.28     263   18.68     383   16.08
     576   13.48     695   13.48     863   13.08    1089   13.08    1250   12.48
    1419   11.08    1561   10.28    1644    8.28    1719    8.28    1731    8.08
    1765    8.28    2051    9.08    2341    9.28    2469   12.48    2591   12.48
    2604   13.28    2655   13.48    2751   15.48    2839   16.68    2886   18.28
    2976   20.08    3007   22.28    3067   23.48    3139   28.28    3157   28.68
#Mann= 3 ,0,0
       0      .2       0    1719     .06       0    1765      .2       0
#XS Ineff= 2 , 0
            1719   15.12    1765           15.12
Permanent Ineff=
       F       F
Bank Sta=1719,1765
XS Rating Curve= 0 ,0
Sediment Elevation=-0.98
Exp/Cntr=0.5,0.3

Type RM Length L Ch R = 3 ,2705.15 ,,,
BEGIN DESCRIPTION:
Bridge #3
END DESCRIPTION:
Bridge Culvert--1,0,-1,-1, 0
Deck Dist Width WeirC Skew NumUp NumDn MinLoCord MaxHiCord MaxSubmerge Is_Ogee
0.001,41.99,2.5,0, 24, 24, 15.12, , 0.98, 0, 0,0,,
       0     238     464     689     914    1149    1290    1451    1498    1629
    1711    1719    1719    1765    1765    1851    1999    2278    2401    2507
    2619    2739    2864    2971
   20.62   18.42   17.62   17.82   17.62   17.22   16.82   15.12   15.12   16.82
   17.02   17.02   17.02   17.02   17.02   17.02   17.02   17.02   17.02   18.42
   20.82   22.82   24.42   26.22
    8.08    8.08    8.08    8.08    8.08    8.08    8.08    8.08    8.08    8.08
    8.08    8.08   13.02   13.02    8.08    8.08    8.08    8.08    8.08    8.08
    8.08    8.08    8.08    8.08
       0     238     464     689     914    1149    1290    1451    1498    1629
    1711    1719    1719    1765    1765    1851    1999    2278    2401    2507
    2619    2739    2864    2971
   20.62   18.42   17.62   17.82   17.62   17.22   16.82   15.12   15.12   16.82
   17.02   17.02   17.02   17.02   17.02   17.02   17.02   17.02   17.02   18.42
   20.82   22.82   24.42   26.22
    8.08    8.08    8.08    8.08    8.08    8.08    8.08    8.08    8.08    8.08
    8.08    8.08   13.02   13.02    8.08    8.08    8.08    8.08    8.08    8.08
    8.08    8.08    8.08    8.08
Pier Skew, UpSta & Num, DnSta & Num=  ,1742, 2 ,1742, 2 , 0 , 0 , 0 ,,
       1       1
    8.08   13.02
       1       1
    8.08   13.02
BR Coef= 0 , 0 ,-1 ,0.95, 0 ,,,0.8006408,0,,2,13.02
WSPro=,,,, 1 ,,,, 0 ,,,, 0 ,,,,-1 ,-1 ,-1 , 0 , 0 , 0 , 0 , 0
BC Design=,, 0 ,, 0 ,,,,,,
BC Use User HTab Curves=0
BC User HTab FreeFlow(D)= 0

Type RM Length L Ch R = 1 ,2705.1  ,200,200,200
#Sta/Elev= 30
       0   25.88      86   23.28     166   22.28     263   18.68     383   16.08
     576   13.48     695   13.48     863   13.08    1089   13.08    1250   12.48
    1419   11.08    1561   10.28    1644    8.28    1719    8.28    1731    8.08
    1765    8.28    2051    9.08    2341    9.28    2469   12.48    2591   12.48
    2604   13.28    2655   13.48    2751   15.48    2839   16.68    2886   18.28
    2976   20.08    3007   22.28    3067   23.48    3139   28.28    3157   28.68
#Mann= 3 ,0,0
       0      .2       0    1719     .06       0    1765      .2       0
#XS Ineff= 2 , 0
            1719   13.02    1765           13.02
Permanent Ineff=
       F       F
Bank Sta=1719,1765
XS Rating Curve= 0 ,0
Sediment Elevation=-0.98
Exp/Cntr=0.5,0.3

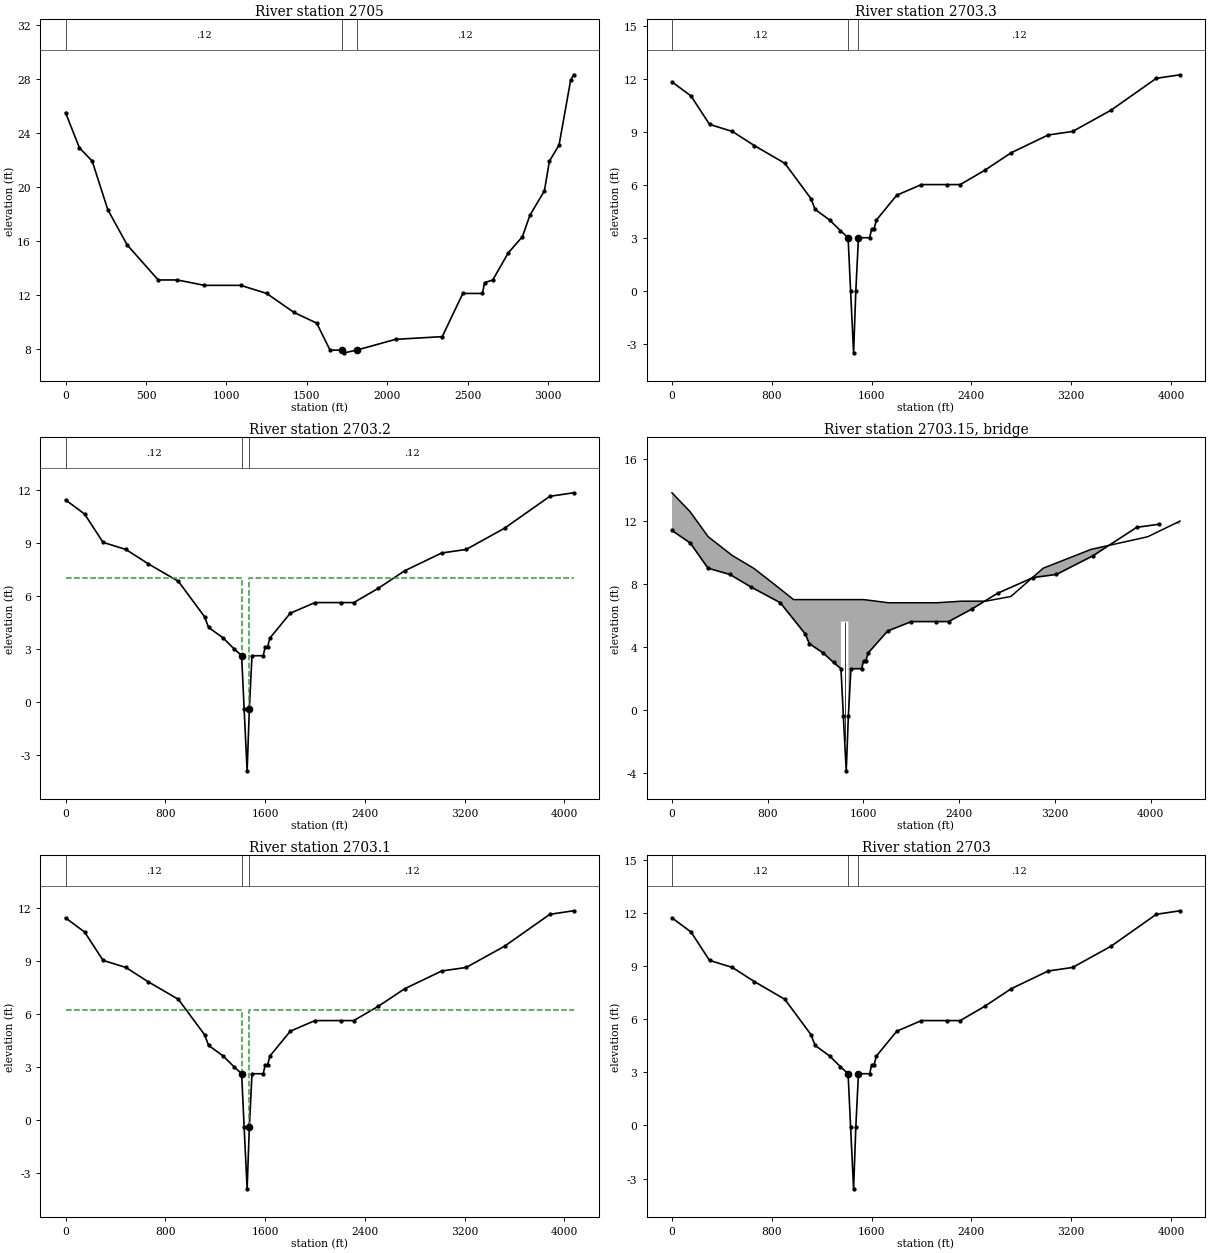
Type RM Length L Ch R = 1 ,2705    ,6600,6370,5760
#Sta/Elev= 30
       0   25.52      86   22.92     166   21.92     263   18.32     383   15.72
     576   13.12     695   13.12     863   12.72    1089   12.72    1250   12.12
    1419   10.72    1561    9.92    1644    7.92    1719    7.92    1731    7.72
    1809    7.92    2051    8.72    2341    8.92    2469   12.12    2591   12.12
    2604   12.92    2655   13.12    2751   15.12    2839   16.32    2886   17.92
    2976   19.72    3007   21.92    3067   23.12    3139   27.92    3157   28.32
#Mann= 3 ,0,0
       0     .12       0    1719     .06       0    1809     .12       0
Bank Sta=1719,1809
XS Rating Curve= 0 ,0
Sediment Elevation=-0.98
Exp/Cntr=0.5,0.3

Type RM Length L Ch R = 1 ,2703.3  ,100,100,100
#Sta/Elev= 30
       0   11.82     153   11.02     301    9.42     484    9.02     661    8.22
     905    7.22    1115    5.22    1147    4.62    1264    4.02    1350    3.42
    1412    3.02    1432     .02    1456   -3.48    1474     .02    1495    3.02
    1585    3.02    1601    3.52    1620    3.52    1639    4.02    1802    5.42
    2000    6.02    2205    6.02    2311    6.02    2506    6.82    2720    7.82
    3016    8.82    3212    9.02    3520   10.22    3883   12.02    4073   12.22
#Mann= 3 ,0,0
       0     .12       0    1412    .045       0    1495     .12       0
Bank Sta=1412,1495
XS Rating Curve= 0 ,0
Sediment Elevation=-0.98
Exp/Cntr=0.5,0.3

Type RM Length L Ch R = 1 ,2703.2  ,14,14,14
BEGIN DESCRIPTION:
This is a REPEATED section.
END DESCRIPTION:
#Sta/Elev= 30
       0   11.42     153   10.62     301    9.02     484    8.62     661    7.82
     905    6.82    1115    4.82    1147    4.22    1264    3.62    1350    3.02
    1412    2.62    1432    -.38    1456   -3.88    1474    -.38    1495    2.62
    1585    2.62    1601    3.12    1620    3.12    1639    3.62    1802    5.02
    2000    5.62    2205    5.62    2311    5.62    2506    6.42    2720    7.42
    3016    8.42    3212    8.62    3520    9.82    3883   11.62    4073   11.82
#Mann= 3 ,0,0
       0     .12       0    1412    .045       0    1474     .12       0
#XS Ineff= 2 , 0
            1412    7.02    1474            7.02
Permanent Ineff=
       F       F
Bank Sta=1412,1474
XS Rating Curve= 0 ,0
Sediment Elevation=-0.98
Exp/Cntr=0.5,0.3

Type RM Length L Ch R = 3 ,2703.15 ,,,
BEGIN DESCRIPTION:
Bridge #2
END DESCRIPTION:
Bridge Culvert--1,0,-1,-1, 0
Deck Dist Width WeirC Skew NumUp NumDn MinLoCord MaxHiCord MaxSubmerge Is_Ogee
0.001,13.99,2.5,0, 24, 24, 6.98, , 0.98, 0, 0,0,,
       0     151     303     505     682     851    1016    1253    1412    1412
    1474    1474    1510    1604    1807    2003    2211    2422    2621    2832
    3102    3503    3975    4245
   13.82   12.62   11.02    9.82    9.02    8.02    7.02    7.02    7.02    7.02
    7.02    7.02    7.02    7.02    6.82    6.82    6.82    6.92    6.92    7.22
    9.02   10.22   11.02   12.02
   -3.88   -3.88   -3.88   -3.88   -3.88   -3.88   -3.88   -3.88   -3.88    5.62
    5.62   -3.88   -3.88   -3.88   -3.88   -3.88   -3.88   -3.88   -3.88   -3.88
   -3.88   -3.88   -3.88   -3.88
       0     151     303     505     682     851    1016    1253    1412    1412
    1474    1474    1510    1604    1807    2003    2211    2422    2621    2832
    3102    3503    3975    4245
   13.82   12.62   11.02    9.82    9.02    8.02    7.02    7.02    7.02    7.02
    7.02    7.02    7.02    7.02    6.82    6.82    6.82    6.92    6.92    7.22
    9.02   10.22   11.02   12.02
   -3.88   -3.88   -3.88   -3.88   -3.88   -3.88   -3.88   -3.88   -3.88    5.62
    5.62   -3.88   -3.88   -3.88   -3.88   -3.88   -3.88   -3.88   -3.88   -3.88
   -3.88   -3.88   -3.88   -3.88
Pier Skew, UpSta & Num, DnSta & Num=  ,1443, 2 ,1443, 2 , 0 , 0 , 0 ,,
       2       2
   -3.88    5.62
       2       2
   -3.88    5.62
BR Coef= 0 , 0 ,-1 ,0.95, 0 ,,,0.8006408,0,,2,5.62
WSPro=,,,, 1 ,,,, 0 ,,,, 0 ,,,,-1 ,-1 ,-1 , 0 , 0 , 0 , 0 , 0
BC Design=,, 0 ,, 0 ,,,,,,
BC Use User HTab Curves=0
BC User HTab FreeFlow(D)= 0

Type RM Length L Ch R = 1 ,2703.1  ,200,200,200
#Sta/Elev= 30
       0   11.42     153   10.62     301    9.02     484    8.62     661    7.82
     905    6.82    1115    4.82    1147    4.22    1264    3.62    1350    3.02
    1412    2.62    1432    -.38    1456   -3.88    1474    -.38    1495    2.62
    1585    2.62    1601    3.12    1620    3.12    1639    3.62    1802    5.02
    2000    5.62    2205    5.62    2311    5.62    2506    6.42    2720    7.42
    3016    8.42    3212    8.62    3520    9.82    3883   11.62    4073   11.82
#Mann= 3 ,0,0
       0     .12       0    1412    .045       0    1474     .12       0
#XS Ineff= 2 , 0
            1412    6.22    1474            6.22
Permanent Ineff=
       F       F
Bank Sta=1412,1474
XS Rating Curve= 0 ,0
Sediment Elevation=-0.98
Exp/Cntr=0.5,0.3

Type RM Length L Ch R = 1 ,2703    ,4970,6160,4770
#Sta/Elev= 30
       0   11.72     153   10.92     301    9.32     484    8.92     661    8.12
     905    7.12    1115    5.12    1147    4.52    1264    3.92    1350    3.32
    1412    2.92    1432    -.08    1456   -3.58    1474    -.08    1495    2.92
    1585    2.92    1601    3.42    1620    3.42    1639    3.92    1802    5.32
    2000    5.92    2205    5.92    2311    5.92    2506    6.72    2720    7.72
    3016    8.72    3212    8.92    3520   10.12    3883   11.92    4073   12.12
#Mann= 3 ,0,0
       0     .12       0    1412    .045       0    1495     .12       0
Bank Sta=1412,1495
XS Rating Curve= 0 ,0
Sediment Elevation=-0.98
Exp/Cntr=0.5,0.3

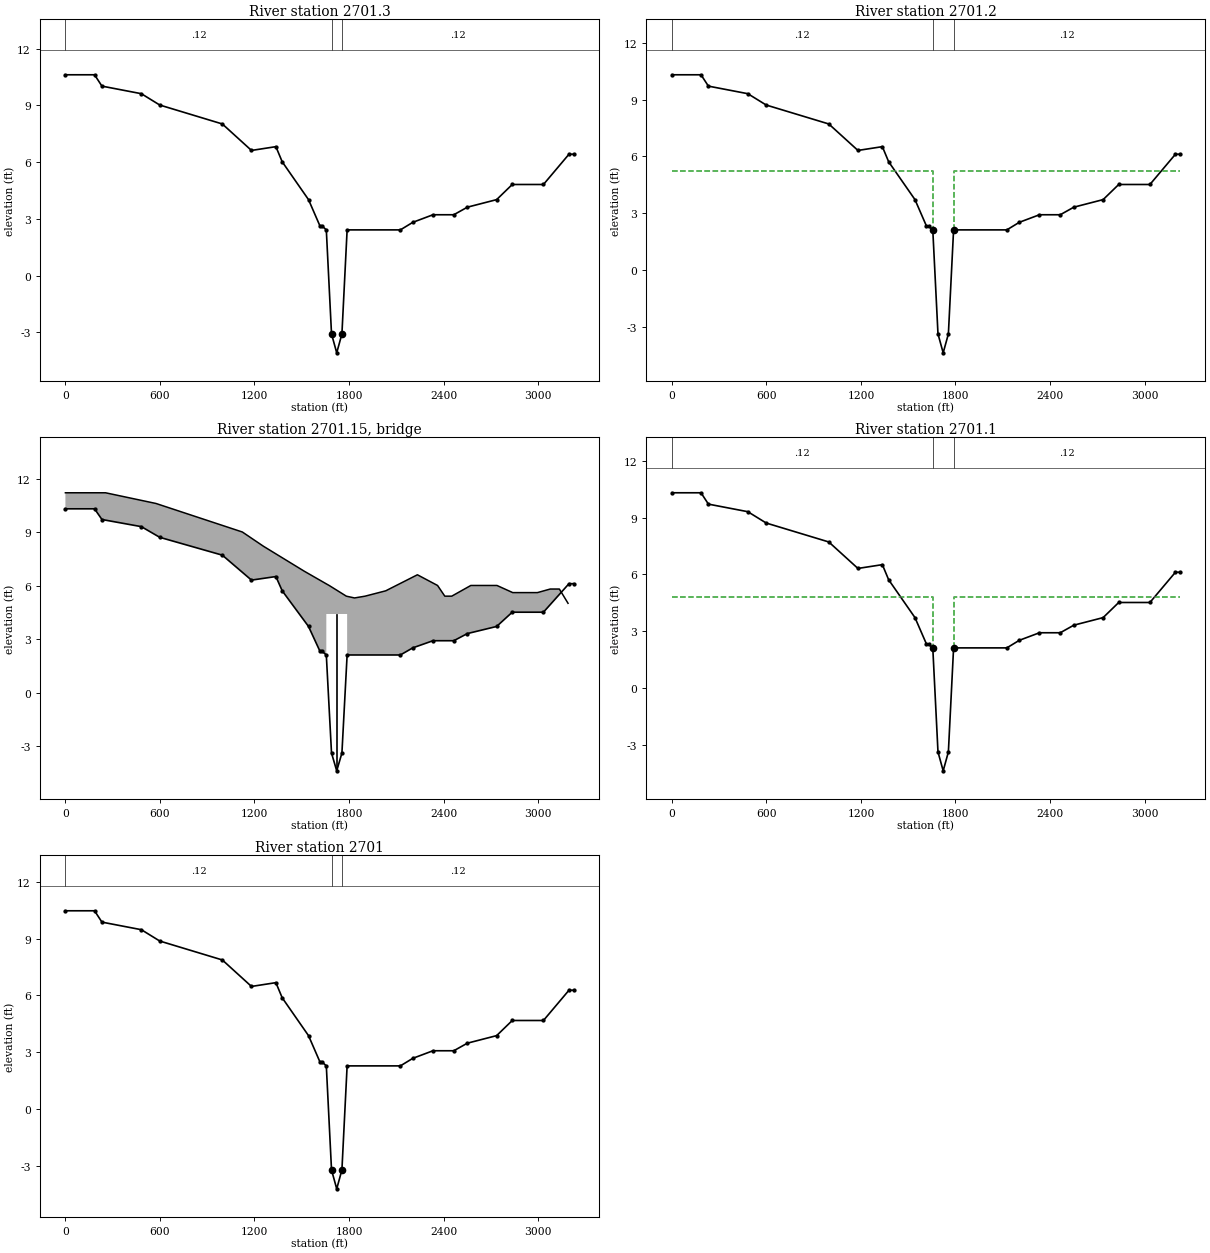
Type RM Length L Ch R = 1 ,2701.3  ,110,110,110
#Sta/Elev= 27
       0   10.62     185   10.62     232   10.02     482    9.62     599    9.02
     996    8.02    1181    6.62    1336    6.82    1376    6.02    1543    4.02
    1616    2.62    1630    2.62    1656    2.42    1689   -3.08    1722   -4.08
    1755   -3.08    1788    2.42    2126    2.42    2205    2.82    2333    3.22
    2465    3.22    2551    3.62    2737    4.02    2836    4.82    3034    4.82
    3196    6.42    3225    6.42
#Mann= 3 ,0,0
       0     .12       0    1689    .045       0    1755     .12       0
Bank Sta=1689,1755
XS Rating Curve= 0 ,0
Sediment Elevation=-0.98
Exp/Cntr=0.5,0.3

Type RM Length L Ch R = 1 ,2701.2  ,20,20,20
BEGIN DESCRIPTION:
This is a REPEATED section.
END DESCRIPTION:
#Sta/Elev= 27
       0   10.32     185   10.32     232    9.72     482    9.32     599    8.72
     996    7.72    1181    6.32    1336    6.52    1376    5.72    1543    3.72
    1616    2.32    1630    2.32    1656    2.12    1689   -3.38    1722   -4.38
    1755   -3.38    1788    2.12    2126    2.12    2205    2.52    2333    2.92
    2465    2.92    2551    3.32    2737    3.72    2836    4.52    3034    4.52
    3196    6.12    3225    6.12
#Mann= 3 ,0,0
       0     .12       0    1656    .045       0    1788     .12       0
#XS Ineff= 2 , 0
            1656    5.22    1788            5.22
Permanent Ineff=
       F       F
Bank Sta=1656,1788
XS Rating Curve= 0 ,0
Sediment Elevation=-0.98
Exp/Cntr=0.5,0.3

Type RM Length L Ch R = 3 ,2701.15 ,,,
BEGIN DESCRIPTION:
Bridge #1
END DESCRIPTION:
Bridge Culvert--1,0,-1,-1, 0
Deck Dist Width WeirC Skew NumUp NumDn MinLoCord MaxHiCord MaxSubmerge Is_Ogee
0.001,19.99,2.5,0, 27, 27, 5.22, , 0.98, 0, 0,0,,
       0     255     575     849    1123    1257    1516    1656    1656    1674
    1783    1788    1788    1835    1902    2033    2234    2362    2408    2452
    2573    2739    2839    2996    3077    3135    3190
   11.22   11.22   10.62    9.82    9.02    8.22    6.82    6.11    6.11    6.02
    5.42    5.41    5.41    5.32    5.42    5.72    6.62    6.02    5.42    5.42
    6.02    6.02    5.62    5.62    5.82    5.82    5.02
   -4.38   -4.38   -4.38   -4.38   -4.38   -4.38   -4.38   -4.38    4.42    4.42
    4.42    4.42   -4.38   -4.38   -4.38   -4.38   -4.38   -4.38   -4.38   -4.38
   -4.38   -4.38   -4.38   -4.38   -4.38   -4.38   -4.38
       0     255     575     849    1123    1257    1516    1656    1656    1674
    1783    1788    1788    1835    1902    2033    2234    2362    2408    2452
    2573    2739    2839    2996    3077    3135    3190
   11.22   11.22   10.62    9.82    9.02    8.22    6.82    6.11    6.11    6.02
    5.42    5.41    5.41    5.32    5.42    5.72    6.62    6.02    5.42    5.42
    6.02    6.02    5.62    5.62    5.82    5.82    5.02
   -4.38   -4.38   -4.38   -4.38   -4.38   -4.38   -4.38   -4.38    4.42    4.42
    4.42    4.42   -4.38   -4.38   -4.38   -4.38   -4.38   -4.38   -4.38   -4.38
   -4.38   -4.38   -4.38   -4.38   -4.38   -4.38   -4.38
Pier Skew, UpSta & Num, DnSta & Num=  ,1722, 2 ,1722, 2 , 0 , 0 , 0 ,,
       9       9
   -4.38    4.42
       9       9
   -4.38    4.42
BR Coef= 0 , 0 ,-1 ,0.95, 0 ,,,0.8006408,0,,2,4.42
WSPro=,,,, 1 ,,,, 0 ,,,, 0 ,,,,-1 ,-1 ,-1 , 0 , 0 , 0 , 0 , 0
BC Design=,, 0 ,, 0 ,,,,,,
BC Use User HTab Curves=0
BC User HTab FreeFlow(D)= 0

Type RM Length L Ch R = 1 ,2701.1  ,400,400,400
#Sta/Elev= 27
       0   10.32     185   10.32     232    9.72     482    9.32     599    8.72
     996    7.72    1181    6.32    1336    6.52    1376    5.72    1543    3.72
    1616    2.32    1630    2.32    1656    2.12    1689   -3.38    1722   -4.38
    1755   -3.38    1788    2.12    2126    2.12    2205    2.52    2333    2.92
    2465    2.92    2551    3.32    2737    3.72    2836    4.52    3034    4.52
    3196    6.12    3225    6.12
#Mann= 3 ,0,0
       0     .12       0    1656    .045       0    1788     .12       0
#XS Ineff= 2 , 0
            1656    4.82    1788            4.82
Permanent Ineff=
       F       F
Bank Sta=1656,1788
XS Rating Curve= 0 ,0
Sediment Elevation=-0.98
Exp/Cntr=0.5,0.3

Type RM Length L Ch R = 1 ,2701    ,0,0,0
#Sta/Elev= 27
       0   10.47     185   10.47     232    9.87     482    9.47     599    8.87
     996    7.87    1181    6.47    1336    6.67    1376    5.87    1543    3.87
    1616    2.47    1630    2.47    1656    2.27    1689   -3.23    1722   -4.23
    1755   -3.23    1788    2.27    2126    2.27    2205    2.67    2333    3.07
    2465    3.07    2551    3.47    2737    3.87    2836    4.67    3034    4.67
    3196    6.27    3225    6.27
#Mann= 3 ,0,0
       0     .12       0    1689    .045       0    1755     .12       0
Bank Sta=1689,1755
XS Rating Curve= 0 ,0
Exp/Cntr=0.5,0.3
LCMann Table=0

--- MollyBranch.g03 (geometry) ---

Geom Title=Existing
Program Version=6.60

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
River Reach=Molly Branch    ,Molly Branch

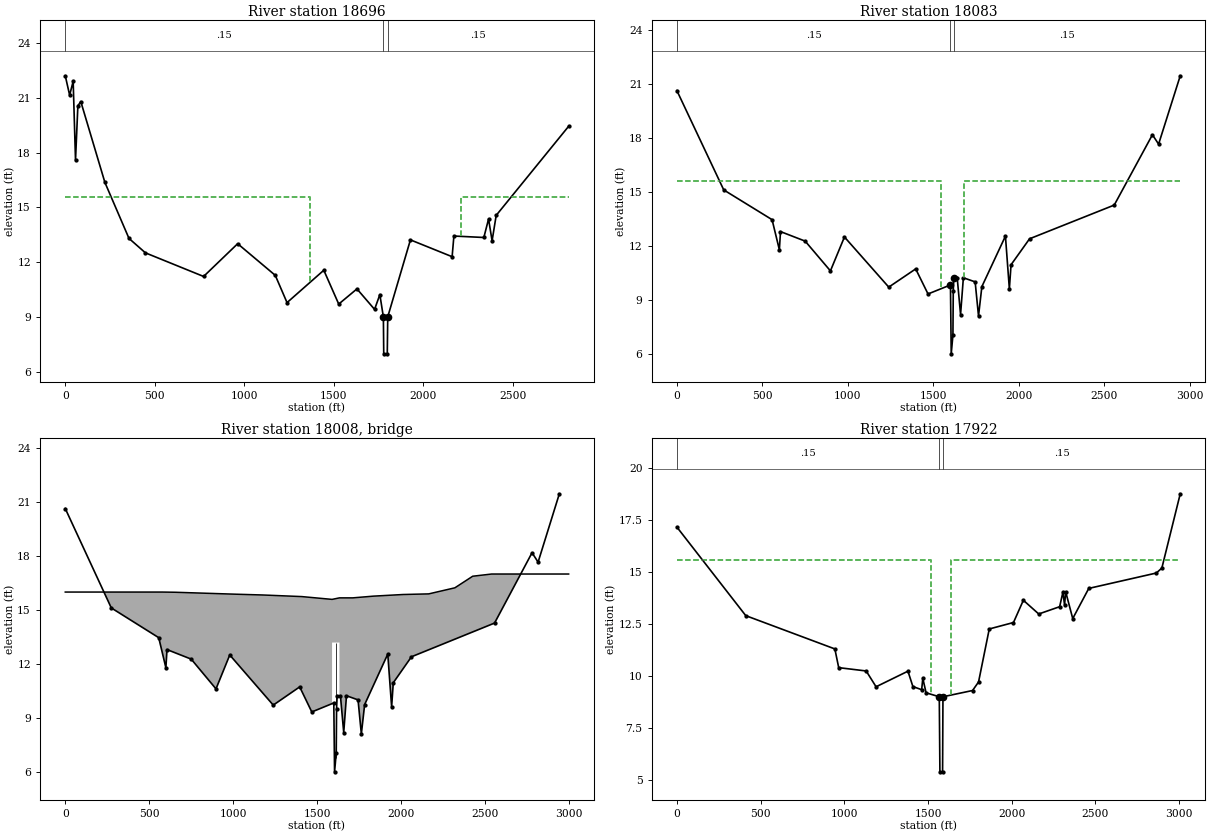
Type RM Length L Ch R = 1 ,18696   ,612.4,612.4,612.4
XS GIS Cut Line= 3
2300024.55007655475467.9829793192300108.29334628472922.503459534
2299989.45341796472684.645367073
#Sta/Elev= 30
       0    22.2    24.4   21.14    44.1    21.9    57.2   17.59    70.4   20.56
    86.8   20.79   221.4   16.37     356   13.31   447.9   12.52   772.9   11.23
   963.3   13.02  1173.5   11.29  1239.1     9.8  1444.6   11.57    1528    9.72
  1629.8   10.55  1728.3    9.43  1757.8   10.24 1777.53    9.01 1779.49       7
 1799.22       7 1801.83    9.02  1928.6   13.23  2161.6   12.31  2171.5   13.44
  2338.9   13.36  2365.2   14.37  2384.9   13.18  2407.9   14.57 2812.75   19.44
#Mann= 3 ,0,0
       0     .15       0 1777.53     .05       0 1801.83     .15       0
#XS Ineff= 2 , 0
            1366   15.59    2210           15.59
Permanent Ineff=
       F       F
Bank Sta=1777.53,1801.83
XS Rating Curve= 0 ,0
Exp/Cntr(USF)=0,0
Exp/Cntr=0.5,0.3

Type RM Length L Ch R = 1 ,18083   ,161.3,161.3,161.3
XS GIS Cut Line= 4
2300186.99074373475628.5958880842300222.43609811475109.814625074
2300214.47431246473089.2015948242300225.02926711472685.421104403
#Sta/Elev= 30
       0   20.63  274.22   15.12  556.98   13.47  599.64    11.8   606.2   12.81
  750.58   12.28  898.24   10.63  980.27   12.51 1239.49    9.73 1396.99   10.74
 1469.18    9.351600.391   9.851 1604.85    6.03 1614.85    7.07 1616.84    9.54
1620.091  10.211 1639.81   10.25 1659.49    8.21  1675.9   10.25 1744.81   10.02
  1764.5    8.13 1784.18    9.76    1922   12.56 1944.97    9.63 1954.81   10.97
 2063.09   12.41 2558.43   14.28 2781.77   18.18 2817.88   17.66 2944.54   21.45
#Mann= 3 ,0,0
       0     .15       01600.391     .05       01620.091     .15       0
#XS Ineff= 2 , 0
            1545   15.59    1679           15.59
Permanent Ineff=
       F       F
Bank Sta=1600.391,1620.091
XS Rating Curve= 0 ,0
Exp/Cntr(USF)=0,0
Exp/Cntr=0.5,0.3

Type RM Length L Ch R = 3 ,18008   ,,,
Node Name=S-791 over Molly
Bridge Culvert-0,0,0,0, 0
Deck Dist Width WeirC Skew NumUp NumDn MinLoCord MaxHiCord MaxSubmerge Is_Ogee
31.67634,41.6,2.6,0, 18, 18, , , 0.98, 0, 2,2,,
       0     577     656    1023    1174    1410    1590    1590    1634    1634
    1713    1837    2012    2166    2322    2428 2540.62    3000
      16      16  15.989  15.879  15.839  15.749  15.594  15.594  15.678  15.678
  15.678  15.774  15.864  15.899  16.236  16.878      17      17
                                                            13.2    13.2
                                                                
     -34     543     622     989    1140    1376    1556    1556    1600    1600
    1679    1803    1978    2132    2288    2394 2506.62    2966
      16      16  15.989  15.879  15.839  15.749  15.594  15.594  15.678  15.678
  15.678  15.774  15.864  15.899  16.236  16.878      17      17
                                                            13.2    13.2
                                                                
Pier Skew, UpSta & Num, DnSta & Num=  ,1612, 2 ,1578, 2 , 0 , 0 , 0 ,,
    1.66    1.66
       0  13.788
    1.66    1.66
       0  13.788
Abutment Skew #Up #Dn= , 2 , 2
    1590    1610
    12.7     2.7
    1556    1576
    12.7     2.7
Abutment Skew #Up #Dn= , 2 , 2
    1614    1634
     2.7    12.7
    1592    1600
     8.7    12.7
BR Coef=-1 ,-1 , 0 ,, 0 ,,,0.8,0,1.2,0,
WSPro=,,,, 1 ,,,, 0 ,,,, 0 ,,,,-1 ,-1 ,-1 , 0 , 0 , 0 , 0 , 0
BC Design=,, 0 ,, 0 ,,,,,,
BC Use User HTab Curves=0
BC User HTab FreeFlow(D)= 0

Type RM Length L Ch R = 1 ,17922   ,1100.1,1100.1,1100.1
XS GIS Cut Line= 6
2300285.47475126475653.991477348  2300324.165683475107.507806008
2300334.00372776474708.9008433122300367.36918183473321.682391052
  2300465.122102473091.7592232922300474.04149011472669.476386347
#Sta/Elev= 30
       0   17.18  411.57   12.92   943.6   11.32  966.57   10.42 1130.68   10.26
 1189.76     9.5 1380.13   10.25 1409.67    9.51 1462.18    9.36 1468.75    9.91
 1488.44    9.21 1567.27    9.02    1571    5.41    1587    5.41 1589.22    9.02
 1765.93    9.32 1801.76    9.73 1865.82   12.28 2010.44   12.59 2069.39   13.66
  2161.3      13 2286.02   13.35 2305.71   14.05 2315.56   13.43 2322.12   14.07
  2364.3   12.78 2460.14   14.23 2863.83   14.97 2896.65   15.21 3006.42   18.78
#Mann= 3 ,0,0
       0     .15       0 1567.27     .05       0 1589.22     .15       0
#XS Ineff= 2 , 0
            1519   15.59    1637           15.59
Permanent Ineff=
       F       F
Bank Sta=1567.27,1589.22
XS Rating Curve= 0 ,0
Exp/Cntr(USF)=0,0
Exp/Cntr=0.5,0.3