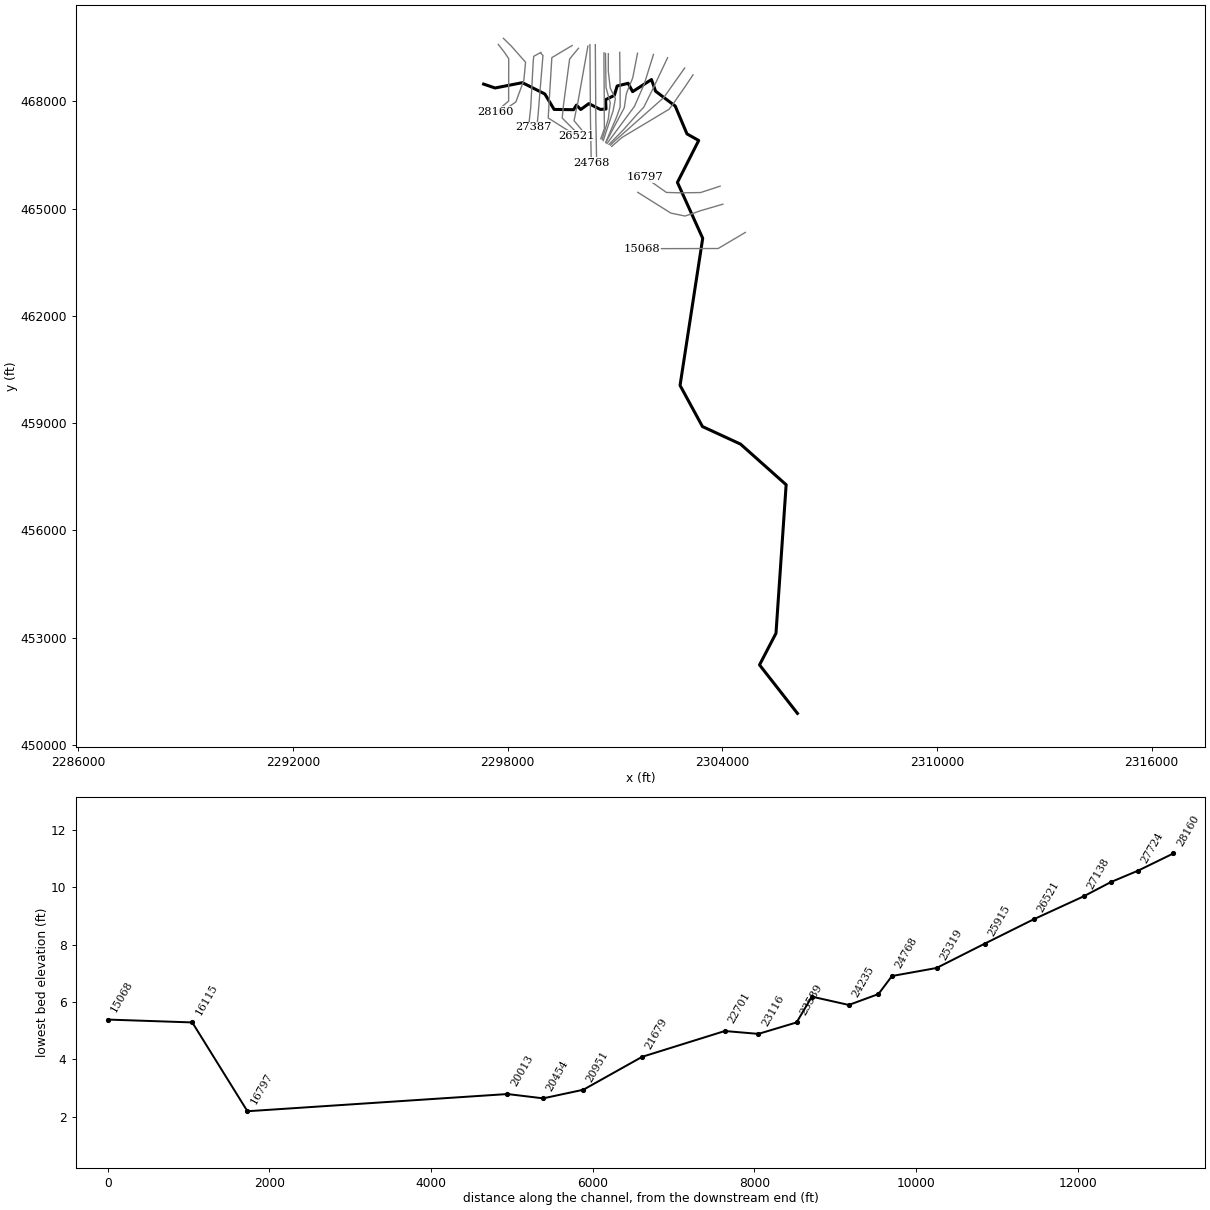
--- WapoolaCreek.prj (project) ---

Proj Title=S-8-791 over Wapoola Creek
Current Plan=p01
Default Exp/Contr=0.3,0.1
English Units
Geom File=g01
Geom File=g10
Geom File=g11
Flow File=f01
Flow File=f02
Flow File=f03
Plan File=p10
Plan File=p01
Plan File=p09
Plan File=p08
Plan File=p02
Plan File=p11
Y Axis Title=Elevation
X Axis Title(PF)=Main Channel Distance
X Axis Title(XS)=Station
BEGIN DESCRIPTION:
END DESCRIPTION:
DSS File=dss
DSS Export Rating Curves= 0
DSS Export Rating Curve Sorted= 0
DSS Export Volume Flow Curves= 0
DXF Filename=SkilbertSwamp.
DXF OffsetX= 0
DXF OffsetY= 0
DXF ScaleX= 1
DXF ScaleY= 10

--- WapoolaCreek.p01 (plan) ---

Plan Title=Existing Conditions
Program Version=6.60
Short Identifier=EX
Geom File=g01
Flow File=f01
Subcritical Flow
K Sum by GR= 0
Std Step Tol= 0.01
Critical Tol= 0.01
Num of Std Step Trials= 20
Max Error Tol= 0.3
Flow Tol Ratio= 0.001
Split Flow NTrial= 30
Split Flow Tol= 0.02
Split Flow Ratio= 0.02
Log Output Level= 0
Friction Slope Method= 1
Unsteady Friction Slope Method= 2
Unsteady Bridges Friction Slope Method= 1
Calc Critical at every XS
Parabolic Critical Depth
Global Vel Dist= 0 , 0 , 0
Global Log Level= 0
CheckData=True
Encroach Param=-1 ,0,0, 2
Flow Ratio Tolerance=0.1
Flow Ratio Min Ratio=0.5
Flow Ratio Max Ratio=4
Flow Ratio Max Iterations= 10
Computation Interval=1MIN
Output Interval=1HOUR
Instantaneous Interval=1HOUR
Mapping Interval=1HOUR
Computation Time Step Use Courant=        0
Computation Time Step Use Time Series=    0
Computation Time Step Count To Double=0
Computation Time Step Max Doubling=0
Computation Time Step Max Halving=0
Computation Time Step Residence Courant=0
Run HTab= 0
Run UNet= 0
Run Sediment= 0
Run PostProcess= 0
Run WQNet= 0
Run RASMapper= 0
UNET Theta= 1
UNET Theta Warmup= 1
UNET ZTol= 0.02
UNET ZSATol= 0.02
UNET MxIter= 20
UNET Max Iter WO Improvement= 0
UNET MaxInSteps= 0
UNET DtIC= 0
UNET DtMin= 0
UNET MaxCRTS= 20
UNET WFStab= 2
UNET SFStab= 1
UNET WFX= 1
UNET SFX= 1
UNET Gravity=32.17405
UNET 1D Methodology=Finite Difference
UNET DSS MLevel= 4
UNET Pardiso=0
UNET DZMax Abort= 100
UNET Use Existing IB Tables=-1
UNET Froude Reduction=False
UNET Froude Limit= 0.8
UNET Froude Power= 4
UNET D1 Cores= 0
UNET WindReference=Eulerian
UNET WindDragFormulation=Hsu (1988)
UNET D2 Coriolis=0
UNET D2 Cores= 0
UNET D2 Theta= 1
UNET D2 Theta Warmup= 1
UNET D2 Z Tol= 0.01
UNET D2 Volume Tol= 0.01
UNET D2 Max Iterations= 20
UNET D2 Advanced Convergence=0
UNET D2 WS Max Tol=0.15
UNET D2 WS RMS Tol=0.002
UNET D2 WS Stall Tol=1
UNET D2 Equation= 0
UNET D2 RampUpFraction=0.1
UNET D2 TimeSlices= 1
UNET D2 Turbulence Formulation=None
UNET D2 Eddy Viscosity=0.3
UNET D2 Transverse Eddy Viscosity=0.1
UNET D2 Smagorinsky Mixing=0.05
UNET D2 BCVolumeCheck=0
UNET D2 Cores=0
UNET D2 SolverType=PARDISO (Direct)
UNET D2 Minimum Iterations= 3
UNET D2 Maximum Iterations= 30
UNET D2 Restart Number= 10
UNET D2 Relaxation Coeff=1.3
UNET D2 SOR Precondition Iterations= 10
UNET D2 ILUT Maximum Fill= 8
UNET D2 ILUT Tolerance=1E-08
UNET D2 Convergence Tolerance=0.00001
PS Theta= 1
PS WS Tol= 0.01
PS Volume Tol= 0.01
PS Max Iterations= 20
PS Equation= 0
PS Advance Time Step=-1
PS Target Courant=0.9
PS Time Slices= 1
PS Iterate With 2D=0
PS Project Initial WSE from DS=-1
PS Ramp Up Initial WSE from US=-1
PS Cores=0
UNET D1D2 MaxIter= 0
UNET D1D2 ZTol=0.01
UNET D1D2 QTol=0.1
UNET D1D2 MinQTol=1
Write IC File= 0
Write IC File at Fixed DateTime=0
Write IC File at Sim End=0
Echo Input=False
Echo Parameters=False
Echo Output=False
Write Detailed= 0
HDF Write Warmup=0
HDF Write Time Slices=0
HDF Flush=0
HDF Compression= 1
HDF Chunk Size= 1
HDF Spatial Parts= 1
HDF Use Max Rows=0
HDF Fixed Rows= 1
Calibration Method= 0
Calibration Iterations= 20
Calibration Max Change=0.05
Calibration Tolerance=0.2
Calibration Maximum=1.5
Calibration Minimum=0.5
Calibration Optimization Method= 1
WQ AD Non Conservative
WQ ULTIMATE=-1
WQ Max Comp Step=1HOUR
WQ Output Interval=15MIN
WQ Output Selected Increments= 0
WQ Create Restart=0
WQ Fixed Restart=0
WQ System Summary=0
WQ Write To DSS=0
Sorting and Armoring Iterations= 10
XS Update Threshold= 0.02
Bed Roughness Predictor= 0
Processes Affected by Predictor=Sediment Only
Hydraulics Update Threshold= 0.02
Energy Slope Method= 1
Volume Change Method= 1
Sediment Retention Method= 0
Sediment TS Multiplier= 1
Warm Up Method= 0
XS Weighting Method= 0
Number of US Weighted Cross Sections= 1
Number of DS Weighted Cross Sections= 1
Upstream XS Weight=0
Main XS Weight=1
Downstream XS Weight=0
Number of DS XS's Weighted with US Boundary= 1
Upstream Boundary Weight= 1
Weight of XSs Associated with US Boundary= 0
Number of US XS's Weighted with DS Boundary= 1
Downstream Boundary Weight= 0.5
Weight of XSs Associated with DS Boundary= 0.5
Percentile Method= 0
Sediment Output Level= 3
Mass or Volume Output= 0
Output Increment Type= 1
Profile and TS Output Increment= 1
Transport Output Increment 1
XS Output Flag= 0
XS Output Increment= 10
Read HDF5 Sediment Hotstart= 0
Sediment Hotstart Type= 0
Write Gradation File= 0
Read Gradation Hotstart= 0
Write HDF5 File= 1
Write Binary Output= 1
Write DSS Sediment File= 0
DSS Sediment Output Type= 1
SV Curve= 0
Specific Gage Flag= 0
Subcell Erosion Methods= 0
Subcell Deposition Methods= 0
Advection Scheme= 1
Matrix Solver= 0
Implicit Weighting Factor= 1
Maximum Outer Loop Convergence Iterations= 5
Convergence Maximum Absolute= 0.001
Convergence RMSE= 0.0001
Grain Fractions Max Abs Error= 0.001
Max Subgrid Regions= 1
Max Subgrid Length Scale= 3.402823E+38
Initial Layer Thickness= 3
Min Layer Thickness= 0.1
Max Layer Thickness= 6
Number of Layers= 5

--- WapoolaCreek.p02 (plan) ---

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Plan Title=Corrected Effective Floodway
Short Identifier=CE-FW
Geom File=g01
Flow File=f02
Encroach River=River 1
Encroach Reach=Reach 1
Encroach Node=28160
       1 1028.64 1407.59
Encroach Node=27724
       1 1175.52 1972.42
Encroach Node=27387
       1  595.82 1863.82
Encroach Node=27138
       1  401.12    1850
Encroach Node=26521
       1   854.3 2891.41
Encroach Node=25915
       1  843.24  2339.2
Encroach Node=25319
       1 1117.89 2161.83
Encroach Node=24768
       1 1359.78 1972.81
Encroach Node=24601
       1 1429.12 1945.95
Encroach Node=24235
       1 1198.98 1699.24
Encroach Node=23778
       1 1149.63 1692.36
Encroach Node=23589
       1 1085.41 1713.79
Encroach Node=23116
       1  877.03 1615.93
Encroach Node=22701
       1  812.93 1757.69
Encroach Node=21679
       1  828.91 1815.52
Encroach Node=20951
       1  896.97  1953.9
Encroach Node=20454
       1  847.15 2018.64
Encroach Node=20013
       1  752.77 2077.95
Encroach Node=16797
       1  424.75 1606.29
Encroach Node=16115
       1  462.69 1513.34
Encroach Node=15068
       1 1039.97 2245.04
Encroach Node=13069
       1  466.86  989.57
Encroach Node=12590
       1   327.9  956.75
Encroach Node=10380
       1  638.17 1894.26
Encroach Node=8262
       1   888.7 1453.47
Encroach Node=5710
       1   668.3 1172.35

--- WapoolaCreek.p08 (plan) ---

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Plan Title=Sensitivity
Short Identifier=SENS
Geom File=g01
Flow File=f03

--- WapoolaCreek.p09 (plan) ---

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Plan Title=Proposed Conditions
Short Identifier=PROP
Geom File=g10
Flow File=f01

--- WapoolaCreek.p10 (plan) ---

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Plan Title=Natural Conditions
Short Identifier=NAT
Geom File=g11
Flow File=f01

--- WapoolaCreek.p11 (plan) ---

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Plan Title=Post Project Floodway
Short Identifier=POST-FW
Geom File=g10
Flow File=f02
Encroach River=River 1
Encroach Reach=Reach 1
Encroach Node=28160
       1 1028.64 1407.59
Encroach Node=27724
       1 1175.52 1972.42
Encroach Node=27387
       1  595.82 1863.82
Encroach Node=27138
       1  401.12    1850
Encroach Node=26521
       1   854.3 2891.41
Encroach Node=25915
       1  843.24  2339.2
Encroach Node=25319
       1 1117.89 2161.83
Encroach Node=24768
       1 1359.78 1972.81
Encroach Node=24601
       1 1429.12 1945.95
Encroach Node=24235
       1 1198.98 1699.24
Encroach Node=23778
       1 1149.63 1692.36
Encroach Node=23589
       1 1085.41 1713.79
Encroach Node=23116
       1  877.03 1615.93
Encroach Node=22701
       1  812.93 1757.69
Encroach Node=21679
       1  828.91 1815.52
Encroach Node=20951
       1  896.97  1953.9
Encroach Node=20454
       1  847.15 2018.64
Encroach Node=20013
       1  752.77 2077.95
Encroach Node=16797
       1  424.75 1606.29
Encroach Node=16115
       1  462.69 1513.34
Encroach Node=15068
       1 1039.97 2245.04
Encroach Node=13069
       1  466.86  989.57
Encroach Node=12590
       1   327.9  956.75
Encroach Node=10380
       1  638.17 1894.26
Encroach Node=8262
       1   888.7 1453.47
Encroach Node=5710
       1   668.3 1172.35

--- WapoolaCreek.f01 (steady flow) ---

Flow Title=USGS Regression
Program Version=6.60
Number of Profiles= 6
Profile Names=2Y,10Y,25Y,50Y,100Y,500Y
River Rch & RM=River 1,Reach 1         ,28160
     149     418     598     766     936    1370
Boundary for River Rch & Prof#=River 1,Reach 1         , 1
Up Type= 0
Dn Type= 3
Dn Slope=0.000025
Boundary for River Rch & Prof#=River 1,Reach 1         , 2
Up Type= 0
Dn Type= 3
Dn Slope=0.000025
Boundary for River Rch & Prof#=River 1,Reach 1         , 3
Up Type= 0
Dn Type= 3
Dn Slope=0.000025
Boundary for River Rch & Prof#=River 1,Reach 1         , 4
Up Type= 0
Dn Type= 3
Dn Slope=0.000025
Boundary for River Rch & Prof#=River 1,Reach 1         , 5
Up Type= 0
Dn Type= 3
Dn Slope=0.000025
Boundary for River Rch & Prof#=River 1,Reach 1         , 6
Up Type= 0
Dn Type= 3
Dn Slope=0.000025
DSS Import GetInterval= 0
DSS Import GetPeak= 0
DSS Import FillOption= 0

--- WapoolaCreek.f02 (steady flow) ---

Flow Title=FIS
Program Version=6.60
Number of Profiles= 2
Profile Names=100Y,100Y-FW
River Rch & RM=River 1,Reach 1         ,28160
     950     950
River Rch & RM=River 1,Reach 1         ,24768
    1190    1190
River Rch & RM=River 1,Reach 1         ,13069
    1480    1480
Boundary for River Rch & Prof#=River 1,Reach 1         , 1
Up Type= 0
Dn Type= 1
Dn Known WS=11.4
Boundary for River Rch & Prof#=River 1,Reach 1         , 2
Up Type= 0
Dn Type= 1
Dn Known WS=12.4
DSS Import GetInterval= 0
DSS Import GetPeak= 0
DSS Import FillOption= 0

--- WapoolaCreek.f03 (steady flow) ---

Flow Title=Sensitivity
Program Version=6.60
Number of Profiles= 3
Profile Names=100Y-3,100Y,100Y+3
River Rch & RM=River 1,Reach 1         ,28160
     936     936     936
Boundary for River Rch & Prof#=River 1,Reach 1         , 1
Up Type= 0
Dn Type= 1
Dn Known WS=8.26
Boundary for River Rch & Prof#=River 1,Reach 1         , 2
Up Type= 0
Dn Type= 1
Dn Known WS=11.26
Boundary for River Rch & Prof#=River 1,Reach 1         , 3
Up Type= 0
Dn Type= 1
Dn Known WS=14.26
DSS Import GetInterval= 0
DSS Import GetPeak= 0
DSS Import FillOption= 0

--- WapoolaCreek.g01 (geometry) ---

Geom Title=Existing Conditions
Program Version=6.60

River Reach=River 1         ,Reach 1
Reach XY= 30
2297328.12706112468485.4161976672297647.50310698468376.917448161
2298411.91214357468525.4797453442299039.21005796468208.542982663
2299297.89037299467777.4091242752299842.19686921 467769.32536443
2299922.59110803467898.2221623212300042.34821854467774.874189177
2300267.70756472467939.0267620852300589.41869313467777.060608518
2300748.33784525467788.558455471 2300736.5517234468049.416864705
2300980.18866062468167.9925924282301060.32956809468432.019017101
2301366.76411063468507.8950947672301492.27486237 468274.35046283
2302018.65016498468612.3042938742302133.99658104468286.362925089
2302683.17612482467870.8715324452303011.86583148467092.273211102
2303339.28382684466908.5805123622302744.36539272465736.021935212
2303451.38971345464172.8649825792302818.26143317 460058.51565423
2303443.99141428458907.7206164912304509.86920541 458415.24557382
2305783.32210744457279.7701360172305499.39807956453125.343993496
2305039.32900606 452241.249389492306099.28889539450884.947619671

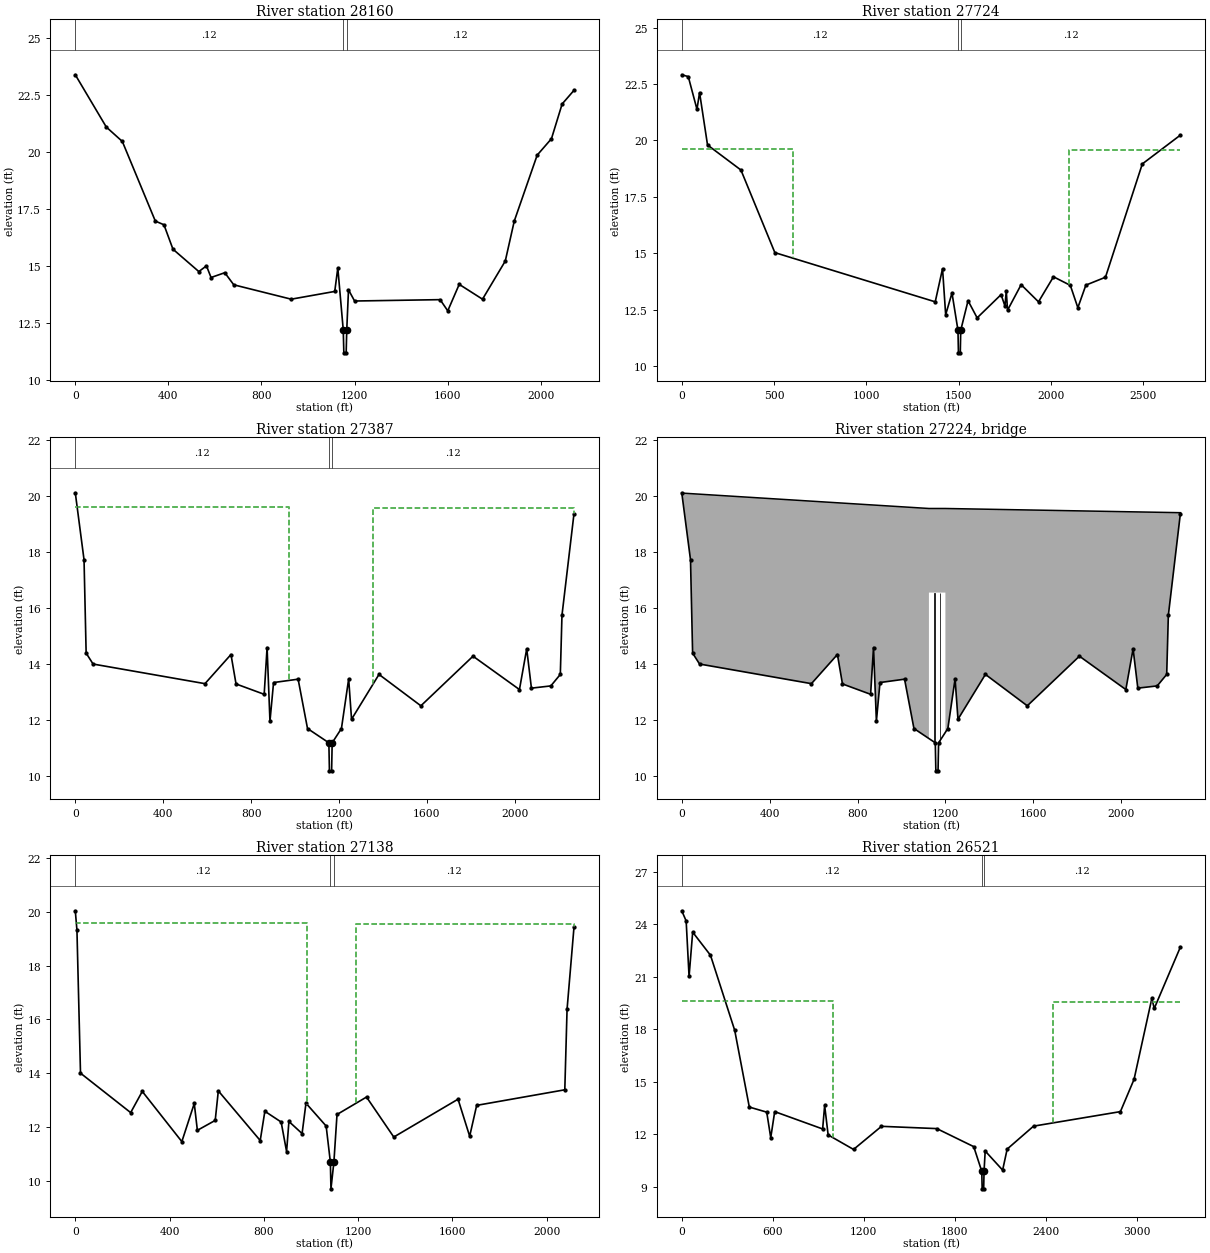
Type RM Length L Ch R = 1 ,28160   ,435.9,435.9,435.9
BEGIN DESCRIPTION:
LETTERED XS Q (Channel bottom from FIS profile)
END DESCRIPTION:
Node Name=Q
XS GIS Cut Line= 5
 2297737.4755506469594.5744884132297896.52194417469391.915058591
2298029.42576155469198.858130839  2298026.354717468009.905794509
2297672.12104847467713.076871271
#Sta/Elev= 30
       0   23.37   133.3   21.08   202.1   20.45     344   16.96     381    16.8
   419.7   15.73   530.9   14.75   563.7      15   583.4   14.49   642.4    14.7
     681   14.17   927.9   13.54  1114.9   13.88  1128.1   14.91  1151.5   12.19
    1154   11.19    1164   11.19  1166.5   12.19    1174   13.95  1200.2   13.46
  1567.7   13.52  1600.6   13.03  1649.8   14.19  1749.9   13.54  1847.7   15.21
  1886.3   16.96  1984.8   19.85  2046.2   20.57    2092   22.09  2143.1   22.69
#Mann= 3 ,0,0
       0     .12       0  1151.5     .05       0  1166.5     .12       0
Bank Sta=1151.5,1166.5
XS Rating Curve= 0 ,0
Exp/Cntr(USF)=0,0
Exp/Cntr=0.5,0.3

Type RM Length L Ch R = 1 ,27724   ,337.1,337.1,337.1
XS GIS Cut Line= 6
2297880.00745647469765.4117417842298093.82701006469557.300061638
2298500.66261166469095.9649418632298452.02862846  468592.0207081
2298228.33834366467984.7648489292297704.23925334467626.248389513
#Sta/Elev= 30
       0   22.91    35.3   22.83    82.4   21.38    96.5   22.12   139.6    19.8
   320.6   18.69   504.4   15.03  1373.3   12.85  1412.9   14.32  1429.8   12.28
  1464.1   13.24  1496.5   11.59    1499   10.59    1509   10.59  1511.5   11.59
  1551.1    12.9  1600.3   12.14  1730.1   13.17  1751.1   12.66  1758.1   13.33
  1765.1   12.48  1838.7   13.61  1932.8   12.85  2013.9   13.96  2105.2   13.58
    2146   12.59  2189.4   13.59  2295.6   13.94  2495.2   18.96    2702   20.24
#Mann= 3 ,0,0
       0     .12       0  1496.5     .05       0  1511.5     .12       0
#XS Ineff= 2 , 0
       0     600    19.6    2100       0   19.56
Permanent Ineff=
       F       F
Bank Sta=1496.5,1511.5
XS Rating Curve= 0 ,0
Exp/Cntr(USF)=0,0
Exp/Cntr=0.5,0.3

Type RM Length L Ch R = 1 ,27387   ,338.6,338.6,338.6
BEGIN DESCRIPTION:
LETTERED XS P
END DESCRIPTION:
Node Name=P
XS GIS Cut Line= 6
2298928.58568252  469370.82540942298729.54475167469263.772795496
2298715.27575519469133.6163705522298643.53410227467823.344480318
2298600.09441483467432.4251396622298734.76331755467275.200004828
#Sta/Elev= 30
       0   20.11    39.8   17.72    49.4   14.39      81      14   590.2    13.3
   708.5   14.34   731.5   13.29   859.6   12.92   872.8   14.59   885.9   11.96
   902.3   13.34  1014.1   13.46  1056.8    11.7    1154   11.19  1156.5   10.19
  1166.5   10.19    1169   11.19  1211.2    11.7  1244.1   13.47  1257.2   12.03
  1382.1   13.63  1572.7   12.51    1810   14.28  2021.3   13.09  2054.3   14.54
  2075.8   13.14  2164.1   13.22  2207.3   13.63  2214.8   15.74  2269.6   19.37
#Mann= 3 ,0,0
       0     .12       0    1154     .05       0    1169     .12       0
#XS Ineff= 2 , 0
       0     972    19.6    1353       0   19.56
Permanent Ineff=
       F       F
Bank Sta=1154,1169
XS Rating Curve= 0 ,0
Exp/Cntr(USF)=0,0
Exp/Cntr=0.5,0.3

Type RM Length L Ch R = 3 ,27224   ,,,
BEGIN DESCRIPTION:
RR Bridge
END DESCRIPTION:
Bridge Culvert--1,0,-1,-1, 0
Deck Dist Width WeirC Skew NumUp NumDn MinLoCord MaxHiCord MaxSubmerge Is_Ogee
153,14,2.6,0, 6, 6, , , 0.98, 0, 2,2,,
       0 1124.99    1125    1200 1200.01    2270
    20.1   19.55   19.55   19.55   19.55    19.4
                   16.55   16.55
       0 1049.99    1050    1125 1125.01    2163
    20.1   19.55   19.55   19.55   19.55    19.4
                   16.55   16.55
Pier Skew, UpSta & Num, DnSta & Num=  ,1150, 2 ,1075, 2 , 0 , 0 , 0 ,,
       3       3
      11   16.55
       3       3
      11   16.55
Pier Skew, UpSta & Num, DnSta & Num=  ,1175, 2 ,1100, 2 , 0 , 0 , 0 ,,
       3       3
      11   16.55
       3       3
      11   16.55
BR Coef=-1 , 0 , 0 ,, 0 ,,,0.8,-1,,0,
WSPro=,,,, 1 ,,,, 0 ,,,, 0 ,,,,-1 ,-1 ,-1 , 0 , 0 , 0 , 0 , 0
BC Design=,, 0 ,, 0 ,,,,,,
BC Use User HTab Curves=0
BC User HTab FreeFlow(D)= 0

Type RM Length L Ch R = 1 ,27138   ,616.8,616.8,616.8
XS GIS Cut Line= 6
2298927.22557656 469347.187328752298986.50411543469287.117654173
2298893.59065445468162.639112454  2298850.501842467627.503043139
2298827.09096331467387.3054406782298741.34071938467295.576624683
#Sta/Elev= 30
       0   20.05       7   19.33    22.1      14     235   12.53   284.3   13.32
   452.2   11.45   504.9   12.87   518.1   11.87   593.8   12.24     607   13.34
   784.8   11.49   804.5   12.58   873.6   12.18   896.7   11.08   906.6    12.2
   962.5   11.75     979   12.88  1064.6   12.03  1082.5   10.69    1085    9.69
  1097.5   10.69  1110.7   12.46  1235.9   13.11  1351.6   11.62  1624.3   13.03
  1673.7   11.65  1703.4    12.8  2077.4   13.38    2087   16.38  2116.5   19.45
#Mann= 3 ,0,0
       0     .12       0  1082.5     .05       0  1097.5     .12       0
#XS Ineff= 2 , 0
       0     984    19.6    1191       0   19.56
Permanent Ineff=
       F       F
Bank Sta=1082.5,1097.5
XS Rating Curve= 0 ,0
Exp/Cntr(USF)=0,0
Exp/Cntr=0.5,0.3

Type RM Length L Ch R = 1 ,26521   ,605.4,605.4,605.4
BEGIN DESCRIPTION:
LETTERED XS O
END DESCRIPTION:
Node Name=O
XS GIS Cut Line= 6
2299803.49818954 469565.298890882299234.77529976469226.028905159
2299154.43961107467912.5107570932299153.44718615467897.624383265
2299133.69131487467537.0589689482299923.05695193467037.864326231
#Sta/Elev= 30
       0   24.77      29   24.19    48.2   21.02      72   23.55   189.4   22.23
   349.2   17.94   445.4   13.56   560.2   13.27   586.7   11.81   612.8    13.3
   928.9   12.31   942.1   13.65   965.1   11.97  1132.7   11.14  1316.8   12.46
  1681.7   12.33    1925    11.3  1978.1    9.89  1980.6    8.89  1990.6    8.89
  1993.1    9.89  2000.6   11.05  2115.6    9.96  2145.5   11.16  2319.4   12.47
  2892.2    13.3    2982   15.14  3099.5   19.77  3115.2   19.19  3288.2   22.71
#Mann= 3 ,0,0
       0     .12       0  1978.1     .05       0  1993.1     .12       0
#XS Ineff= 2 , 0
       0    1000    19.6    2450       0   19.56
Permanent Ineff=
       F       F
Bank Sta=1978.1,1993.1
XS Rating Curve= 0 ,0
Exp/Cntr(USF)=0,0
Exp/Cntr=0.5,0.3

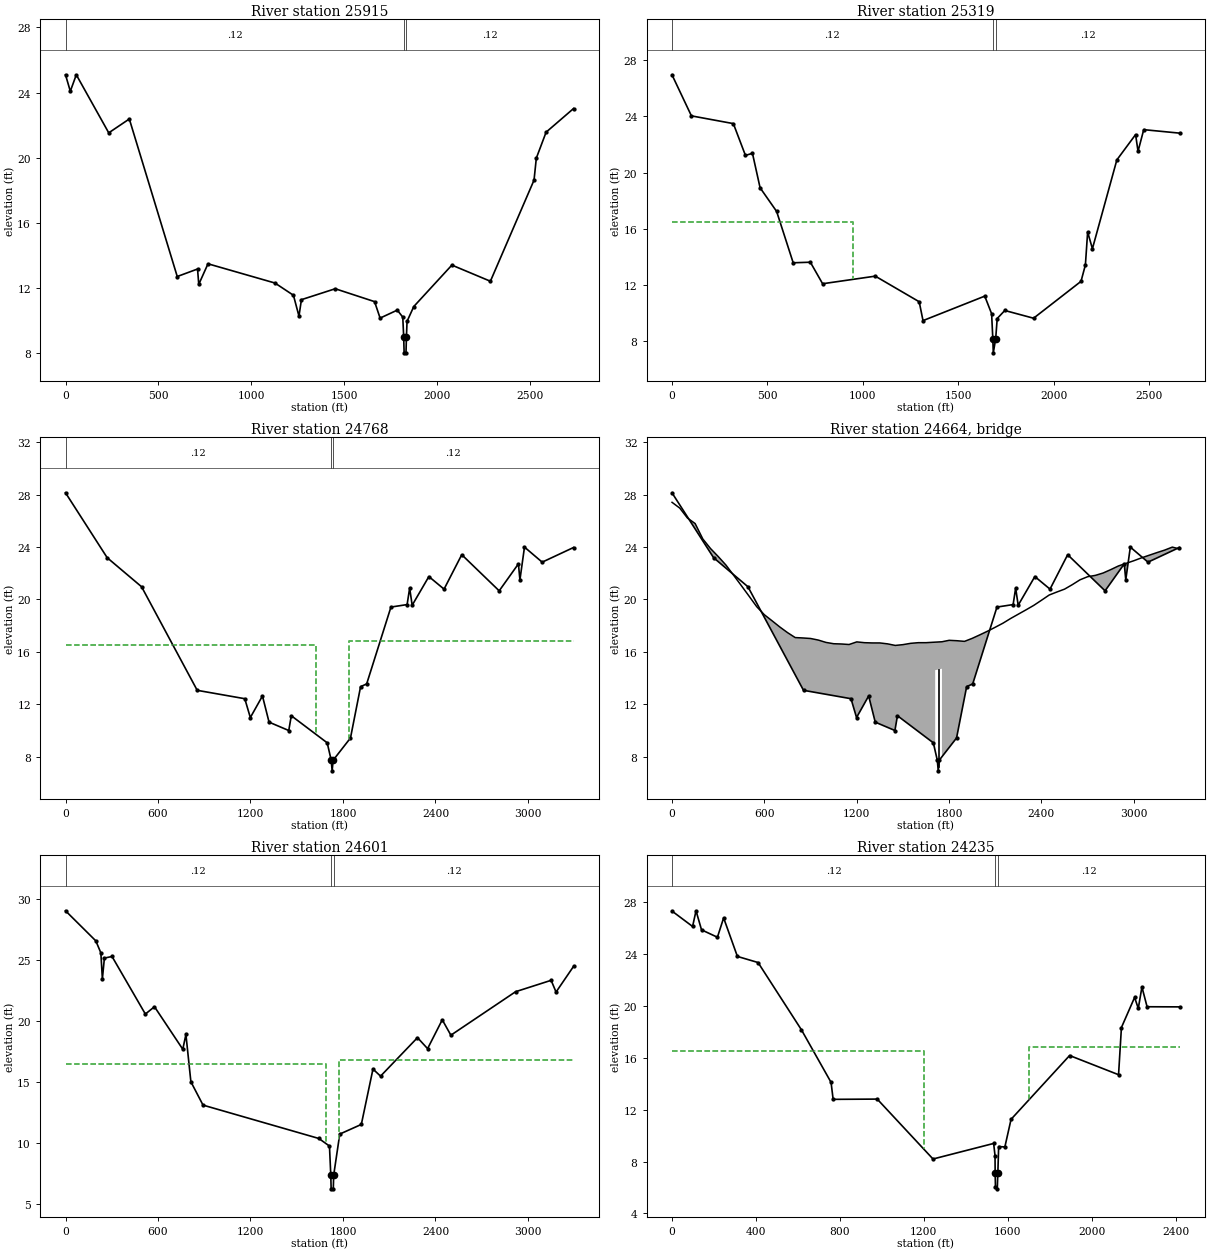
Type RM Length L Ch R = 1 ,25915   ,596.3,596.3,596.3
XS GIS Cut Line= 6
  2299978.943536469486.9291452262299731.49713724469188.243408806
 2299552.5489904467843.9374370592299545.82417894 467759.29731793
2299523.38360181467537.0589689482300006.84857433467053.937453047
#Sta/Elev= 30
       0   25.09    25.9   24.08    58.1   25.09   232.8   21.53   343.6   22.38
   601.7   12.72     711   13.18   717.6   12.24   767.3    13.5  1128.1   12.32
  1227.4   11.57  1257.2   10.29  1270.4    11.3  1452.5   11.97  1664.3   11.18
  1694.1   10.17  1786.7   10.66  1816.2   10.23    1821    9.04  1823.5    8.04
  1833.5    8.04    1836    9.04  1839.2    9.97  1875.5   10.88  2080.6   13.42
    2288   12.43    2523   18.63  2535.4   19.98    2588   21.57  2735.8   23.02
#Mann= 3 ,0,0
       0     .12       0    1821     .05       0    1836     .12       0
#XS Ineff= 2 , 0
       0 249.025   16.492550.975       0    16.8
Permanent Ineff=
       F       F
Bank Sta=1821,1836
XS Rating Curve= 0 ,0
Exp/Cntr(USF)=0,0
Exp/Cntr=0.5,0.3

Type RM Length L Ch R = 1 ,25319   ,551.1,551.1,551.1
XS GIS Cut Line= 5
2300242.39242795469548.6018239872299953.51308862467923.566066384
2299935.48686758467861.7913910882299855.50303648467461.845142113
2300198.88760843467048.376502058
#Sta/Elev= 30
       0   26.95   101.8   24.03   321.4   23.48   384.7   21.22   421.4   21.37
   461.4   18.92     548   17.24   634.7   13.59   724.6   13.63   788.8    12.1
  1064.6   12.64  1294.5   10.82  1314.5    9.48  1637.8   11.22 1673.71    9.97
    1680    8.19  1682.5    7.19    1695    8.19 1702.99    9.63  1742.8    10.2
  1893.4    9.65  2141.8   12.27  2164.8   13.44  2176.5   15.78  2201.5   14.59
  2329.5    20.9  2427.6    22.7  2440.4   21.51  2470.2   23.05  2660.2    22.8
#Mann= 3 ,0,0
       0     .12       0    1680     .05       0    1695     .12       0
#XS Ineff= 2 , 0
       0 949.025   16.492300.975       0    16.8
Permanent Ineff=
       F       F
Bank Sta=1680,1695
XS Rating Curve= 0 ,0
Exp/Cntr(USF)=0,0
Exp/Cntr=0.5,0.3

Type RM Length L Ch R = 1 ,24768   ,167.5,167.5,167.5
BEGIN DESCRIPTION:
LETTERED XS N (Channel bottom from Survey)
END DESCRIPTION:
Node Name=N
XS GIS Cut Line= 4
 2300298.8673546 469587.919463872300304.48241966468843.837061898
2300313.49474258467517.3176863722300336.38493535466292.152987895
#Sta/Elev= 30
       0   28.15   270.4   23.19   493.6   20.97   854.5   13.06    1163   12.42
  1199.1   10.98  1277.8   12.63  1320.5   10.63  1448.4    9.99  1464.8   11.12
  1697.8    9.05  1723.8    7.72 1729.83    6.91 1736.27    7.72  1848.8    9.42
  1914.4   13.34  1953.8   13.55  2111.3   19.42  2216.3   19.61  2232.7   20.87
  2249.1   19.56  2357.4   21.75  2455.9   20.79  2570.7   23.42  2813.6   20.66
  2938.3   22.72  2948.1    21.5  2977.7      24  3092.5   22.85    3296   23.97
#Mann= 3 ,0,0
       0     .12       0  1723.8     .05       0 1736.27     .12       0
#XS Ineff= 2 , 0
       01626.025   16.491837.975       0    16.8
Permanent Ineff=
       F       F
Bank Sta=1723.8,1736.27
XS Rating Curve= 0 ,0
Exp/Cntr(USF)=0,0
Exp/Cntr=0.5,0.3

Type RM Length L Ch R = 3 ,24664   ,,,
BEGIN DESCRIPTION:
S-8-791 over Wapoola Creek
END DESCRIPTION:
Bridge Culvert--1,0,-1,-1, 0
Deck Dist Width WeirC Skew NumUp NumDn MinLoCord MaxHiCord MaxSubmerge Is_Ogee
83.975,41.6,2.6,0, 69, 69, , , 0.98, 0, 2,2,,
      .5    50.5   100.5   150.5   200.5   250.5   300.5   350.5   400.5   450.5
   500.5   550.5   600.5   650.5   700.5   750.5   800.5   850.5   900.5   950.5
  1000.5  1050.5  1100.5  1150.5  1200.5  1250.5  1300.5  1350.5  1400.5  1450.5
  1500.5  1550.5  1600.5  1650.5 1709.99    1710    1754 1754.01  1800.5  1850.5
  1900.5  1950.5  2000.5  2050.5  2100.5  2150.5  2200.5  2250.5  2300.5  2350.5
  2400.5  2450.5  2500.5  2550.5  2600.5  2650.5  2700.5  2750.5  2800.5  2850.5
  2900.5  2950.5  3000.5  3050.5  3100.5  3150.5  3200.5  3250.5  3300.5
   27.42   26.98   26.22    25.8   24.62   23.89   23.28   22.63   21.85   21.06
   20.26   19.45   18.83   18.37    17.9   17.47   17.09   17.06   17.02    16.9
   16.72   16.62    16.6   16.56   16.76    16.7   16.68   16.68   16.61   16.49
   16.55   16.65    16.7    16.7   16.74   16.74   16.77   16.77   16.88   16.85
    16.8   17.03    17.3   17.58   17.88   18.19   18.55   18.88   19.21   19.55
   19.94   20.34   20.57   20.79   21.13    21.5   21.74   21.84   22.02   22.28
   22.56   22.76   22.96   23.18   23.38   23.58   23.77      24   23.85
                                                                                
                                                                                
                                                                                
                                            14.6   14.71
                                                                                
                                                                                
                                                                        
      .5    50.5   100.5   150.5   200.5   250.5   300.5   350.5   400.5   450.5
   500.5   550.5   600.5   650.5   700.5   750.5   800.5   850.5   900.5   950.5
  1000.5  1050.5  1100.5  1150.5  1200.5  1250.5  1300.5  1350.5  1400.5  1450.5
  1500.5  1550.5  1600.5  1650.5 1709.99    1710    1754 1754.01  1800.5  1850.5
  1900.5  1950.5  2000.5  2050.5  2100.5  2150.5  2200.5  2250.5  2300.5  2350.5
  2400.5  2450.5  2500.5  2550.5  2600.5  2650.5  2700.5  2750.5  2800.5  2850.5
  2900.5  2950.5  3000.5  3050.5  3100.5  3150.5  3200.5  3250.5  3300.5
   27.42   26.98   26.22    25.8   24.62   23.89   23.28   22.63   21.85   21.06
   20.26   19.45   18.83   18.37    17.9   17.47   17.09   17.06   17.02    16.9
   16.72   16.62    16.6   16.56   16.76    16.7   16.68   16.68   16.61   16.49
   16.55   16.65    16.7    16.7   16.74   16.74   16.77   16.77   16.88   16.85
    16.8   17.03    17.3   17.58   17.88   18.19   18.55   18.88   19.21   19.55
   19.94   20.34   20.57   20.79   21.13    21.5   21.74   21.84   22.02   22.28
   22.56   22.76   22.96   23.18   23.38   23.58   23.77      24   23.85
                                                                                
                                                                                
                                                                                
                                            14.6   14.71
                                                                                
                                                                                
                                                                        
Pier Skew, UpSta & Num, DnSta & Num=  ,1732, 2 ,1732, 2 , 0 , 0 , 0 ,,
    1.67    1.67
       6      15
    1.67    1.67
       6      15
Abutment Skew #Up #Dn= , 3 , 3
 1709.99 1711.99 1720.39
    12.6    12.6     8.4
 1709.99 1711.99 1720.39
    12.6    12.6     8.4
Abutment Skew #Up #Dn= , 3 , 3
 1743.59 1752.01 1754.01
     8.5   12.71   12.71
 1743.59 1752.01 1754.01
     8.5   12.71   12.71
BR Coef=-1 ,-1 ,-1 ,0.9, 0 ,,,0.8,0,1.2,0,
WSPro=,,,, 1 ,,,, 0 ,,,, 0 ,,,,-1 ,-1 ,-1 , 0 , 0 , 0 , 0 , 0
BC Design=,, 0 ,, 0 ,,,,,,
BC Use User HTab Curves=0
BC User HTab FreeFlow(D)= 0

Type RM Length L Ch R = 1 ,24601   ,366.1,366.1,366.1
XS GIS Cut Line= 4
2300449.31206972469589.4839137532300454.92713478468845.401511781
 2300463.9394577467518.8821362552300486.82965047466293.717437778
#Sta/Elev= 30
       0   29.03   196.5   26.57   229.3   25.59   239.2   23.46   252.3   25.16
   301.8   25.29   518.1   20.58   577.2   21.18   760.9    17.7   781.2   18.91
   813.4   15.04   892.2   13.13  1643.6    10.4  1712.5    9.78 1721.09    7.38
 1723.32    6.28 1737.38    6.28 1739.74    7.39  1779.3   10.76  1919.2   11.55
  1994.7   16.08  2043.9    15.5  2283.5   18.65  2349.1   17.75  2444.3   20.11
  2500.1   18.85  2920.2   22.41  3150.5   23.34  3182.5   22.38    3296   24.48
#Mann= 3 ,0,0
       0     .12       0 1721.09     .05       0 1739.74     .12       0
#XS Ineff= 2 , 0
       01690.012   16.491773.988       0    16.8
Permanent Ineff=
       F       F
Bank Sta=1721.09,1739.74
XS Rating Curve= 0 ,0
Exp/Cntr(USF)=0,0
Exp/Cntr=0.5,0.3

Type RM Length L Ch R = 1 ,24235   ,456.9,456.9,456.9
BEGIN DESCRIPTION:
LETTERED XS M (Channel bottom from Survey)
END DESCRIPTION:
Node Name=M
XS GIS Cut Line= 6
2300691.89821835469359.8917309122300690.27254581469153.431319064
2300701.55822337467819.9775441342300697.65414775467809.851347998
2300703.40781971467237.8111847652300602.36719703466958.674533622
#Sta/Elev= 30
       0   27.32    98.2   26.13   114.6   27.34   140.8   25.87   216.5    25.3
   246.1   26.79   311.7   23.82   410.1   23.35   616.8   18.16   757.9   14.11
   767.8    12.8   977.8   12.82  1243.6     8.2  1532.4     9.4    1539    8.47
 1539.64    7.14  1541.1    6.03  1549.7     5.9  1552.5    7.13  1556.3    9.16
  1585.9    9.13  1615.4   11.26  1894.3   16.18  2127.5    14.7  2141.2   18.34
    2204   20.66  2221.5   19.81  2238.9   21.46  2263.4   19.94  2420.3   19.93
#Mann= 3 ,0,0
       0     .12       0 1539.64     .05       0  1552.5     .12       0
#XS Ineff= 2 , 0
       01199.512   16.491700.488       0    16.8
Permanent Ineff=
       F       F
Bank Sta=1539.64,1552.5
XS Rating Curve= 0 ,0
Exp/Cntr(USF)=0,0
Exp/Cntr=0.5,0.3

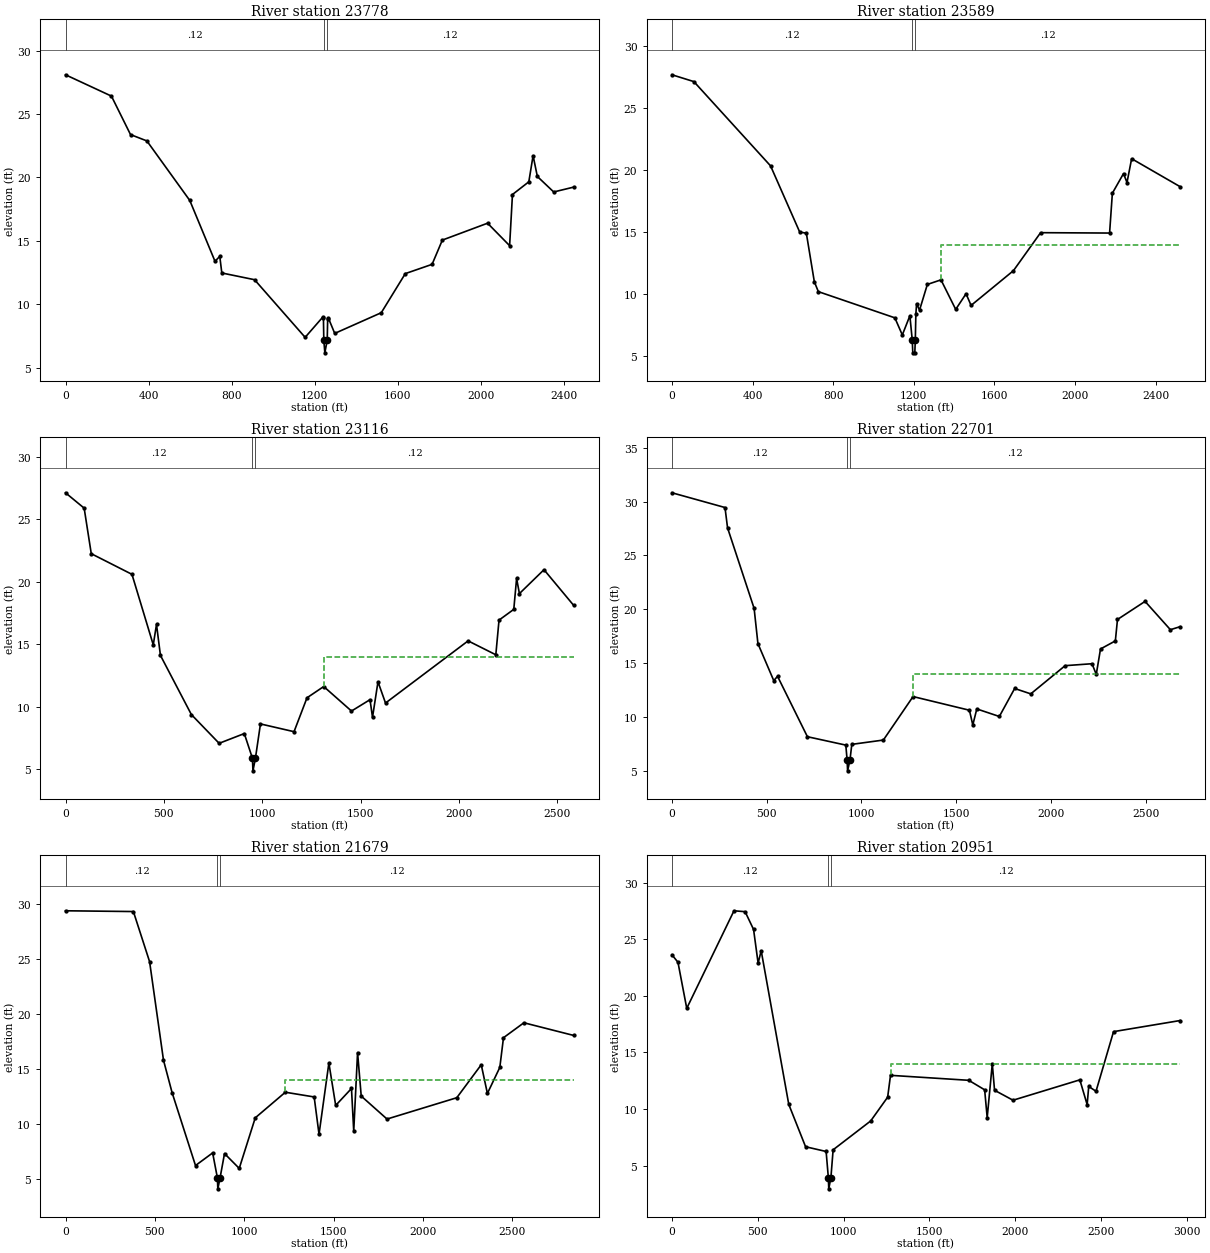
Type RM Length L Ch R = 1 ,23778   ,189.1,189.1,189.1
XS GIS Cut Line= 5
 2300734.2461279469341.8034746872300748.86795574 468391.38466571
2300865.84257838467962.4777160182300812.22920967467509.201053275
2300641.64121831 466938.94976789
#Sta/Elev= 30
       0   28.09   221.2   26.41   313.1   23.38   391.9   22.88   598.6   18.19
     720    13.4     743   13.79   752.8   12.48   910.4   11.95  1154.1    7.41
  1238.8       9  1242.2    8.96    1244    7.19    1249    6.19 1260.46    7.19
  1262.6    8.88    1266    8.93  1296.6    7.72  1520.8    9.35  1636.5   12.43
  1765.5   13.16  1814.9   15.07  2032.7    16.4  2138.9   14.63  2152.6   18.66
  2231.4   19.66  2251.9   21.72  2272.5   20.08  2351.2   18.86  2446.8   19.24
#Mann= 3 ,0,0
       0     .12       0    1244     .05       0 1260.46     .12       0
Bank Sta=1244,1260.46
XS Rating Curve= 0 ,0
Exp/Cntr(USF)=0,0
Exp/Cntr=0.3,0.1

Type RM Length L Ch R = 1 ,23589   ,472.2,472.2,472.2
XS GIS Cut Line= 6
2300813.60767496469334.2949013382300813.60767496468839.102332148
2300867.22104368468371.6912358362301011.69436764468081.947900386
2300947.57928926 467739.099199852300669.82636797 466902.19753888
#Sta/Elev= 30
       0   27.69   108.7   27.14   489.3   20.35   633.9   15.02   666.8   14.93
   706.4   11.02   726.3   10.22    1106    8.11  1143.1    6.73  1180.6    8.28
  1192.5    6.29    1195    5.29    1205    5.29  1207.5    6.29  1210.3    8.42
  1213.9    9.25  1228.5    8.73  1267.3    10.8  1334.9   11.17    1408    8.79
  1459.3   10.05  1484.3    9.11  1694.5   11.91  1829.3   14.97  2171.6   14.94
  2185.4   18.15  2240.7   19.73    2258   19.01    2281   20.93  2521.1   18.68
#Mann= 3 ,0,0
       0     .12       0  1192.5     .05       0  1207.5     .12       0
#XS Ineff= 2 , 0
       0                  1334.9       0      14
Permanent Ineff=
       F       F
Bank Sta=1192.5,1207.5
XS Rating Curve= 0 ,0
Exp/Cntr(USF)=0,0
Exp/Cntr=0.3,0.1

Type RM Length L Ch R = 1 ,23116   ,415.7,415.7,415.7
XS GIS Cut Line= 5
2301131.34041205469372.9385808742301143.37483825468422.218911341
2301143.37483825467844.5664539032301047.85435224467571.792470774
2300746.47946227466869.537243461
#Sta/Elev= 30
       0   27.12    94.8   25.89   130.9   22.25   337.7    20.6     446   14.96
   462.4    16.6   482.4   14.12   639.6    9.39   780.7    7.09   908.6    7.87
     950    5.89   952.5    4.89     965    5.89   990.7    8.64  1161.3    8.02
  1227.2   10.73  1312.2   11.63  1453.3    9.67  1547.4   10.58  1560.1    9.17
  1587.9   12.01  1626.2   10.31  2045.9   15.28  2186.7   14.17    2203   16.94
    2278    17.8  2292.3   20.27  2306.6   19.06  2431.5   20.97  2581.7   18.13
#Mann= 3 ,0,0
       0     .12       0     950     .05       0     965     .12       0
#XS Ineff= 2 , 0
       0                  1315.2       0      14
Permanent Ineff=
       F       F
Bank Sta=950,965
XS Rating Curve= 0 ,0
Exp/Cntr(USF)=0,0
Exp/Cntr=0.3,0.1

Type RM Length L Ch R = 1 ,22701   ,1021.7,1021.7,1021.7
XS GIS Cut Line= 6
2301629.89948779469349.362652073 2301495.1204016 468658.07991878
2301348.13253272468300.2897328482301313.51040238468193.901677413
2301259.98004178467825.9552139932300741.37792624466848.666359408
#Sta/Elev= 30
       0   30.82   279.9   29.45   293.4   27.56   433.6   20.08   453.7   16.81
   537.3   13.37   557.3   13.77   714.9    8.16   917.6    7.38   924.5    5.99
     927    4.99   939.5    5.99   949.3    7.45  1115.8    7.85  1272.6   11.89
  1570.1   10.62  1587.9    9.25  1609.1   10.74    1728   10.04  1808.9   12.64
  1893.9   12.14  2075.3   14.76  2217.2   14.94  2239.6   13.95    2262   16.31
  2340.4   17.06  2351.6   19.05  2497.2   20.73  2630.9    18.1  2681.7   18.38
#Mann= 3 ,0,0
       0     .12       0   924.5     .05       0   939.5     .12       0
#XS Ineff= 2 , 0
       0                  1272.6       0      14
Permanent Ineff=
       F       F
Bank Sta=924.5,939.5
XS Rating Curve= 0 ,0
Exp/Cntr(USF)=0,0
Exp/Cntr=0.3,0.1

Type RM Length L Ch R = 1 ,21679   ,728,728,728
XS GIS Cut Line= 4
2302075.46116425469315.7757536512301819.31072934468492.685218829
2301542.99719806467861.0056250092300776.21828518466823.488605643
#Sta/Elev= 30
       0   29.39   379.7   29.32   470.3   24.76     548    15.8   596.2   12.84
   727.1    6.21     823    7.36   849.5    5.09     852    4.09   864.5    5.09
   889.4     7.3   971.7    5.95  1061.3   10.55  1229.6   12.88  1390.8   12.45
    1418    9.06  1473.1   15.54  1511.2   11.68  1599.5   13.22  1612.1    9.35
  1633.6   16.49    1654   12.53  1798.3   10.44  2188.5   12.38  2325.3   15.38
  2359.8   12.77  2429.2   15.14  2449.7   17.84  2563.9    19.2  2841.6   18.05
#Mann= 3 ,0,0
       0     .12       0   849.5     .05       0   864.5     .12       0
#XS Ineff= 2 , 0
       0                  1229.6       0      14
Permanent Ineff=
       F       F
Bank Sta=849.5,864.5
XS Rating Curve= 0 ,0
Exp/Cntr(USF)=0,0
Exp/Cntr=0.3,0.1

Type RM Length L Ch R = 1 ,20951   ,496.6,496.6,496.6
XS GIS Cut Line= 6
2302469.88134281469224.3793634432302074.55044225468384.978136227
2301803.77585283 467838.013465592301646.41127995467673.029264329
2301227.80853499467199.8622153142300833.05544833466799.929758738
#Sta/Elev= 30
       0   23.62    34.9   22.96    86.1   18.89   361.3   27.51   426.1   27.43
   475.4   25.86   501.9   22.88   519.8   23.98   680.5    10.4   778.4    6.66
   898.1    6.24     911    3.94   913.5    2.94     926    3.94   938.9    6.39
  1157.8    8.94  1256.6   11.04  1273.2   12.97  1729.1   12.53  1821.7   11.69
  1836.5    9.23  1866.2   13.99  1879.3   11.65  1987.1   10.77  2376.3   12.57
  2418.9   10.38    2428   11.99  2470.5   11.56  2572.6   16.83  2959.9   17.81
#Mann= 3 ,0,0
       0     .12       0     911     .05       0     926     .12       0
#XS Ineff= 2 , 0
       0                  1273.2       0      14
Permanent Ineff=
       F       F
Bank Sta=911,926
XS Rating Curve= 0 ,0
Exp/Cntr(USF)=0,0
Exp/Cntr=0.3,0.1

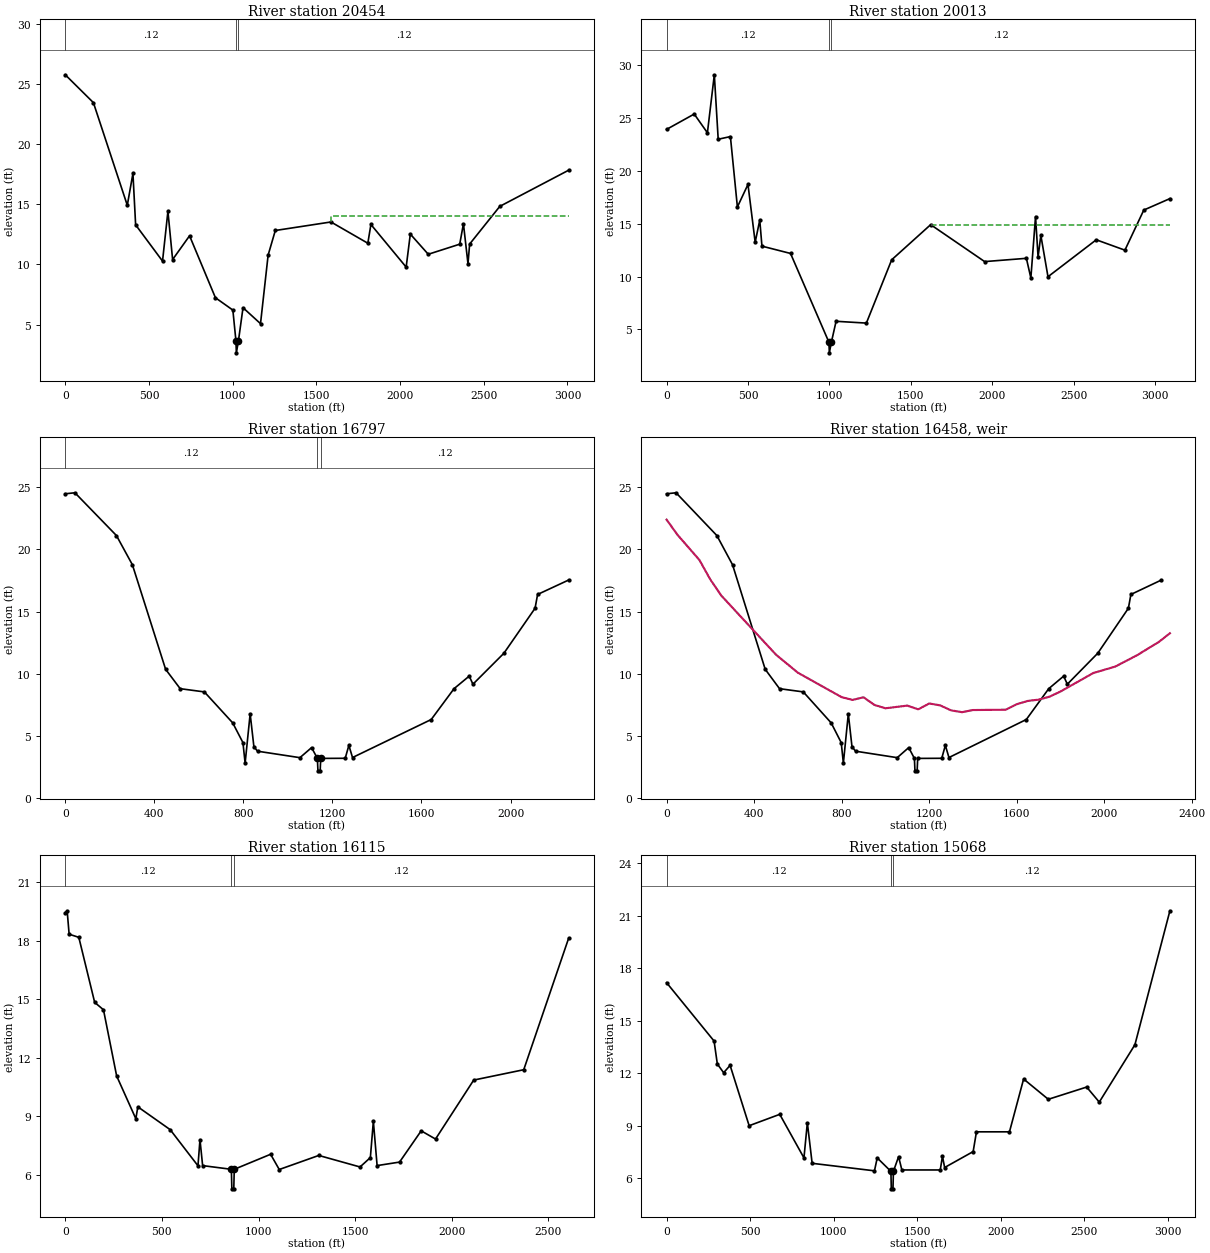
Type RM Length L Ch R = 1 ,20454   ,441.6,441.6,441.6
XS GIS Cut Line= 6
2302947.64806282468935.5531347242302382.03003158468135.263792647
2302357.96117918468105.177727156 2301278.5181247467147.701466358
2300986.49916948466891.8085674522300873.70515816466782.405735953
#Sta/Elev= 30
       0    25.8     168   23.48   370.5   14.93   404.2   17.58   420.3    13.3
     581   10.28   613.2   14.43   641.2   10.41   742.5   12.39     897    7.23
  1001.2     6.2  1019.5    3.64    1022    2.64  1034.5    3.64  1061.8     6.4
  1166.3    5.07  1211.8   10.78  1254.7   12.83  1587.1   13.54  1807.4   11.77
  1825.8   13.33  2036.4    9.78  2061.2   12.53  2168.4   10.85  2356.3   11.69
  2378.5   13.39  2405.7   10.06  2415.6    11.7  2595.8   14.84  3006.8   17.85
#Mann= 3 ,0,0
       0     .12       0  1019.5     .05       0  1034.5     .12       0
#XS Ineff= 2 , 0
       0                  1587.1       0      14
Permanent Ineff=
       F       F
Bank Sta=1019.5,1034.5
XS Rating Curve= 0 ,0
Exp/Cntr(USF)=0,0
Exp/Cntr=0.3,0.1

Type RM Length L Ch R = 1 ,20013   ,3216,3216,3216
BEGIN DESCRIPTION:
LETTERED XS L (Channel bottom from FIS profile)
END DESCRIPTION:
Node Name=L
XS GIS Cut Line= 6
2303180.71033738468744.2469862612302939.39004044468383.965979576
2302608.65682618467909.5520491752302513.23711435467783.509071374
2301193.19344355 466991.574453572300906.67502345466742.177588433
#Sta/Elev= 30
       0    23.9   169.9   25.35   250.9   23.58   293.4   29.06   317.2   22.97
   392.2   23.22   435.1   16.57   500.1    18.7   544.4   13.24   572.5   15.33
     586   12.87   761.6   12.18   997.5    3.79    1000    2.79  1012.5    3.79
  1041.4    5.77  1227.5     5.6    1383   11.58  1622.5    14.9  1954.1   11.41
  2210.5   11.72    2238    9.86  2266.7   15.67  2282.3   11.84  2299.3   13.89
  2343.2    9.98  2639.8   13.47  2815.8   12.49  2931.8   16.28  3092.2   17.36
#Mann= 3 ,0,0
       0     .12       0   997.5     .05       0  1012.5     .12       0
#XS Ineff= 2 , 0
       0                    1622       0    14.9
Permanent Ineff=
       F       F
Bank Sta=997.5,1012.5
XS Rating Curve= 0 ,0
Exp/Cntr(USF)=0,0
Exp/Cntr=0.3,0.1

Type RM Length L Ch R = 1 ,16797   ,681.9,681.9,681.9
BEGIN DESCRIPTION:
LETTERED XS K
END DESCRIPTION:
Node Name=K
XS GIS Cut Line= 5
2303937.92226084465630.2695093922303392.09208948465452.230762532
2302827.29065252465444.0349012092302436.83195498465455.139984259
2301839.45864639465877.063679807
#Sta/Elev= 30
       0   24.48    43.4   24.56   229.8   21.12   301.5   18.77   450.7   10.36
   516.2     8.8   624.8    8.54   752.1    6.05   798.1    4.46   807.9    2.81
   830.5    6.78   847.3    4.13   863.7    3.77    1054    3.25  1106.5    4.06
  1132.5    3.19    1135    2.19    1145    2.19  1147.5    3.19  1257.5     3.2
  1273.9    4.24  1290.3    3.26  1643.9    6.32  1746.3     8.8  1814.5    9.81
  1831.3    9.16  1970.3   11.65  2110.3   15.27  2121.7   16.38    2261   17.54
#Mann= 3 ,0,0
       0     .12       0  1132.5     .05       0  1147.5     .12       0
Bank Sta=1132.5,1147.5
XS Rating Curve= 0 ,0
Exp/Cntr(USF)=0,0
Exp/Cntr=0.3,0.1

Type RM Length L Ch R = 5 ,16458   ,,,
BEGIN DESCRIPTION:
Wappaoolah Rd
Wappaoolah Rd
END DESCRIPTION:
IW Pilot Flow=0
#Inline Weir SE= 30
       0  22.399      50  21.176     150  19.154     200  17.581     250  16.291
     500  11.536     600  10.084     800   8.119     850   7.895     900   8.108
     950   7.491    1000   7.223    1100   7.438    1150   7.136    1200   7.608
    1250   7.459    1300   7.054    1350   6.911    1400   7.081    1550   7.107
    1600   7.548    1650   7.813    1700   7.918    1750   8.156    1800   8.572
    1950  10.059    2050  10.576    2150  11.491    2250  12.567    2300  13.259
IW Dist,WD,Coef,Skew,MaxSub,Min_El,Is_Ogee,SpillHt,DesHd
332,13,2.6,0,0.98,, 0 ,,,2,2,
Inline Weir Flap Gates= 0
IW Outlet Rating Curve= 0 ,False,,

Type RM Length L Ch R = 1 ,16115   ,1046.9,1046.9,1046.9
BEGIN DESCRIPTION:
LETTERED XS J
END DESCRIPTION:
Node Name=J
XS GIS Cut Line= 6
2304014.28333919465126.1425069172303378.73445001464940.618307769
2303154.73808638464859.6167550912302955.51776613464795.079552995
2302560.45146012464877.7221797592301636.77604868465458.262158569
#Sta/Elev= 30
       0   19.44     9.7   19.53      20   18.33    70.1   18.17   152.1   14.84
   197.7   14.46   265.9   11.07   365.2    8.88   375.5    9.49     543    8.32
   686.7    6.47   697.1    7.81   710.8    6.48   859.5    6.29     862    5.29
     872    5.29   874.5    6.29  1062.5    7.06  1107.3    6.28  1311.9       7
  1525.3    6.41  1578.8    6.89  1594.3    8.75  1613.7    6.48  1729.9    6.66
  1841.8    8.26    1916    7.84  2113.6   10.86  2372.5   11.39  2604.7   18.12
#Mann= 3 ,0,0
       0     .12       0   859.5     .05       0   874.5     .12       0
Bank Sta=859.5,874.5
XS Rating Curve= 0 ,0
Exp/Cntr(USF)=0,0
Exp/Cntr=0.3,0.1

Type RM Length L Ch R = 1 ,15068   ,1999.1,1999.1,1999.1
BEGIN DESCRIPTION:
LETTERED XS I
END DESCRIPTION:
Node Name=I
XS GIS Cut Line= 3
2304643.37595087464337.1733138692303883.55276672463886.942150741
2301754.57862972463882.378684353
#Sta/Elev= 30
       0   17.18   284.4   13.84   303.8   12.53   341.6   12.03   380.2   12.45
   494.2       9   677.3    9.65   822.2    7.16   842.5    9.17   871.2    6.85
  1244.2    6.42  1260.6    7.16  1342.5    6.39    1345    5.39    1355    5.39
  1357.5    6.39  1388.5    7.23  1408.2    6.47  1637.9    6.47    1651    7.25
  1664.2    6.61  1834.8    7.52  1854.5    8.65  2052.1    8.65  2136.7   11.67
  2284.5   10.51    2514   11.21  2589.5   10.35  2802.8   13.63  3012.2   21.29
#Mann= 3 ,0,0
       0     .12       0  1342.5     .05       0  1357.5     .12       0
Bank Sta=1342.5,1357.5
XS Rating Curve= 0 ,0
Exp/Cntr(USF)=0,0
Exp/Cntr=0.3,0.1