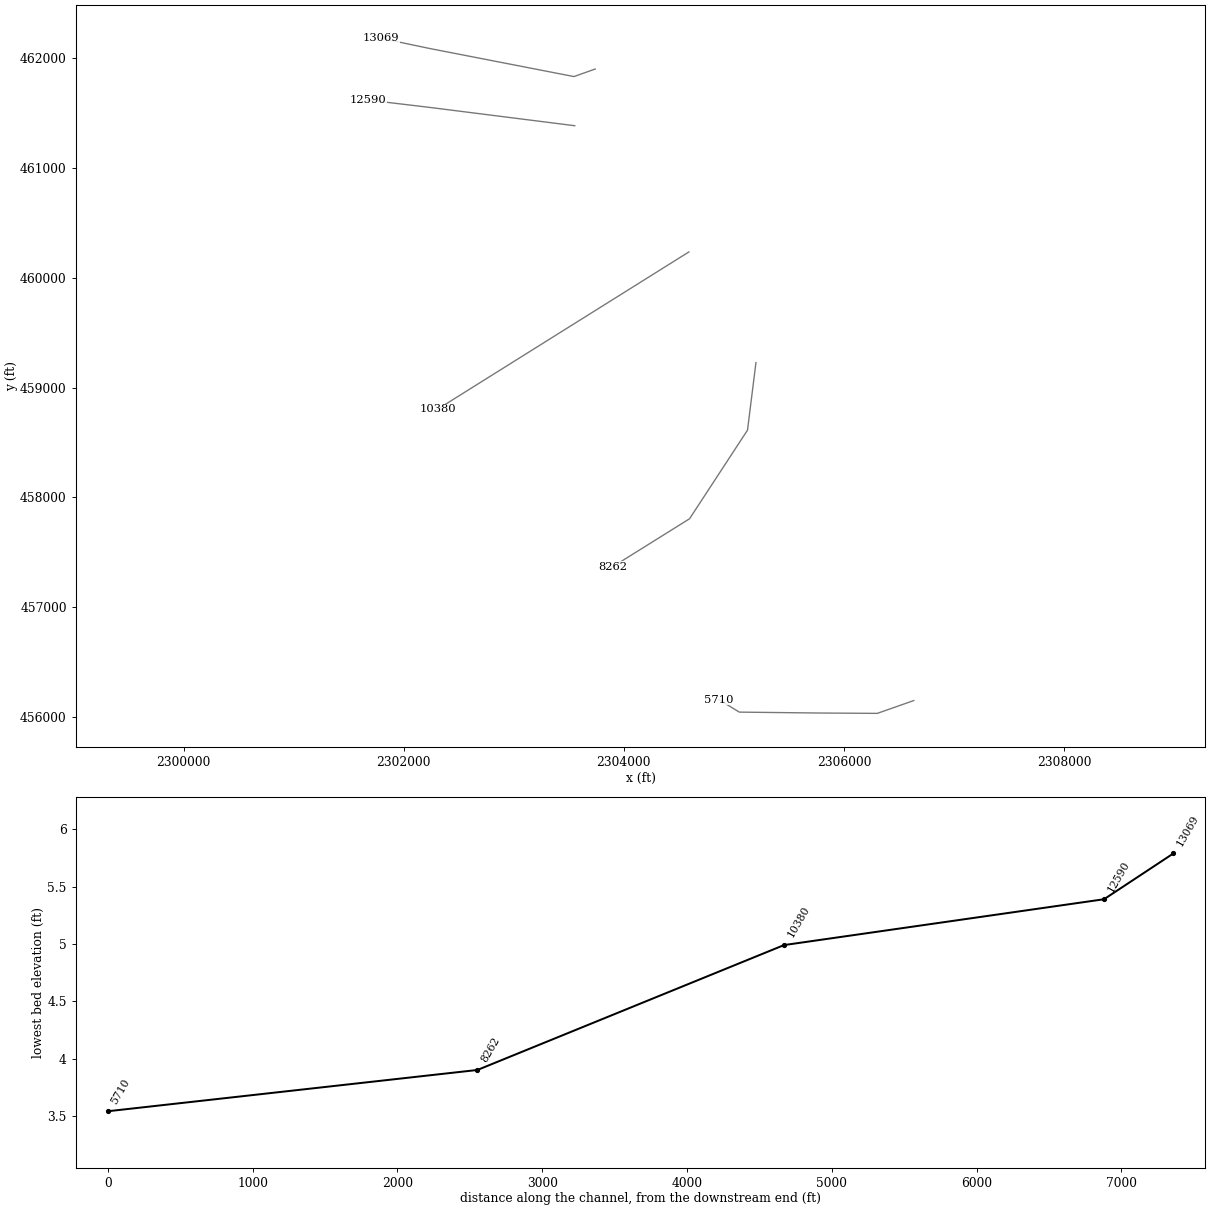
HEC-RAS study WapoolaCreek.prj: S-8-791 over Wapoola Creek

--- WapoolaCreek.g01 (geometry) --- (continued)

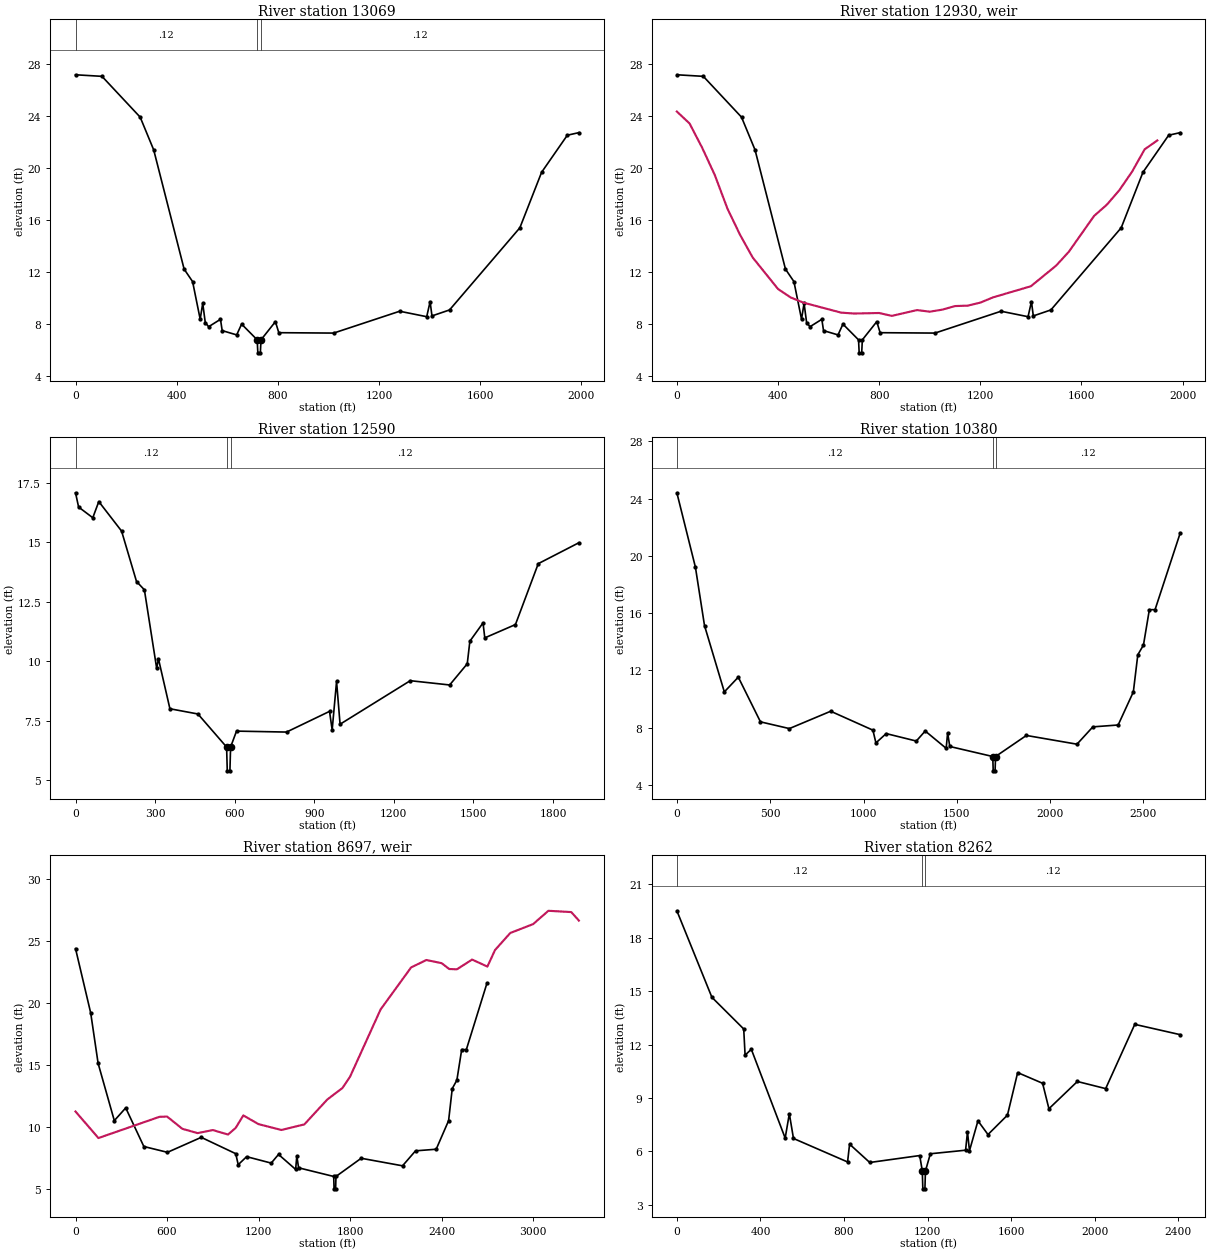
Type RM Length L Ch R = 1 ,13069   ,479.6,479.6,479.6
BEGIN DESCRIPTION:
LETTERED XS H
END DESCRIPTION:
Node Name=H
XS GIS Cut Line= 4
2303739.29728246461896.9032593622303546.44091051461828.385812557
2302238.75217319462082.9371162582301794.48596901462176.129130799
#Sta/Elev= 30
       0   27.18   104.6   27.06   255.7   23.92   309.2    21.4   429.5   12.23
     463   11.27     493    8.38   503.1     9.6   513.1    8.12   526.5     7.8
   573.3    8.37     580     7.5   637.4    7.17   656.8       8   718.5    6.79
     721    5.79     731    5.79   733.5    6.79   790.6    8.19   803.9    7.34
  1020.8    7.31    1282    8.99  1388.9    8.57  1402.3    9.73  1409.7    8.63
  1479.2    9.09  1757.3   15.41  1843.3   19.68    1945   22.53  1990.8   22.73
#Mann= 3 ,0,0
       0     .12       0   718.5     .05       0   733.5     .12       0
Bank Sta=718.5,733.5
XS Rating Curve= 0 ,0
Exp/Cntr(USF)=0,0
Exp/Cntr=0.3,0.1

Type RM Length L Ch R = 5 ,12930   ,,,
BEGIN DESCRIPTION:
Private Rd
END DESCRIPTION:
IW Pilot Flow=0
#Inline Weir SE= 30
       0   24.35      50   23.44     100  21.571     150  19.468     200  16.884
     250  14.865     300  13.121     400  10.703     450  10.051     500   9.653
     650   8.882     700   8.814     800   8.854     850   8.633     950    9.08
    1000   8.956    1050   9.113    1100   9.388    1150    9.42    1200   9.651
    1250  10.054    1400  10.912    1500    12.5    1550  13.562    1650   16.32
    1700  17.177    1750  18.303    1800  19.717    1850  21.445    1900  22.127
IW Dist,WD,Coef,Skew,MaxSub,Min_El,Is_Ogee,SpillHt,DesHd
133,12,2.6,0,0.98,, 0 ,,,2,2,
Inline Weir Flap Gates= 0
IW Outlet Rating Curve= 0 ,False,,

Type RM Length L Ch R = 1 ,12590   ,2210.1,2210.1,2210.1
BEGIN DESCRIPTION:
LETTERED XS G
END DESCRIPTION:
Node Name=G
XS GIS Cut Line= 3
2303553.78043171461381.2504360262302239.20703873461547.407159727
2301670.74455314461615.299807402
#Sta/Elev= 30
       0   17.08    11.6   16.48    65.1   16.03    87.7   16.71   173.6   15.47
   229.9   13.35   259.6      13   305.9     9.7   312.6    10.1   355.8       8
   461.4    7.78   569.5    6.39     572    5.39     582    5.39   584.5    6.39
   606.9    7.06   795.4    7.02   957.5    7.89   967.4    7.11     984    9.15
   997.2    7.35  1261.8    9.18  1410.3       9  1476.6    9.89  1486.5   10.84
  1536.1   11.61  1542.7   10.98  1658.3   11.54  1744.3    14.1  1897.5   14.98
#Mann= 3 ,0,0
       0     .12       0   569.5     .05       0   584.5     .12       0
Bank Sta=569.5,584.5
XS Rating Curve= 0 ,0
Exp/Cntr(USF)=0,0
Exp/Cntr=0.3,0.1

Type RM Length L Ch R = 1 ,10380   ,2117.7,2117.7,2117.7
BEGIN DESCRIPTION:
LETTERED XS F
END DESCRIPTION:
Node Name=F
XS GIS Cut Line= 2
2304591.26379284460233.4493018012302305.54854131458801.792450838
#Sta/Elev= 30
       0    24.4    99.5    19.2   148.1   15.13   254.3    10.5   329.1   11.53
   447.9    8.41   602.8    7.94   824.2    9.15  1050.4    7.83  1066.5    6.94
  1121.6    7.59  1282.9    7.07  1330.7    7.77    1443    6.56  1450.7    7.65
  1462.3    6.69  1692.5    5.99    1695    4.99    1705    4.99  1707.5    5.99
  1872.7    7.46  2143.8    6.85  2228.9    8.06  2364.4    8.19  2445.8    10.5
  2469.7   13.09    2500   13.77  2531.6   16.24  2562.1   16.24  2697.1    21.6
#Mann= 3 ,0,0
       0     .12       0  1692.5     .05       0  1707.5     .12       0
Bank Sta=1692.5,1707.5
XS Rating Curve= 0 ,0
Exp/Cntr(USF)=0,0
Exp/Cntr=0.3,0.1

Type RM Length L Ch R = 5 ,8697    ,,,
BEGIN DESCRIPTION:
Private Rd
END DESCRIPTION:
IW Pilot Flow=0
#Inline Weir SE= 30
       0  11.237     150   9.094     550  10.806     600  10.832     700   9.841
     800   9.491     900   9.739    1000   9.377    1050   9.915    1100  10.921
    1200  10.216    1350   9.746    1500  10.196    1650  12.201    1750   13.14
    1800  14.057    2000  19.485    2200  22.879    2300  23.479    2400  23.223
    2450  22.751    2500  22.727    2600  23.514    2700  22.947    2750  24.281
    2850  25.662    3000   26.38    3100  27.456    3250   27.35    3300  26.662
IW Dist,WD,Coef,Skew,MaxSub,Min_El,Is_Ogee,SpillHt,DesHd
1677,13,2.6,0,0.98,, 0 ,,,2,2,
Inline Weir Flap Gates= 0
IW Outlet Rating Curve= 0 ,False,,

Type RM Length L Ch R = 1 ,8262    ,2552,2552,2552
BEGIN DESCRIPTION:
LETTERED XS E
END DESCRIPTION:
Node Name=E
XS GIS Cut Line= 4
 2305200.6169154459226.7846019832305123.75637911458612.454945723
2304597.13294398457806.4922337072303895.79915137457368.326245636
#Sta/Elev= 30
       0   19.52   167.6   14.66   319.9   12.88   326.5   11.41   356.3   11.74
   518.3    6.75   538.2    8.12     558    6.73   816.9    5.41   826.5    6.41
     923    5.38  1162.1    5.77  1174.5     4.9    1177     3.9    1187     3.9
  1189.5     4.9    1213    5.87  1381.6    6.07  1390.7     7.1  1400.2    6.04
  1440.8    7.72  1488.8    6.95  1581.9    8.04  1630.8   10.43  1750.1    9.83
  1780.4     8.4  1916.5    9.93  2051.9    9.53  2191.2   13.14  2408.8   12.56
#Mann= 3 ,0,0
       0     .12       0  1174.5     .05       0  1189.5     .12       0
Bank Sta=1174.5,1189.5
XS Rating Curve= 0 ,0
Exp/Cntr(USF)=0,0
Exp/Cntr=0.3,0.1

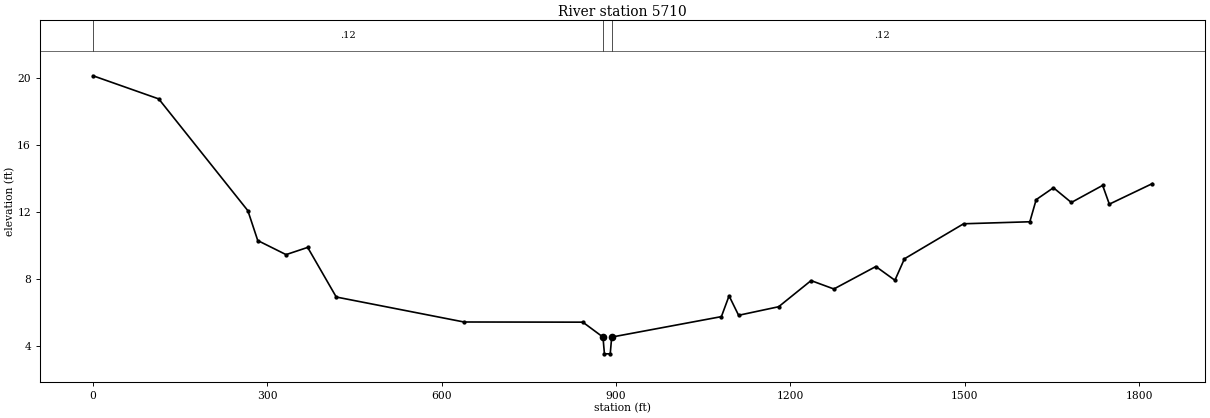
Type RM Length L Ch R = 1 ,5710    ,,,
BEGIN DESCRIPTION:
LETTERED XS D
END DESCRIPTION:
Node Name=D
XS GIS Cut Line= 5
2306634.78765407456152.8686219742306303.47530321456036.332101799
2305771.03817018456039.6030341372305049.47335917456047.794296906
2304863.71812244456161.501968033
#Sta/Elev= 30
       0   20.13     113   18.75   266.4   12.08   283.4    10.3   332.1    9.46
   369.3    9.89   418.5    6.93   638.3    5.44  842.82    5.43   877.5    4.54
     880    3.54     890    3.54   892.5    4.54  1081.3    5.76  1094.5       7
  1110.9    5.84  1179.8    6.35  1235.6    7.91  1274.9    7.41  1347.1    8.75
  1379.9    7.93  1396.3    9.21  1498.1    11.3  1612.1   11.42    1623   12.74
  1652.7   13.45  1683.5   12.57  1737.4   13.59  1748.9   12.47  1823.1    13.7
#Mann= 3 ,0,0
       0     .12       0   877.5     .05       0   892.5     .12       0
Bank Sta=877.5,892.5
XS Rating Curve= 0 ,0
Exp/Cntr(USF)=0,0
Exp/Cntr=0.3,0.1
LCMann Table=0

Chan Stop Cuts=-1
Use User Specified Reach Order=0
Composite Channel Slope=5

--- WapoolaCreek.g10 (geometry) ---

Geom Title=Proposed Conditions
Program Version=6.60

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
River Reach=River 1         ,Reach 1

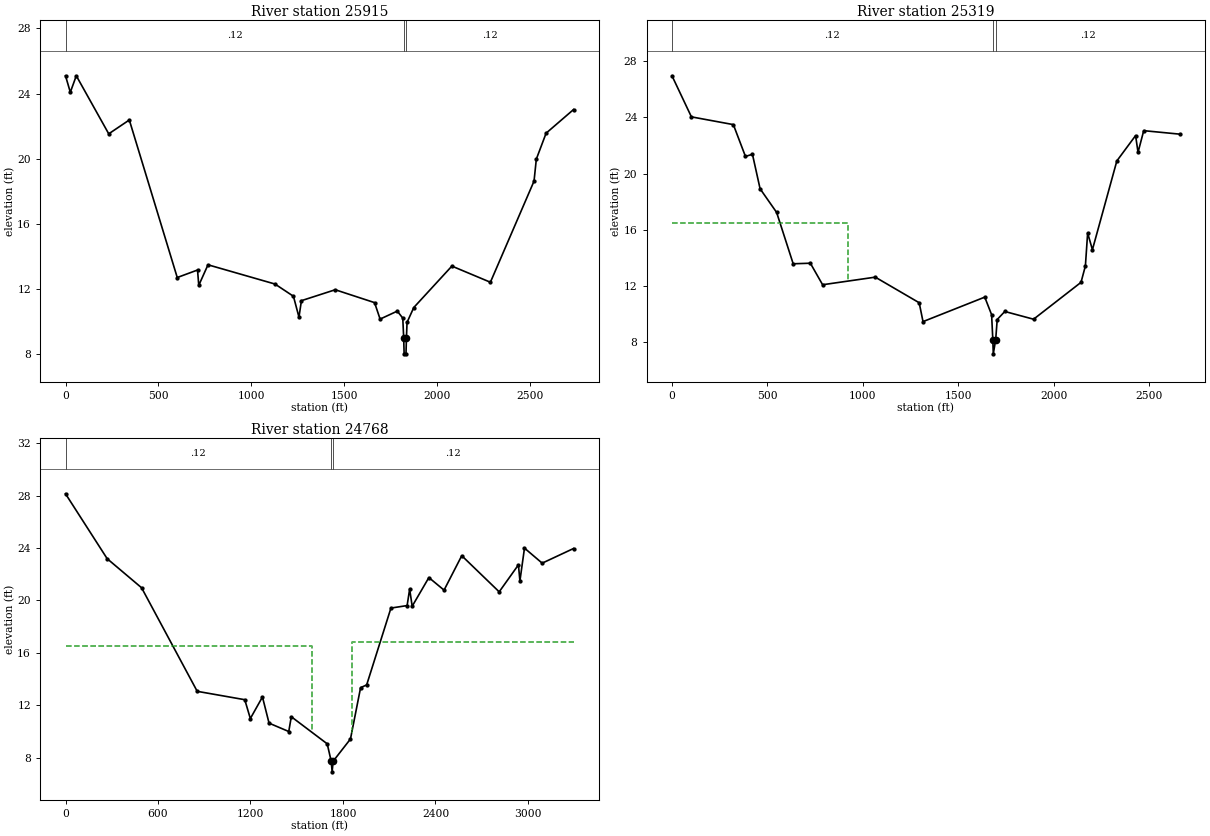
Type RM Length L Ch R = 1 ,25915   ,596.3,596.3,596.3
XS GIS Cut Line= 6
  2299978.943536469486.9291452262299731.49713724469188.243408806
 2299552.5489904467843.9374370592299545.82417894 467759.29731793
2299523.38360181467537.0589689482300006.84857433467053.937453047
#Sta/Elev= 30
       0   25.09    25.9   24.08    58.1   25.09   232.8   21.53   343.6   22.38
   601.7   12.72     711   13.18   717.6   12.24   767.3    13.5  1128.1   12.32
  1227.4   11.57  1257.2   10.29  1270.4    11.3  1452.5   11.97  1664.3   11.18
  1694.1   10.17  1786.7   10.66  1816.2   10.23    1821    9.04  1823.5    8.04
  1833.5    8.04    1836    9.04  1839.2    9.97  1875.5   10.88  2080.6   13.42
    2288   12.43    2523   18.63  2535.4   19.98    2588   21.57  2735.8   23.02
#Mann= 3 ,0,0
       0     .12       0    1821     .05       0    1836     .12       0
#XS Ineff= 2 , 0
       0 221.025   16.492568.975       0    16.8
Permanent Ineff=
       F       F
Bank Sta=1821,1836
XS Rating Curve= 0 ,0
Exp/Cntr(USF)=0,0
Exp/Cntr=0.5,0.3

Type RM Length L Ch R = 1 ,25319   ,551.1,551.1,551.1
XS GIS Cut Line= 5
2300242.39242795469548.6018239872299953.51308862467923.566066384
2299935.48686758467861.7913910882299855.50303648467461.845142113
2300198.88760843467048.376502058
#Sta/Elev= 30
       0   26.95   101.8   24.03   321.4   23.48   384.7   21.22   421.4   21.37
   461.4   18.92     548   17.24   634.7   13.59   724.6   13.63   788.8    12.1
  1064.6   12.64  1294.5   10.82  1314.5    9.48  1637.8   11.22 1673.71    9.97
    1680    8.19  1682.5    7.19    1695    8.19 1702.99    9.63  1742.8    10.2
  1893.4    9.65  2141.8   12.27  2164.8   13.44  2176.5   15.78  2201.5   14.59
  2329.5    20.9  2427.6    22.7  2440.4   21.51  2470.2   23.05  2660.2    22.8
#Mann= 3 ,0,0
       0     .12       0    1680     .05       0    1695     .12       0
#XS Ineff= 2 , 0
       0 921.025   16.492318.975       0    16.8
Permanent Ineff=
       F       F
Bank Sta=1680,1695
XS Rating Curve= 0 ,0
Exp/Cntr(USF)=0,0
Exp/Cntr=0.5,0.3

Type RM Length L Ch R = 1 ,24768   ,167.5,167.5,167.5
BEGIN DESCRIPTION:
LETTERED XS N (Channel bottom from Survey)
END DESCRIPTION:
Node Name=N
XS GIS Cut Line= 4
 2300298.8673546 469587.919463872300304.48241966468843.837061898
2300313.49474258467517.3176863722300336.38493535466292.152987895
#Sta/Elev= 30
       0   28.15   270.4   23.19   493.6   20.97   854.5   13.06    1163   12.42
  1199.1   10.98  1277.8   12.63  1320.5   10.63  1448.4    9.99  1464.8   11.12
  1697.8    9.05  1723.8    7.72 1729.83    6.91 1736.27    7.72  1848.8    9.42
  1914.4   13.34  1953.8   13.55  2111.3   19.42  2216.3   19.61  2232.7   20.87
  2249.1   19.56  2357.4   21.75  2455.9   20.79  2570.7   23.42  2813.6   20.66
  2938.3   22.72  2948.1    21.5  2977.7      24  3092.5   22.85    3296   23.97
#Mann= 3 ,0,0
       0     .12       0  1723.8     .05       0 1736.27     .12       0
#XS Ineff= 2 , 0
       01598.025   16.491855.975       0    16.8
Permanent Ineff=
       F       F
Bank Sta=1723.8,1736.27
XS Rating Curve= 0 ,0
Exp/Cntr(USF)=0,0
Exp/Cntr=0.5,0.3