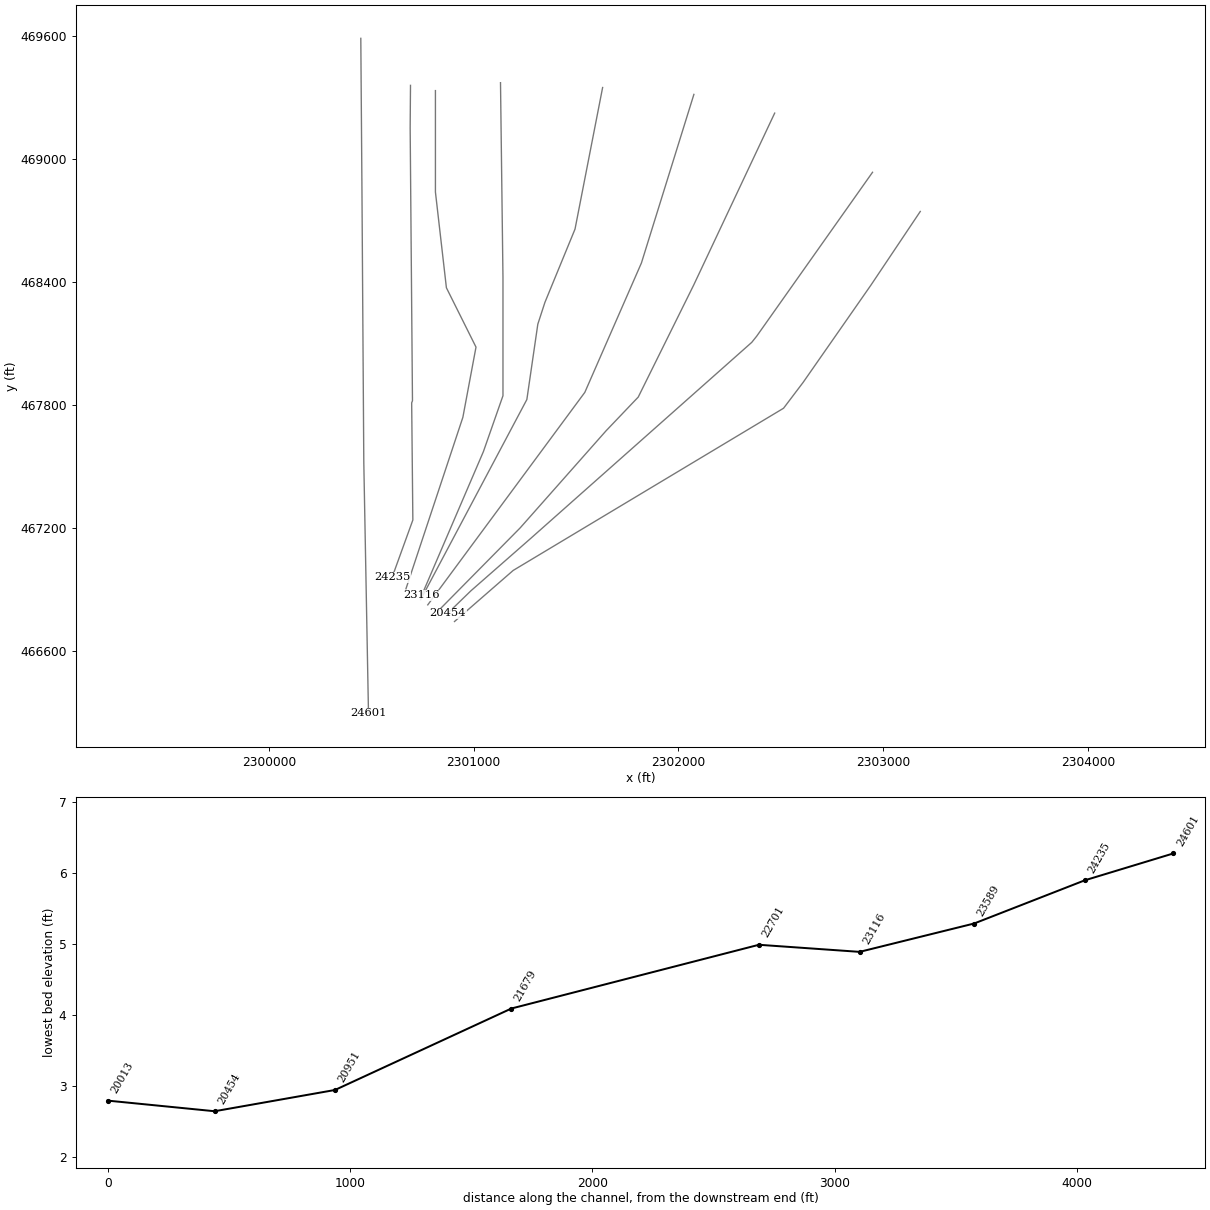
HEC-RAS study WapoolaCreek.prj: S-8-791 over Wapoola Creek

--- WapoolaCreek.g10 (geometry) --- (continued)

Type RM Length L Ch R = 3 ,24664   ,,,
BEGIN DESCRIPTION:
S-8-791 over Wapoola Creek
END DESCRIPTION:
Bridge Culvert--1,0,-1,-1, 0
Deck Dist Width WeirC Skew NumUp NumDn MinLoCord MaxHiCord MaxSubmerge Is_Ogee
83,43.55,2.6,0, 69, 69, , , 0.98, 0, 2,2,,
   -27.5    22.5    72.5   122.5   172.5   222.5   272.5   322.5   372.5   422.5
   472.5   522.5   572.5   622.5   672.5   722.5   772.5   822.5   872.5   922.5
   972.5  1022.5  1072.5  1122.5  1172.5  1222.5  1272.5  1322.5  1372.5  1422.5
  1472.5  1522.5  1572.5  1622.5 1681.99    1682    1772 1772.01  1818.5  1868.5
  1918.5  1968.5  2018.5  2068.5  2118.5  2168.5  2218.5  2268.5  2318.5  2368.5
  2418.5  2468.5  2518.5  2568.5  2618.5  2668.5  2718.5  2768.5  2818.5  2868.5
  2918.5  2968.5  3018.5  3068.5  3118.5  3168.5  3218.5  3268.5  3318.5
   27.42   26.98   26.22    25.8   24.62   23.89   23.28   22.63   21.85   21.06
   20.26   19.45   18.83   18.37    17.9   17.47   17.09   17.06   17.02    16.9
   16.72   16.62    16.6   16.56   16.76    16.7   16.68   16.68   16.61   16.49
   16.55   16.65    16.7    16.7   17.14   17.14   17.14   17.14   16.88   16.85
    16.8   17.03    17.3   17.58   17.88   18.19   18.55   18.88   19.21   19.55
   19.94   20.34   20.57   20.79   21.13    21.5   21.74   21.84   22.02   22.28
   22.56   22.76   22.96   23.18   23.38   23.58   23.77      24   23.85
                                                                                
                                                                                
                                                                                
                                           15.24   15.24
                                                                                
                                                                                
                                                                        
   -27.5    22.5    72.5   122.5   172.5   222.5   272.5   322.5   372.5   422.5
   472.5   522.5   572.5   622.5   672.5   722.5   772.5   822.5   872.5   922.5
   972.5  1022.5  1072.5  1122.5  1172.5  1222.5  1272.5  1322.5  1372.5  1422.5
  1472.5  1522.5  1572.5  1622.5 1681.99    1682    1772 1772.01  1818.5  1868.5
  1918.5  1968.5  2018.5  2068.5  2118.5  2168.5  2218.5  2268.5  2318.5  2368.5
  2418.5  2468.5  2518.5  2568.5  2618.5  2668.5  2718.5  2768.5  2818.5  2868.5
  2918.5  2968.5  3018.5  3068.5  3118.5  3168.5  3218.5  3268.5  3318.5
   27.42   26.98   26.22    25.8   24.62   23.89   23.28   22.63   21.85   21.06
   20.26   19.45   18.83   18.37    17.9   17.47   17.09   17.06   17.02    16.9
   16.72   16.62    16.6   16.56   16.76    16.7   16.68   16.68   16.61   16.49
   16.55   16.65    16.7    16.7   17.14   17.14   17.14   17.14   16.88   16.85
    16.8   17.03    17.3   17.58   17.88   18.19   18.55   18.88   19.21   19.55
   19.94   20.34   20.57   20.79   21.13    21.5   21.74   21.84   22.02   22.28
   22.56   22.76   22.96   23.18   23.38   23.58   23.77      24   23.85
                                                                                
                                                                                
                                                                                
                                           15.24   15.24
                                                                                
                                                                                
                                                                        
Pier Skew, UpSta & Num, DnSta & Num=  ,1712, 2 ,1712, 2 , 0 , 0 , 0 ,,
       2       2
       4      16
       2       2
       4      16
Pier Skew, UpSta & Num, DnSta & Num=  ,1742, 2 ,1742, 2 , 0 , 0 , 0 ,,
       2       2
       4      16
       2       2
       4      16
Abutment Skew #Up #Dn= , 3 , 3
 1681.99 1683.99 1693.19
      13      13     8.4
 1681.99 1683.99 1693.19
      13      13     8.4
Abutment Skew #Up #Dn= , 3 , 3
 1761.01 1770.01 1772.01
     8.5      13      13
 1761.01 1770.01 1772.01
     8.5      13      13
BR Coef=-1 ,-1 ,-1 ,1.25, 0 ,,,0.8,0,2,0,
WSPro=,,,, 1 ,,,, 0 ,,,, 0 ,,,,-1 ,-1 ,-1 , 0 , 0 , 0 , 0 , 0
BC Design=,, 0 ,, 0 ,,,,,,
BC Use User HTab Curves=0
BC User HTab FreeFlow(D)= 0

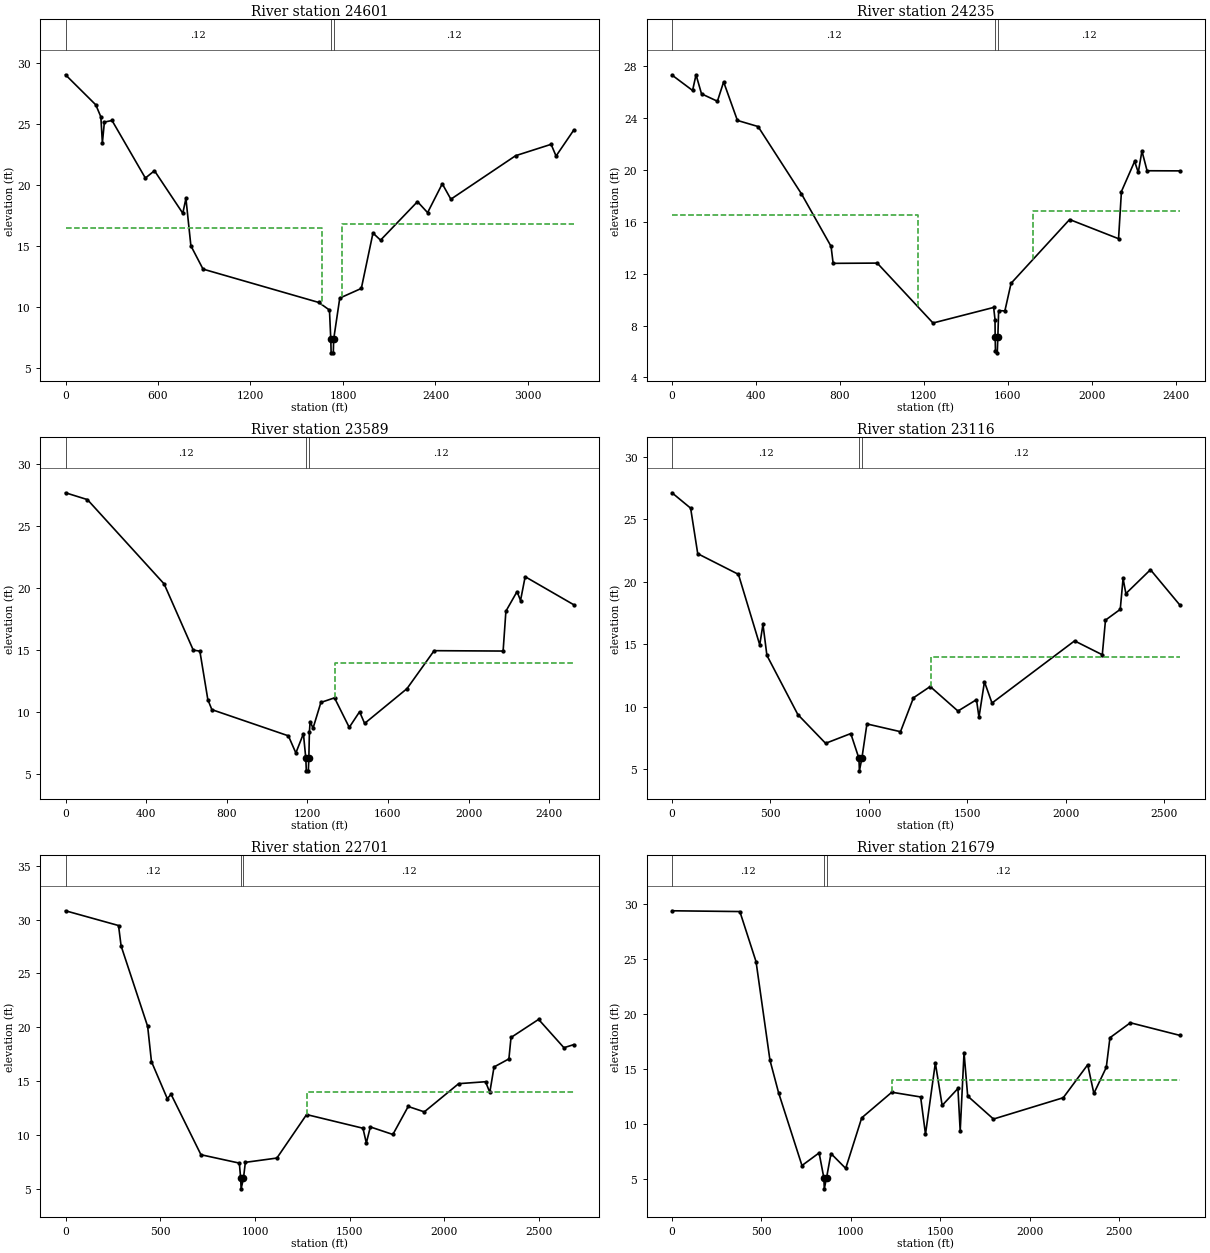
Type RM Length L Ch R = 1 ,24601   ,366.1,366.1,366.1
XS GIS Cut Line= 4
2300449.31206972469589.4839137532300454.92713478468845.401511781
 2300463.9394577467518.8821362552300486.82965047466293.717437778
#Sta/Elev= 30
       0   29.03   196.5   26.57   229.3   25.59   239.2   23.46   252.3   25.16
   301.8   25.29   518.1   20.58   577.2   21.18   760.9    17.7   781.2   18.91
   813.4   15.04   892.2   13.13  1643.6    10.4  1712.5    9.78 1721.09    7.38
 1723.32    6.28 1737.38    6.28 1739.74    7.39  1779.3   10.76  1919.2   11.55
  1994.7   16.08  2043.9    15.5  2283.5   18.65  2349.1   17.75  2444.3   20.11
  2500.1   18.85  2920.2   22.41  3150.5   23.34  3182.5   22.38    3296   24.48
#Mann= 3 ,0,0
       0     .12       0 1721.09     .05       0 1739.74     .12       0
#XS Ineff= 2 , 0
       01662.012   16.491791.988       0    16.8
Permanent Ineff=
       F       F
Bank Sta=1721.09,1739.74
XS Rating Curve= 0 ,0
Exp/Cntr(USF)=0,0
Exp/Cntr=0.5,0.3

Type RM Length L Ch R = 1 ,24235   ,456.9,456.9,456.9
BEGIN DESCRIPTION:
LETTERED XS M (Channel bottom from Survey)
END DESCRIPTION:
Node Name=M
XS GIS Cut Line= 6
2300691.89821835469359.8917309122300690.27254581469153.431319064
2300701.55822337467819.9775441342300697.65414775467809.851347998
2300703.40781971467237.8111847652300602.36719703466958.674533622
#Sta/Elev= 30
       0   27.32    98.2   26.13   114.6   27.34   140.8   25.87   216.5    25.3
   246.1   26.79   311.7   23.82   410.1   23.35   616.8   18.16   757.9   14.11
   767.8    12.8   977.8   12.82  1243.6     8.2  1532.4     9.4    1539    8.47
 1539.64    7.14  1541.1    6.03  1549.7     5.9  1552.5    7.13  1556.3    9.16
  1585.9    9.13  1615.4   11.26  1894.3   16.18  2127.5    14.7  2141.2   18.34
    2204   20.66  2221.5   19.81  2238.9   21.46  2263.4   19.94  2420.3   19.93
#Mann= 3 ,0,0
       0     .12       0 1539.64     .05       0  1552.5     .12       0
#XS Ineff= 2 , 0
       01171.512   16.491718.488       0    16.8
Permanent Ineff=
       F       F
Bank Sta=1539.64,1552.5
XS Rating Curve= 0 ,0
Exp/Cntr(USF)=0,0
Exp/Cntr=0.5,0.3

Type RM Length L Ch R = 1 ,23589   ,472.2,472.2,472.2
XS GIS Cut Line= 6
2300813.60767496469334.2949013382300813.60767496468839.102332148
2300867.22104368468371.6912358362301011.69436764468081.947900386
2300947.57928926 467739.099199852300669.82636797 466902.19753888
#Sta/Elev= 30
       0   27.69   108.7   27.14   489.3   20.35   633.9   15.02   666.8   14.93
   706.4   11.02   726.3   10.22    1106    8.11  1143.1    6.73  1180.6    8.28
  1192.5    6.29    1195    5.29    1205    5.29  1207.5    6.29  1210.3    8.42
  1213.9    9.25  1228.5    8.73  1267.3    10.8  1334.9   11.17    1408    8.79
  1459.3   10.05  1484.3    9.11  1694.5   11.91  1829.3   14.97  2171.6   14.94
  2185.4   18.15  2240.7   19.73    2258   19.01    2281   20.93  2521.1   18.68
#Mann= 3 ,0,0
       0     .12       0  1192.5     .05       0  1207.5     .12       0
#XS Ineff= 2 , 0
                          1334.9              14
Permanent Ineff=
       F       F
Bank Sta=1192.5,1207.5
XS Rating Curve= 0 ,0
Exp/Cntr(USF)=0,0
Exp/Cntr=0.3,0.1

Type RM Length L Ch R = 1 ,23116   ,415.7,415.7,415.7
XS GIS Cut Line= 5
2301131.34041205469372.9385808742301143.37483825468422.218911341
2301143.37483825467844.5664539032301047.85435224467571.792470774
2300746.47946227466869.537243461
#Sta/Elev= 30
       0   27.12    94.8   25.89   130.9   22.25   337.7    20.6     446   14.96
   462.4    16.6   482.4   14.12   639.6    9.39   780.7    7.09   908.6    7.87
     950    5.89   952.5    4.89     965    5.89   990.7    8.64  1161.3    8.02
  1227.2   10.73  1312.2   11.63  1453.3    9.67  1547.4   10.58  1560.1    9.17
  1587.9   12.01  1626.2   10.31  2045.9   15.28  2186.7   14.17    2203   16.94
    2278    17.8  2292.3   20.27  2306.6   19.06  2431.5   20.97  2581.7   18.13
#Mann= 3 ,0,0
       0     .12       0     950     .05       0     965     .12       0
#XS Ineff= 2 , 0
                          1315.2              14
Permanent Ineff=
       F       F
Bank Sta=950,965
XS Rating Curve= 0 ,0
Exp/Cntr(USF)=0,0
Exp/Cntr=0.3,0.1

Type RM Length L Ch R = 1 ,22701   ,1021.7,1021.7,1021.7
XS GIS Cut Line= 6
2301629.89948779469349.362652073 2301495.1204016 468658.07991878
2301348.13253272468300.2897328482301313.51040238468193.901677413
2301259.98004178467825.9552139932300741.37792624466848.666359408
#Sta/Elev= 30
       0   30.82   279.9   29.45   293.4   27.56   433.6   20.08   453.7   16.81
   537.3   13.37   557.3   13.77   714.9    8.16   917.6    7.38   924.5    5.99
     927    4.99   939.5    5.99   949.3    7.45  1115.8    7.85  1272.6   11.89
  1570.1   10.62  1587.9    9.25  1609.1   10.74    1728   10.04  1808.9   12.64
  1893.9   12.14  2075.3   14.76  2217.2   14.94  2239.6   13.95    2262   16.31
  2340.4   17.06  2351.6   19.05  2497.2   20.73  2630.9    18.1  2681.7   18.38
#Mann= 3 ,0,0
       0     .12       0   924.5     .05       0   939.5     .12       0
#XS Ineff= 2 , 0
                          1272.6              14
Permanent Ineff=
       F       F
Bank Sta=924.5,939.5
XS Rating Curve= 0 ,0
Exp/Cntr(USF)=0,0
Exp/Cntr=0.3,0.1

Type RM Length L Ch R = 1 ,21679   ,728,728,728
XS GIS Cut Line= 4
2302075.46116425469315.7757536512301819.31072934468492.685218829
2301542.99719806467861.0056250092300776.21828518466823.488605643
#Sta/Elev= 30
       0   29.39   379.7   29.32   470.3   24.76     548    15.8   596.2   12.84
   727.1    6.21     823    7.36   849.5    5.09     852    4.09   864.5    5.09
   889.4     7.3   971.7    5.95  1061.3   10.55  1229.6   12.88  1390.8   12.45
    1418    9.06  1473.1   15.54  1511.2   11.68  1599.5   13.22  1612.1    9.35
  1633.6   16.49    1654   12.53  1798.3   10.44  2188.5   12.38  2325.3   15.38
  2359.8   12.77  2429.2   15.14  2449.7   17.84  2563.9    19.2  2841.6   18.05
#Mann= 3 ,0,0
       0     .12       0   849.5     .05       0   864.5     .12       0
#XS Ineff= 2 , 0
                          1229.6              14
Permanent Ineff=
       F       F
Bank Sta=849.5,864.5
XS Rating Curve= 0 ,0
Exp/Cntr(USF)=0,0
Exp/Cntr=0.3,0.1

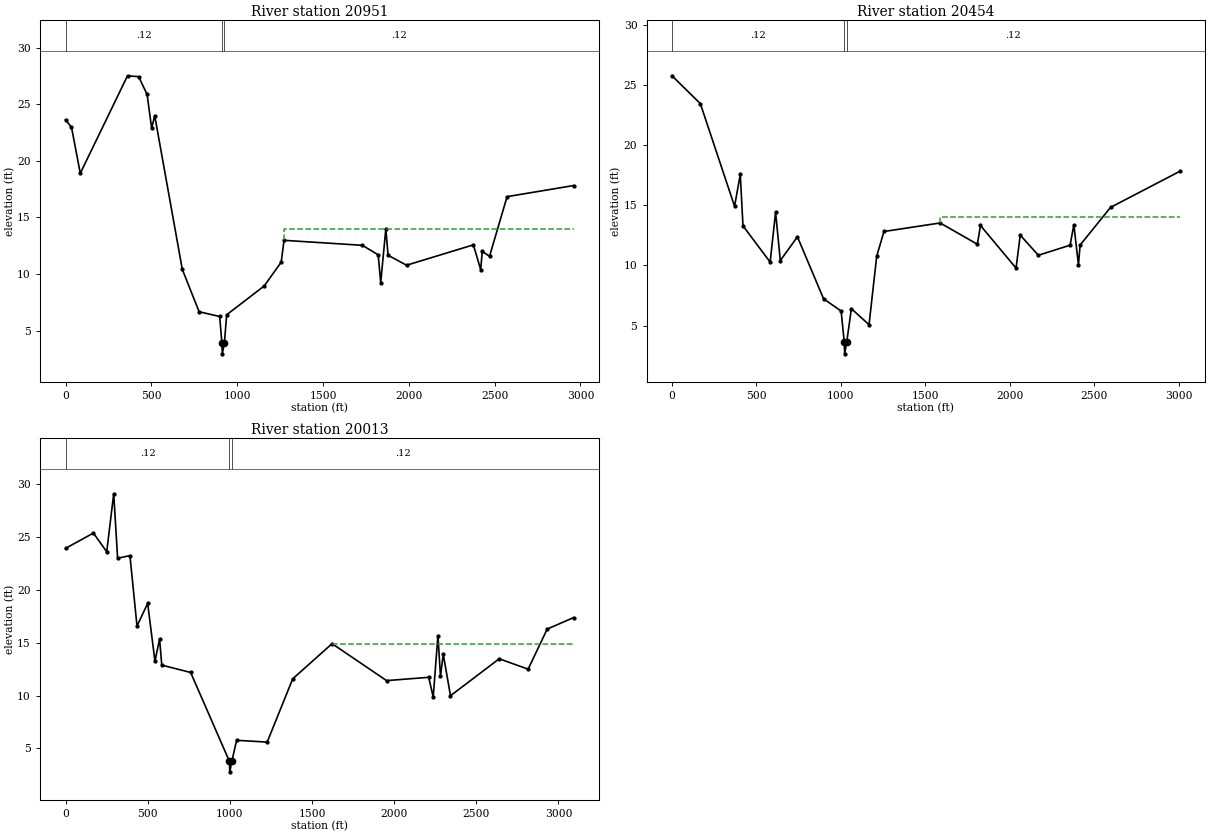
Type RM Length L Ch R = 1 ,20951   ,496.6,496.6,496.6
XS GIS Cut Line= 6
2302469.88134281469224.3793634432302074.55044225468384.978136227
2301803.77585283 467838.013465592301646.41127995467673.029264329
2301227.80853499467199.8622153142300833.05544833466799.929758738
#Sta/Elev= 30
       0   23.62    34.9   22.96    86.1   18.89   361.3   27.51   426.1   27.43
   475.4   25.86   501.9   22.88   519.8   23.98   680.5    10.4   778.4    6.66
   898.1    6.24     911    3.94   913.5    2.94     926    3.94   938.9    6.39
  1157.8    8.94  1256.6   11.04  1273.2   12.97  1729.1   12.53  1821.7   11.69
  1836.5    9.23  1866.2   13.99  1879.3   11.65  1987.1   10.77  2376.3   12.57
  2418.9   10.38    2428   11.99  2470.5   11.56  2572.6   16.83  2959.9   17.81
#Mann= 3 ,0,0
       0     .12       0     911     .05       0     926     .12       0
#XS Ineff= 2 , 0
                          1273.2              14
Permanent Ineff=
       F       F
Bank Sta=911,926
XS Rating Curve= 0 ,0
Exp/Cntr(USF)=0,0
Exp/Cntr=0.3,0.1

Type RM Length L Ch R = 1 ,20454   ,441.6,441.6,441.6
XS GIS Cut Line= 6
2302947.64806282468935.5531347242302382.03003158468135.263792647
2302357.96117918468105.177727156 2301278.5181247467147.701466358
2300986.49916948466891.8085674522300873.70515816466782.405735953
#Sta/Elev= 30
       0    25.8     168   23.48   370.5   14.93   404.2   17.58   420.3    13.3
     581   10.28   613.2   14.43   641.2   10.41   742.5   12.39     897    7.23
  1001.2     6.2  1019.5    3.64    1022    2.64  1034.5    3.64  1061.8     6.4
  1166.3    5.07  1211.8   10.78  1254.7   12.83  1587.1   13.54  1807.4   11.77
  1825.8   13.33  2036.4    9.78  2061.2   12.53  2168.4   10.85  2356.3   11.69
  2378.5   13.39  2405.7   10.06  2415.6    11.7  2595.8   14.84  3006.8   17.85
#Mann= 3 ,0,0
       0     .12       0  1019.5     .05       0  1034.5     .12       0
#XS Ineff= 2 , 0
                          1587.1              14
Permanent Ineff=
       F       F
Bank Sta=1019.5,1034.5
XS Rating Curve= 0 ,0
Exp/Cntr(USF)=0,0
Exp/Cntr=0.3,0.1

Type RM Length L Ch R = 1 ,20013   ,3216,3216,3216
BEGIN DESCRIPTION:
LETTERED XS L (Channel bottom from FIS profile)
END DESCRIPTION:
Node Name=L
XS GIS Cut Line= 6
2303180.71033738468744.2469862612302939.39004044468383.965979576
2302608.65682618467909.5520491752302513.23711435467783.509071374
2301193.19344355 466991.574453572300906.67502345466742.177588433
#Sta/Elev= 30
       0    23.9   169.9   25.35   250.9   23.58   293.4   29.06   317.2   22.97
   392.2   23.22   435.1   16.57   500.1    18.7   544.4   13.24   572.5   15.33
     586   12.87   761.6   12.18   997.5    3.79    1000    2.79  1012.5    3.79
  1041.4    5.77  1227.5     5.6    1383   11.58  1622.5    14.9  1954.1   11.41
  2210.5   11.72    2238    9.86  2266.7   15.67  2282.3   11.84  2299.3   13.89
  2343.2    9.98  2639.8   13.47  2815.8   12.49  2931.8   16.28  3092.2   17.36
#Mann= 3 ,0,0
       0     .12       0   997.5     .05       0  1012.5     .12       0
#XS Ineff= 2 , 0
                            1622            14.9
Permanent Ineff=
       F       F
Bank Sta=997.5,1012.5
XS Rating Curve= 0 ,0
Exp/Cntr(USF)=0,0
Exp/Cntr=0.3,0.1

--- WapoolaCreek.g11 (geometry) ---

Geom Title=Natural Conditions
Program Version=6.60

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
River Reach=River 1         ,Reach 1

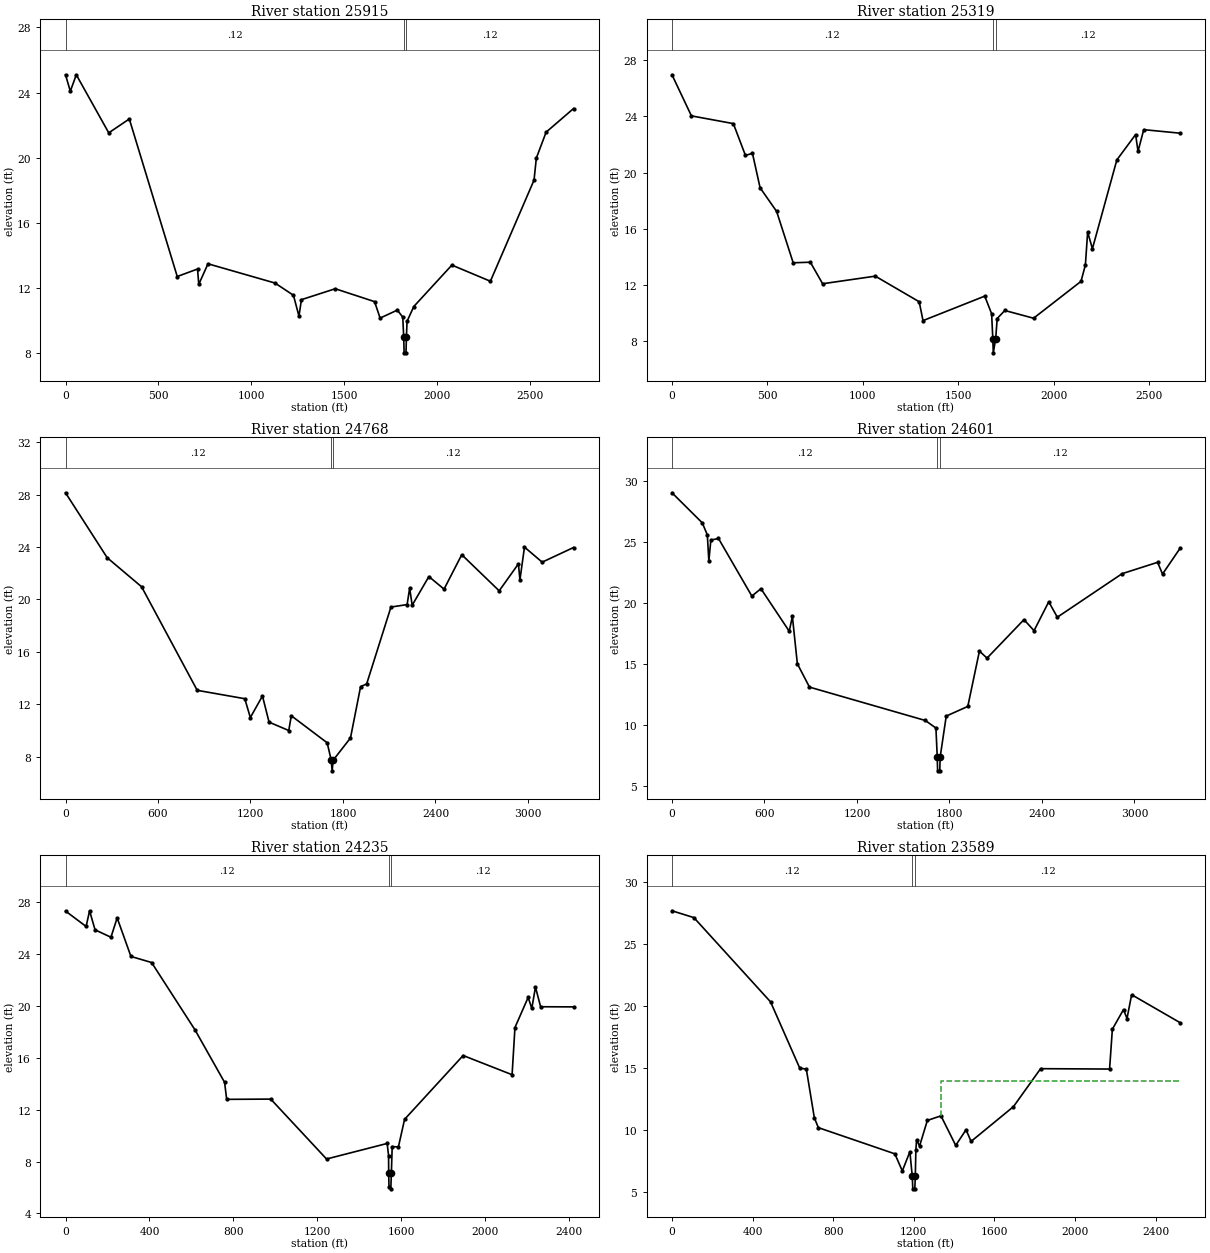
Type RM Length L Ch R = 1 ,25915   ,596.3,596.3,596.3
XS GIS Cut Line= 6
  2299978.943536469486.9291452262299731.49713724469188.243408806
 2299552.5489904467843.9374370592299545.82417894 467759.29731793
2299523.38360181467537.0589689482300006.84857433467053.937453047
#Sta/Elev= 30
       0   25.09    25.9   24.08    58.1   25.09   232.8   21.53   343.6   22.38
   601.7   12.72     711   13.18   717.6   12.24   767.3    13.5  1128.1   12.32
  1227.4   11.57  1257.2   10.29  1270.4    11.3  1452.5   11.97  1664.3   11.18
  1694.1   10.17  1786.7   10.66  1816.2   10.23    1821    9.04  1823.5    8.04
  1833.5    8.04    1836    9.04  1839.2    9.97  1875.5   10.88  2080.6   13.42
    2288   12.43    2523   18.63  2535.4   19.98    2588   21.57  2735.8   23.02
#Mann= 3 ,0,0
       0     .12       0    1821     .05       0    1836     .12       0
Bank Sta=1821,1836
XS Rating Curve= 0 ,0
Exp/Cntr(USF)=0,0
Exp/Cntr=0.3,0.1

Type RM Length L Ch R = 1 ,25319   ,551.1,551.1,551.1
XS GIS Cut Line= 5
2300242.39242795469548.6018239872299953.51308862467923.566066384
2299935.48686758467861.7913910882299855.50303648467461.845142113
2300198.88760843467048.376502058
#Sta/Elev= 30
       0   26.95   101.8   24.03   321.4   23.48   384.7   21.22   421.4   21.37
   461.4   18.92     548   17.24   634.7   13.59   724.6   13.63   788.8    12.1
  1064.6   12.64  1294.5   10.82  1314.5    9.48  1637.8   11.22 1673.71    9.97
    1680    8.19  1682.5    7.19    1695    8.19 1702.99    9.63  1742.8    10.2
  1893.4    9.65  2141.8   12.27  2164.8   13.44  2176.5   15.78  2201.5   14.59
  2329.5    20.9  2427.6    22.7  2440.4   21.51  2470.2   23.05  2660.2    22.8
#Mann= 3 ,0,0
       0     .12       0    1680     .05       0    1695     .12       0
Bank Sta=1680,1695
XS Rating Curve= 0 ,0
Exp/Cntr(USF)=0,0
Exp/Cntr=0.3,0.1

Type RM Length L Ch R = 1 ,24768   ,167.5,167.5,167.5
BEGIN DESCRIPTION:
LETTERED XS N (Channel bottom from Survey)
END DESCRIPTION:
Node Name=N
XS GIS Cut Line= 4
 2300298.8673546 469587.919463872300304.48241966468843.837061898
2300313.49474258467517.3176863722300336.38493535466292.152987895
#Sta/Elev= 30
       0   28.15   270.4   23.19   493.6   20.97   854.5   13.06    1163   12.42
  1199.1   10.98  1277.8   12.63  1320.5   10.63  1448.4    9.99  1464.8   11.12
  1697.8    9.05  1723.8    7.72 1729.83    6.91 1736.27    7.72  1848.8    9.42
  1914.4   13.34  1953.8   13.55  2111.3   19.42  2216.3   19.61  2232.7   20.87
  2249.1   19.56  2357.4   21.75  2455.9   20.79  2570.7   23.42  2813.6   20.66
  2938.3   22.72  2948.1    21.5  2977.7      24  3092.5   22.85    3296   23.97
#Mann= 3 ,0,0
       0     .12       0  1723.8     .05       0 1736.27     .12       0
Bank Sta=1723.8,1736.27
XS Rating Curve= 0 ,0
Exp/Cntr(USF)=0,0
Exp/Cntr=0.3,0.1

Type RM Length L Ch R = 1 ,24601   ,366.1,366.1,366.1
XS GIS Cut Line= 4
2300449.31206972469589.4839137532300454.92713478468845.401511781
 2300463.9394577467518.8821362552300486.82965047466293.717437778
#Sta/Elev= 30
       0   29.03   196.5   26.57   229.3   25.59   239.2   23.46   252.3   25.16
   301.8   25.29   518.1   20.58   577.2   21.18   760.9    17.7   781.2   18.91
   813.4   15.04   892.2   13.13  1643.6    10.4  1712.5    9.78 1721.09    7.38
 1723.32    6.28 1737.38    6.28 1739.74    7.39  1779.3   10.76  1919.2   11.55
  1994.7   16.08  2043.9    15.5  2283.5   18.65  2349.1   17.75  2444.3   20.11
  2500.1   18.85  2920.2   22.41  3150.5   23.34  3182.5   22.38    3296   24.48
#Mann= 3 ,0,0
       0     .12       0 1721.09     .05       0 1739.74     .12       0
Bank Sta=1721.09,1739.74
XS Rating Curve= 0 ,0
Exp/Cntr(USF)=0,0
Exp/Cntr=0.3,0.1

Type RM Length L Ch R = 1 ,24235   ,456.9,456.9,456.9
BEGIN DESCRIPTION:
LETTERED XS M (Channel bottom from Survey)
END DESCRIPTION:
Node Name=M
XS GIS Cut Line= 6
2300691.89821835469359.8917309122300690.27254581469153.431319064
2300701.55822337467819.9775441342300697.65414775467809.851347998
2300703.40781971467237.8111847652300602.36719703466958.674533622
#Sta/Elev= 30
       0   27.32    98.2   26.13   114.6   27.34   140.8   25.87   216.5    25.3
   246.1   26.79   311.7   23.82   410.1   23.35   616.8   18.16   757.9   14.11
   767.8    12.8   977.8   12.82  1243.6     8.2  1532.4     9.4    1539    8.47
 1539.64    7.14  1541.1    6.03  1549.7     5.9  1552.5    7.13  1556.3    9.16
  1585.9    9.13  1615.4   11.26  1894.3   16.18  2127.5    14.7  2141.2   18.34
    2204   20.66  2221.5   19.81  2238.9   21.46  2263.4   19.94  2420.3   19.93
#Mann= 3 ,0,0
       0     .12       0 1539.64     .05       0  1552.5     .12       0
Bank Sta=1539.64,1552.5
XS Rating Curve= 0 ,0
Exp/Cntr(USF)=0,0
Exp/Cntr=0.3,0.1

Type RM Length L Ch R = 1 ,23589   ,472.2,472.2,472.2
XS GIS Cut Line= 6
2300813.60767496469334.2949013382300813.60767496468839.102332148
2300867.22104368468371.6912358362301011.69436764468081.947900386
2300947.57928926 467739.099199852300669.82636797 466902.19753888
#Sta/Elev= 30
       0   27.69   108.7   27.14   489.3   20.35   633.9   15.02   666.8   14.93
   706.4   11.02   726.3   10.22    1106    8.11  1143.1    6.73  1180.6    8.28
  1192.5    6.29    1195    5.29    1205    5.29  1207.5    6.29  1210.3    8.42
  1213.9    9.25  1228.5    8.73  1267.3    10.8  1334.9   11.17    1408    8.79
  1459.3   10.05  1484.3    9.11  1694.5   11.91  1829.3   14.97  2171.6   14.94
  2185.4   18.15  2240.7   19.73    2258   19.01    2281   20.93  2521.1   18.68
#Mann= 3 ,0,0
       0     .12       0  1192.5     .05       0  1207.5     .12       0
#XS Ineff= 2 , 0
                          1334.9              14
Permanent Ineff=
       F       F
Bank Sta=1192.5,1207.5
XS Rating Curve= 0 ,0
Exp/Cntr(USF)=0,0
Exp/Cntr=0.3,0.1

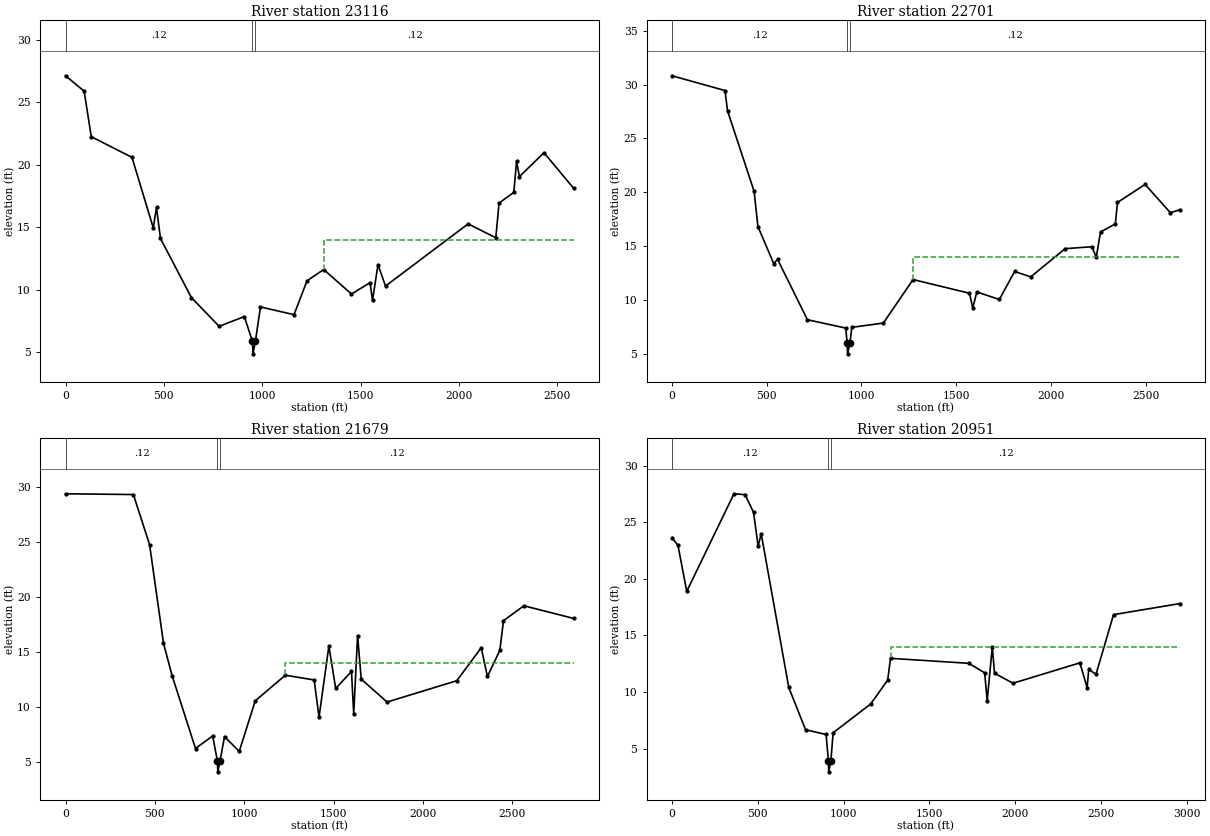
Type RM Length L Ch R = 1 ,23116   ,415.7,415.7,415.7
XS GIS Cut Line= 5
2301131.34041205469372.9385808742301143.37483825468422.218911341
2301143.37483825467844.5664539032301047.85435224467571.792470774
2300746.47946227466869.537243461
#Sta/Elev= 30
       0   27.12    94.8   25.89   130.9   22.25   337.7    20.6     446   14.96
   462.4    16.6   482.4   14.12   639.6    9.39   780.7    7.09   908.6    7.87
     950    5.89   952.5    4.89     965    5.89   990.7    8.64  1161.3    8.02
  1227.2   10.73  1312.2   11.63  1453.3    9.67  1547.4   10.58  1560.1    9.17
  1587.9   12.01  1626.2   10.31  2045.9   15.28  2186.7   14.17    2203   16.94
    2278    17.8  2292.3   20.27  2306.6   19.06  2431.5   20.97  2581.7   18.13
#Mann= 3 ,0,0
       0     .12       0     950     .05       0     965     .12       0
#XS Ineff= 2 , 0
                          1315.2              14
Permanent Ineff=
       F       F
Bank Sta=950,965
XS Rating Curve= 0 ,0
Exp/Cntr(USF)=0,0
Exp/Cntr=0.3,0.1

Type RM Length L Ch R = 1 ,22701   ,1021.7,1021.7,1021.7
XS GIS Cut Line= 6
2301629.89948779469349.362652073 2301495.1204016 468658.07991878
2301348.13253272468300.2897328482301313.51040238468193.901677413
2301259.98004178467825.9552139932300741.37792624466848.666359408
#Sta/Elev= 30
       0   30.82   279.9   29.45   293.4   27.56   433.6   20.08   453.7   16.81
   537.3   13.37   557.3   13.77   714.9    8.16   917.6    7.38   924.5    5.99
     927    4.99   939.5    5.99   949.3    7.45  1115.8    7.85  1272.6   11.89
  1570.1   10.62  1587.9    9.25  1609.1   10.74    1728   10.04  1808.9   12.64
  1893.9   12.14  2075.3   14.76  2217.2   14.94  2239.6   13.95    2262   16.31
  2340.4   17.06  2351.6   19.05  2497.2   20.73  2630.9    18.1  2681.7   18.38
#Mann= 3 ,0,0
       0     .12       0   924.5     .05       0   939.5     .12       0
#XS Ineff= 2 , 0
                          1272.6              14
Permanent Ineff=
       F       F
Bank Sta=924.5,939.5
XS Rating Curve= 0 ,0
Exp/Cntr(USF)=0,0
Exp/Cntr=0.3,0.1

Type RM Length L Ch R = 1 ,21679   ,728,728,728
XS GIS Cut Line= 4
2302075.46116425469315.7757536512301819.31072934468492.685218829
2301542.99719806467861.0056250092300776.21828518466823.488605643
#Sta/Elev= 30
       0   29.39   379.7   29.32   470.3   24.76     548    15.8   596.2   12.84
   727.1    6.21     823    7.36   849.5    5.09     852    4.09   864.5    5.09
   889.4     7.3   971.7    5.95  1061.3   10.55  1229.6   12.88  1390.8   12.45
    1418    9.06  1473.1   15.54  1511.2   11.68  1599.5   13.22  1612.1    9.35
  1633.6   16.49    1654   12.53  1798.3   10.44  2188.5   12.38  2325.3   15.38
  2359.8   12.77  2429.2   15.14  2449.7   17.84  2563.9    19.2  2841.6   18.05
#Mann= 3 ,0,0
       0     .12       0   849.5     .05       0   864.5     .12       0
#XS Ineff= 2 , 0
                          1229.6              14
Permanent Ineff=
       F       F
Bank Sta=849.5,864.5
XS Rating Curve= 0 ,0
Exp/Cntr(USF)=0,0
Exp/Cntr=0.3,0.1

Type RM Length L Ch R = 1 ,20951   ,496.6,496.6,496.6
XS GIS Cut Line= 6
2302469.88134281469224.3793634432302074.55044225468384.978136227
2301803.77585283 467838.013465592301646.41127995467673.029264329
2301227.80853499467199.8622153142300833.05544833466799.929758738
#Sta/Elev= 30
       0   23.62    34.9   22.96    86.1   18.89   361.3   27.51   426.1   27.43
   475.4   25.86   501.9   22.88   519.8   23.98   680.5    10.4   778.4    6.66
   898.1    6.24     911    3.94   913.5    2.94     926    3.94   938.9    6.39
  1157.8    8.94  1256.6   11.04  1273.2   12.97  1729.1   12.53  1821.7   11.69
  1836.5    9.23  1866.2   13.99  1879.3   11.65  1987.1   10.77  2376.3   12.57
  2418.9   10.38    2428   11.99  2470.5   11.56  2572.6   16.83  2959.9   17.81
#Mann= 3 ,0,0
       0     .12       0     911     .05       0     926     .12       0
#XS Ineff= 2 , 0
                          1273.2              14
Permanent Ineff=
       F       F
Bank Sta=911,926
XS Rating Curve= 0 ,0
Exp/Cntr(USF)=0,0
Exp/Cntr=0.3,0.1